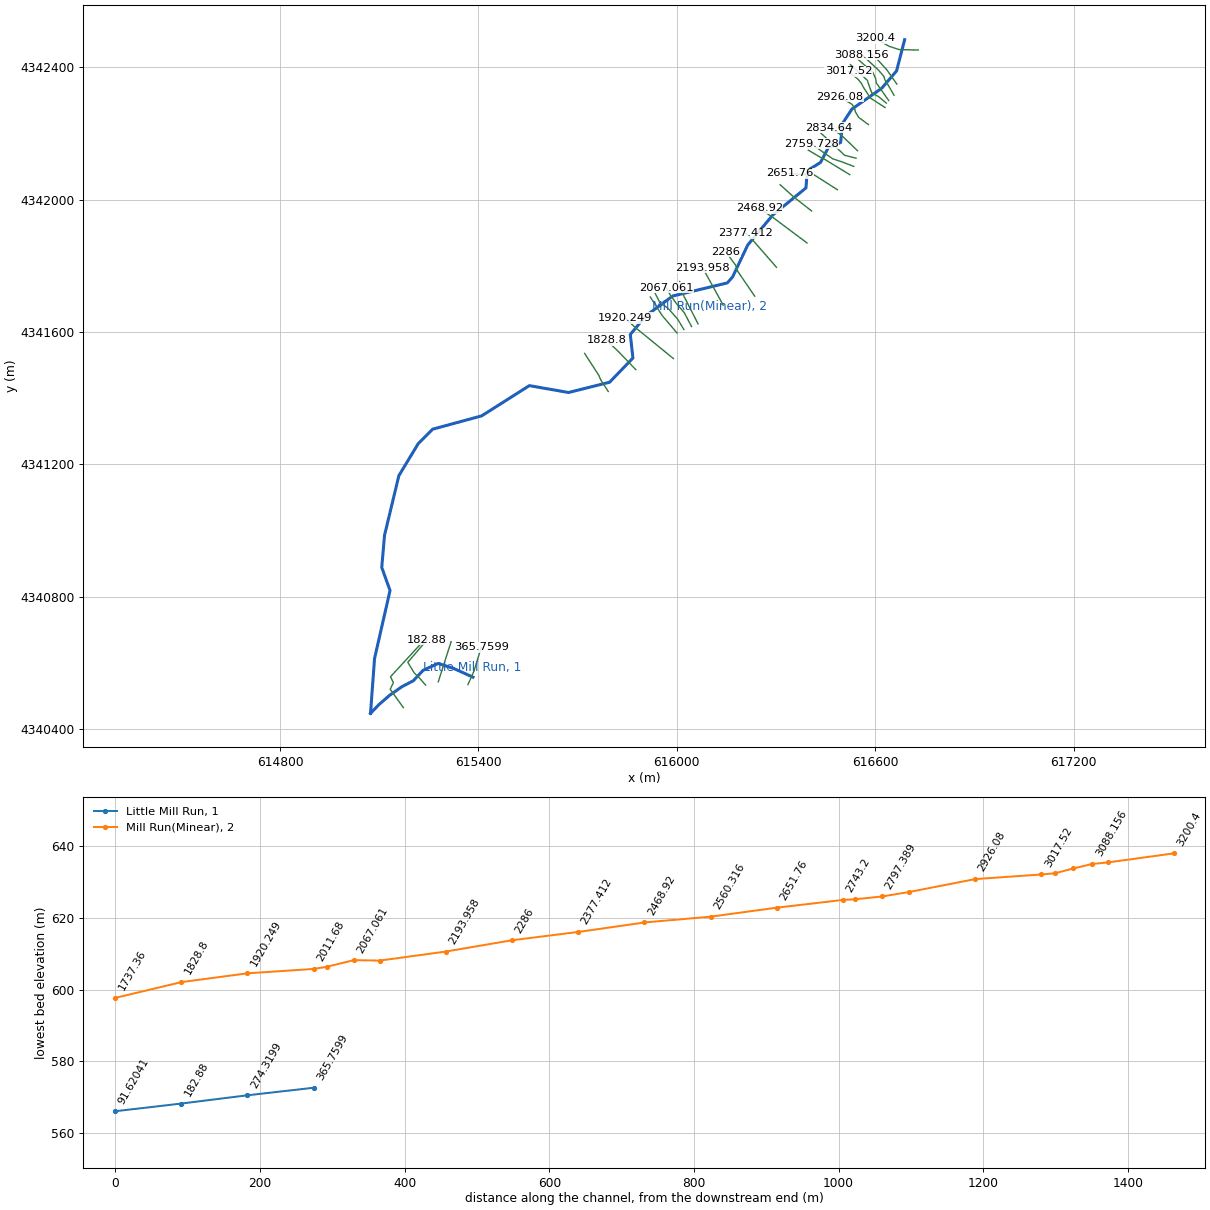
--- MinearRun.prj (project) ---

Proj Title=MinearRun
Current Plan=p01
Default Exp/Contr=0.3,0.1
SI Units
Geom File=g01
Flow File=f01
Plan File=p01
Background Map Layer=Bing Satellite
Y Axis Title=Elevation
X Axis Title(PF)=Main Channel Distance
X Axis Title(XS)=Station
BEGIN DESCRIPTION:
September 2018
Tucker County ABFE Study
US Army Corps of Engineers, Pittsburgh District
NAD 1983 UTM 17N (meters)
END DESCRIPTION:
DSS Export Rating Curves= 0
DSS Export Rating Curve Sorted= 0
DSS Export Volume Flow Curves= 0
DXF OffsetX= 0
DXF OffsetY= 0
DXF ScaleX= 1
DXF ScaleY= 10

--- MinearRun.p01 (plan) ---

Plan Title=MinearRun_plan
Program Version=5.05
Short Identifier=Plan1_subcritical
Geom File=g01
Flow File=f01
Subcritical Flow
K Sum by GR= 0
Std Step Tol= 0.003
Critical Tol= 0.003
Num of Std Step Trials= 20
Max Error Tol= 0.1
Flow Tol Ratio= 0.001
Split Flow NTrial= 30
Split Flow Tol= 0.006
Split Flow Ratio= 0.02
Log Output Level= 0
Friction Slope Method= 1
Unsteady Friction Slope Method= 2
Unsteady Bridges Friction Slope Method= 1
Parabolic Critical Depth
Global Vel Dist= 0 , 0 , 0
Global Log Level= 0
CheckData=True
Encroach Param=-1 ,0,0, 0
Computation Interval=1MIN
Output Interval=1HOUR
Instantaneous Interval=1HOUR
Mapping Interval=1HOUR
Computation Time Step Use Courant=        0
Computation Time Step Use Time Series=    0
Computation Time Step Count To Double=0
Computation Time Step Max Doubling=0
Computation Time Step Max Halving=0
Computation Time Step Residence Courant=0
Run HTab= 0
Run UNet= 0
Run Sediment= 0
Run PostProcess= 0
Run WQNet= 0
Run RASMapper=-1
UNET Theta= 1
UNET Theta Warmup= 1
UNET ZTol= 0.006
UNET ZSATol= 0.006
UNET MxIter= 20
UNET Max Iter WO Improvement= 0
UNET MaxInSteps= 0
UNET DtIC= 0
UNET DtMin= 0
UNET MaxCRTS= 20
UNET WFStab= 2
UNET SFStab= 1
UNET WFX= 1
UNET SFX= 1
UNET 1D Methodology=Finite Difference
UNET DSS MLevel= 4
UNET Pardiso=0
UNET DZMax Abort= 30
UNET Use Existing IB Tables=-1
UNET Froude Reduction=False
UNET Froude Limit= 0.8
UNET Froude Power= 4
UNET D1 Cores= 0
UNET D2 Coriolis=0
UNET D2 Cores= 0
UNET D2 Theta= 1
UNET D2 Theta Warmup= 1
UNET D2 Z Tol= 0.003
UNET D2 Volume Tol= 0.003
UNET D2 Max Iterations= 20
UNET D2 Equation= 0
UNET D2 RampUpFraction=0.1
UNET D2 TimeSlices= 1
UNET D2 BCVolumeCheck=0
UNET D1D2 MaxIter= 0
UNET D1D2 ZTol=0.003
UNET D1D2 QTol=0.1
UNET D1D2 MinQTol=0.03
Write IC File= 0
Write IC File at Fixed DateTime=0
Write IC File at Sim End=0
Echo Input=False
Echo Parameters=False
Echo Output=False
Write Detailed= 0
HDF Write Warmup=0
HDF Write Time Slices=0
HDF Flush=0
HDF Face Node Velocities=0
HDF Compression= 1
HDF Chunk Size= 1
HDF Spatial Parts= 1
HDF Use Max Rows=0
HDF Fixed Rows= 1
Calibration Method= 0
Calibration Iterations= 20
Calibration Max Change=0.05
Calibration Tolerance=0.2
Calibration Maximum=1.5
Calibration Minimum=0.5
Calibration Optimization Method= 1
WQ AD Non Conservative
WQ ULTIMATE=-1
WQ Max Comp Step=1HOUR
WQ Output Interval=15MIN
WQ Output Selected Increments= 0
WQ Output face flow=0
WQ Output face velocity=0
WQ Output face area=0
WQ Output face dispersion=0
WQ Output cell volume=0
WQ Output cell surface area=0
WQ Output cell continuity=0
WQ Output cumulative cell continuity=0
WQ Output face conc=0
WQ Output face dconc_dx=0
WQ Output face courant=0
WQ Output face peclet=0
WQ Output face adv mass=0
WQ Output face disp mass=0
WQ Output cell mass=0
WQ Output cell source sink temp=0
WQ Output nsm pathways=0
WQ Output nsm derived pathways=0
WQ Output MaxMinRange=-1
WQ Daily Max Min Mean=-1
WQ Daily Range=0
WQ Daily Time=0
WQ Create Restart=0
WQ Fixed Restart=0
WQ System Summary=0
WQ Write To DSS=0
WQ Use Fixed Temperature=0
Sorting and Armoring Iterations= 10
XS Update Threshold= 0.02
Bed Roughness Predictor= 0
Hydraulics Update Threshold= 0.02
Energy Slope Method= 1
Volume Change Method= 1
Sediment Retention Method= 0
XS Weighting Method= 0
Number of US Weighted Cross Sections= 1
Number of DS Weighted Cross Sections= 1
Upstream XS Weight=0
Main XS Weight=1
Downstream XS Weight=0
Number of DS XS's Weighted with US Boundary= 1
Upstream Boundary Weight= 1
Weight of XSs Associated with US Boundary= 0
Number of US XS's Weighted with DS Boundary= 1
Downstream Boundary Weight= 0.5
Weight of XSs Associated with DS Boundary= 0.5
Percentile Method= 0
Sediment Output Level= 4
Mass or Volume Output= 0
Output Increment Type= 1
Profile and TS Output Increment= 1
XS Output Flag= 0
XS Output Increment= 10
Write Gradation File= 0
Read Gradation Hotstart= 0
Write HDF5 File= 1
Write Binary Output= 1
Write DSS Sediment File= 0
SV Curve= 0
Specific Gage Flag= 0

--- MinearRun.f01 (steady flow) ---

Flow Title=MinearRun_flow
Program Version=5.05
Number of Profiles= 1
Profile Names=PF 1
River Rch & RM=Little Mill Run,1               ,365.7599
  9.4323
River Rch & RM=Little Mill Run,1               ,91.62041
  9.7409
River Rch & RM=Mill Run(Minear),2               ,3200.4
   14.64
River Rch & RM=Mill Run(Minear),2               ,2286
 16.1121
River Rch & RM=Mill Run(Minear),2               ,1591.275
 17.7262
River Rch & RM=Mill Run(Minear),2               ,1491.988
 19.5384
River Rch & RM=Mill Run(Minear),2               ,731.52
 21.4923
River Rch & RM=Mill Run(Minear),2               ,365.76
 28.0051
River Rch & RM=Mill Run(Minear),1               ,274.2707
   28.26
River Rch & RM=Mill Run(Minear),1               ,19.92903
 28.3732
River Rch & RM=Minear Run,1               ,7376.625
  40.681
River Rch & RM=Minear Run,1               ,6492.24
 41.7386
River Rch & RM=Minear Run,1               ,5303.417
 45.8729
River Rch & RM=Minear Run,1               ,4297.68
 47.7984
River Rch & RM=Minear Run,1               ,4206.24
  53.363
River Rch & RM=Minear Run,1               ,3108.96
 54.8209
River Rch & RM=Minear Run,1               ,692.6317
 60.8806
River Rch & RM=Stump Run,1               ,1828.007
   14.64
River Rch & RM=Stump Run,1               ,1188.022
  16.282
River Rch & RM=Stump Run,1               ,90.74239
 17.9244
River Rch & RM=Stump Run,1               ,2.381145
 17.9527
Boundary for River Rch & Prof#=Little Mill Run,1               , 1
Up Type= 2
Dn Type= 0
Boundary for River Rch & Prof#=Mill Run(Minear),2               , 1
Up Type= 2
Dn Type= 0
Boundary for River Rch & Prof#=Mill Run(Minear),1               , 1
Up Type= 0
Dn Type= 0
Boundary for River Rch & Prof#=Minear Run,1               , 1
Up Type= 0
Dn Type= 1
Dn Known WS=473.2
Boundary for River Rch & Prof#=Stump Run,1               , 1
Up Type= 2
Dn Type= 0
DSS Import GetInterval= 0
DSS Import GetPeak= 0
DSS Import FillOption= 0

--- MinearRun.g01 (geometry) ---

Geom Title=MinearRun_geometry
Program Version=5.05

Junct Name=2
Junct Desc=, 0 , 0 , 0 ,0
Up River,Reach=Little Mill Run ,1
Up River,Reach=Mill Run(Minear),2
Dn River,Reach=Mill Run(Minear),1
Junc L&A=110,
Junc L&A=92,

Junct Name=4
Junct Desc=, 0 , 0 , 0 ,0
Up River,Reach=Mill Run(Minear),1
Up River,Reach=Stump Run       ,1
Dn River,Reach=Minear Run      ,1
Junc L&A=48,
Junc L&A=30,

River Reach=Little Mill Run ,1
Reach XY= 30
     615383.4468    4340557.6386     615372.3886    4340562.6283
     615366.8594    4340565.1231     615364.0949    4340566.3706
     615358.5657    4340568.8654     615350.2721    4340572.6077
     615344.7429    4340575.1025     615341.9784      4340576.35
     615336.4492    4340578.8448      615325.391    4340583.8345
     615303.0682    4340590.9977     615300.2779    4340591.8932
     615277.9551    4340599.0564      615232.603    4340578.3085
     615222.1239    4340567.1335     615213.7405    4340558.1936
     615203.2614    4340547.0186     615187.0864    4340538.5226
     615184.3905    4340537.1067     615168.2155    4340528.6107
     615131.2567    4340502.7564     615126.6454    4340498.7498
     615124.3397    4340496.7466     615117.4228    4340490.7367
     615112.8114    4340486.7302     615105.8945    4340480.7203
     615103.5888    4340478.7171     615098.9775    4340474.7105
     615090.5108    4340465.8911     615073.5775    4340448.2522

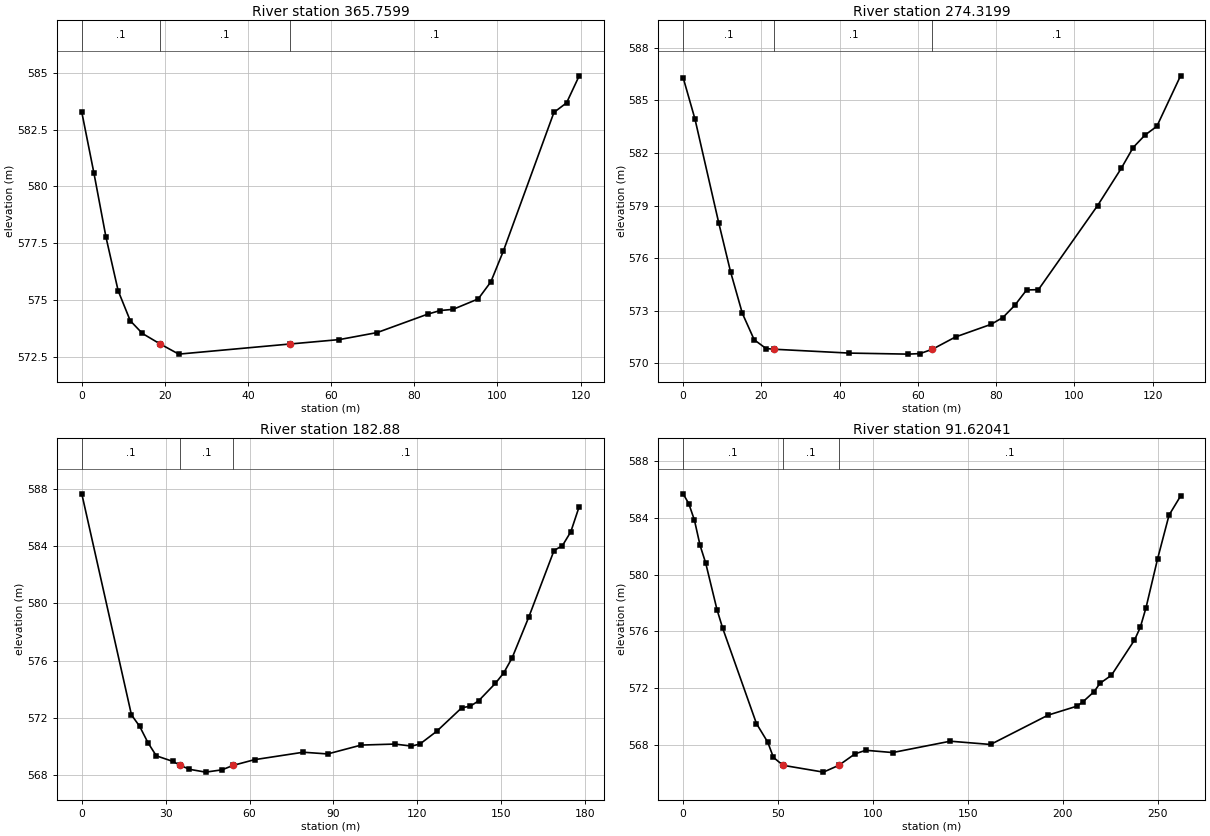
Type RM Length L Ch R = 1 ,365.7599,90.48,91.44,93.1
XS GIS Cut Line= 3
     615368.2423    4340535.2412     615386.2331    4340575.1126
     615408.7141    4340647.6346
#Sta/Elev= 20
       0  583.27    2.92  580.59    5.83  577.76    8.75  575.41   11.66  574.09
   14.58  573.53   18.88 573.064   23.33  572.62   50.02573.0646   61.96  573.26
   71.08  573.57   83.22  574.38   86.26  574.54    89.3  574.59   95.37  575.05
   98.41   575.8  101.45  577.17  113.59  583.26  116.63  583.68  119.67  584.87
#Mann= 3 , 0 , 0
       0      .1       0   18.88      .1       0   50.02      .1       0
Bank Sta=18.88,50.02
XS Rating Curve= 0 ,0
Exp/Cntr=0.3,0.1

Type RM Length L Ch R = 1 ,274.3199,79.6,91.44,105.01
XS GIS Cut Line= 2
     615278.4718    4340543.6429     615317.3164     4340664.694
#Sta/Elev= 24
       0   586.3    3.03  583.93    9.08  578.03   12.11  575.23   15.13  572.85
   18.16  571.34   21.19  570.84   23.25570.7993   42.38  570.58   57.51  570.52
   60.54  570.55   63.72570.7994   69.62   571.5    78.7  572.22   81.73  572.61
   84.75   573.3   87.78  574.18   90.81   574.2  105.94     579     112  581.13
  115.02  582.31  118.05  583.02  121.08  583.52  127.13   586.4
#Mann= 3 , 0 , 0
       0      .1       0   23.25      .1       0   63.72      .1       0
Bank Sta=23.25,63.72
XS Rating Curve= 0 ,0
Exp/Cntr=0.3,0.1

Type RM Length L Ch R = 1 ,182.88  ,91.87,91.26,68.32
XS GIS Cut Line= 5
     615240.2211    4340533.7266     615218.7468    4340558.2034
     615205.9208    4340570.2309     615186.3121    4340602.5184
     615245.0242    4340670.6609
#Sta/Elev= 30
       0  587.65   17.76  572.21   20.72   571.4   23.68  570.26   26.64  569.35
   32.56  568.96   35.26568.6833   38.42  568.41   44.28  568.21   50.14  568.37
   54.15568.6832   61.77  569.08    79.2   569.6   87.92  569.48   99.91   570.1
  111.91  570.17   117.9  570.03   120.9  570.17   126.9  571.06  135.89  572.71
  138.89  572.81  141.89  573.19  147.89  574.41  150.88  575.14  153.88  576.19
  159.88  579.06  168.87  583.69  171.87  584.03  174.87     585  177.87  586.76
#Mann= 3 , 0 , 0
       0      .1       0   35.26      .1       0   54.15      .1       0
Bank Sta=35.26,54.15
XS Rating Curve= 0 ,0
Exp/Cntr=0.3,0.1

Type RM Length L Ch R = 1 ,91.62041,86.59,91.62,15.07
XS GIS Cut Line= 5
     615173.0549    4340465.4925     615133.1301    4340521.0163
     615142.6888    4340541.0688     615134.0899    4340558.9283
     615236.9858    4340670.4119
#Sta/Elev= 30
       0  585.69    2.97     585    5.95  583.84    8.92  582.06   11.89  580.81
   17.84  577.53   20.81  576.23   38.65  569.49    44.6  568.18   47.57  567.11
   52.64566.5518   73.94  566.07   82.07 566.552    90.6  567.36   96.27  567.61
  110.42  567.45  140.77  568.25  162.01  568.02  192.35  570.09  207.52  570.72
  210.55  571.01  216.62  571.75  219.66  572.33  225.72   572.9  237.86  575.38
   240.9  576.27  243.93  577.66     250  581.09  256.07  584.19  262.13  585.53
#Mann= 3 , 0 , 0
       0      .1       0   52.64      .1       0   82.07      .1       0
Bank Sta=52.64,82.07
XS Rating Curve= 0 ,0
Exp/Cntr=0.3,0.1

River Reach=Mill Run(Minear),2
Reach XY= 30
     616689.1265    4342482.9021     616664.7848    4342388.7102
616619.345170091 4342335.8059044616529.8147348624342273.50871633
      616501.272    4342229.9599 616495.638948994342172.54323009
     616457.88024342156.25329303     616434.5968    4342111.9555
616394.4944629354342087.41196037     616390.6759    4342035.2262
     616290.1341    4341953.2052     616214.4631    4341862.7175
616168.726504953 4341766.3325811616152.8301306414341748.39972294
     615987.4501    4341708.7297     615906.4875    4341648.9337
     615859.3509     4341592.557615867.2941212834341521.44045321
615796.6892398164341448.37717633615672.5595908254341417.37586018
615553.9759976154341438.10676294     615409.8472    4341346.8134
      615261.432    4341306.5622     615218.0402    4341263.1705
     615159.3026    4341166.2666     615115.9109    4340985.8866
     615107.5376     4340888.831 615132.622948994340819.43842569
     615085.7483    4340613.8817     615073.5775    4340448.2522

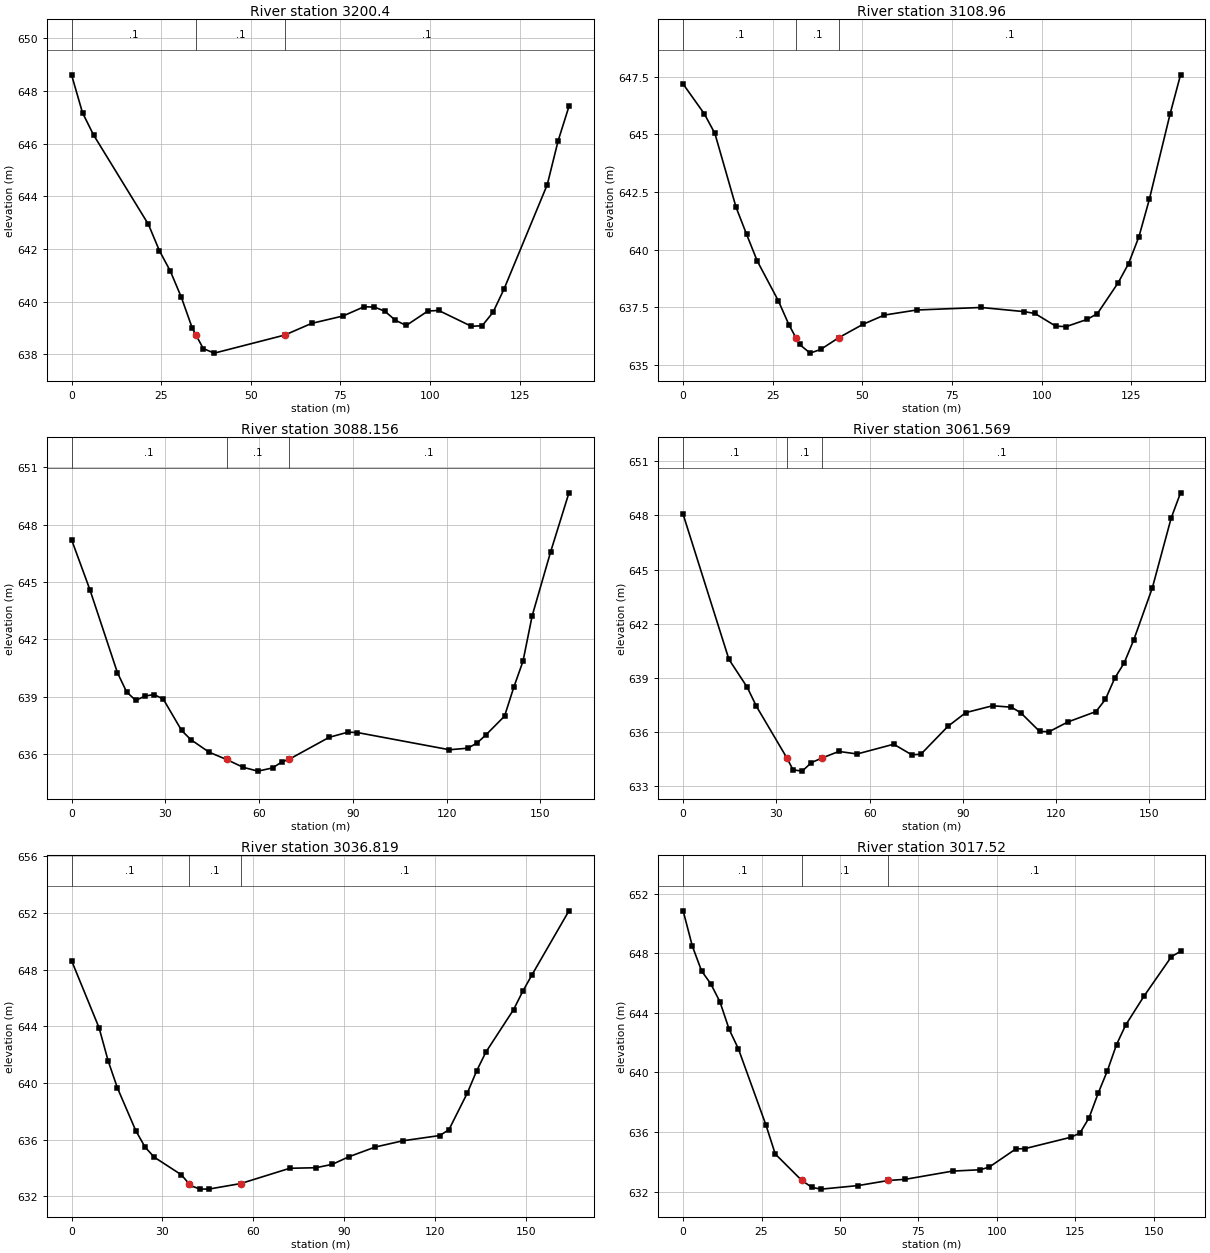
Type RM Length L Ch R = 1 ,3200.4  ,95.36,91.44,67.13
XS GIS Cut Line= 4
     616730.5228    4342451.6801     616672.3172    4342453.1172
     616641.7888    4342463.1383     616599.6644     4342487.048
#Sta/Elev= 28
       0  648.61    3.06  647.17    6.13  646.33   21.45  642.93   24.52  641.93
   27.58  641.15   30.64  640.16   33.71  638.98   34.72638.7258   36.77  638.21
   39.84  638.04   59.49638.7265   66.99  639.17   75.75  639.45   81.59   639.8
   84.51  639.79   87.43  639.63   90.35  639.29   93.38  639.09   99.44  639.64
  102.46  639.66  111.55  639.06  114.57  639.08   117.6  639.59  120.63  640.46
  132.74  644.44  135.76   646.1  138.79  647.41
#Mann= 3 , 0 , 0
       0      .1       0   34.72      .1       0   59.49      .1       0
Bank Sta=34.72,59.49
XS Rating Curve= 0 ,0
Exp/Cntr=0.3,0.1

Type RM Length L Ch R = 1 ,3108.96 ,22.3,20.8,19.58
XS GIS Cut Line= 4
     616665.5313    4342348.8559     616635.0209    4342392.3102
     616604.6387    4342425.4935     616573.8088    4342451.9191
#Sta/Elev= 29
       0  647.18     5.9  645.89    8.85  645.04   14.75  641.84    17.7  640.66
   20.65  639.51   26.55  637.78    29.5  636.74   31.45636.1785   32.45  635.89
    35.4  635.51   38.35  635.67   43.38636.1786   50.15  636.76    56.1  637.16
   65.09  637.38   83.09  637.49   95.09  637.31   98.09  637.23  103.89  636.68
  106.79  636.66  112.59  636.97  115.49  637.22  121.29  638.56  124.19  639.39
  127.09  640.56  129.99  642.18  135.79  645.89  138.69  647.58
#Mann= 3 , 0 , 0
       0      .1       0   31.45      .1       0   43.38      .1       0
Bank Sta=31.45,43.38
XS Rating Curve= 0 ,0
Exp/Cntr=0.3,0.1

Type RM Length L Ch R = 1 ,3088.156,27.01,26.59,20.46
XS GIS Cut Line= 6
     616657.0669    4342315.3245      616634.908    4342353.3584
     616628.9769    4342362.4821     616626.7941    4342371.6764
     616609.0008    4342392.1155     616559.3031    4342438.0649
#Sta/Elev= 30
       0  647.22    5.87   644.6   14.67  640.26   17.61  639.25   20.54   638.8
   23.48  639.03   26.41  639.11   29.35  638.87   35.21  637.23   38.15  636.75
   44.02  636.09   49.58635.7116    54.9   635.3   59.63   635.1   64.35  635.27
   67.36  635.59   69.52 635.712   82.42  636.87   88.44  637.14   91.45  637.12
  120.88  636.22  126.76   636.3  129.71  636.57  132.65  637.01  138.53  637.98
  141.48  639.49  144.42  640.85  147.36  643.23  153.25  646.57  159.13  649.67
#Mann= 3 , 0 , 0
       0      .1       0   49.58      .1       0   69.52      .1       0
Bank Sta=49.58,69.52
XS Rating Curve= 0 ,0
Exp/Cntr=0.3,0.1

Type RM Length L Ch R = 1 ,3061.569,24.51,24.75,27.99
XS GIS Cut Line= 5
     616641.0595    4342299.1584     616603.6209    4342352.0752
     616601.2397     4342366.495     616592.5084     4342384.619
     616547.1323    4342424.5711
#Sta/Elev= 30
       0  648.06   14.73  640.03   20.63  638.48   23.57  637.43   33.37 634.571
   35.36  633.91    38.3  633.84   41.25  634.31   44.75634.5718   50.09  634.93
   55.98  634.79   67.74  635.33   73.59  634.74   76.51  634.78   85.18  636.32
   90.93  637.08   99.55  637.46   105.6  637.38  108.62  637.07  114.67  636.04
  117.69  636.02  123.74  636.56  132.81  637.14  135.83  637.81  138.85  638.99
  141.87  639.83   144.9  641.08  150.94  643.99  156.99  647.85  160.01  649.25
#Mann= 3 , 0 , 0
       0      .1       0   33.37      .1       0   44.75      .1       0
Bank Sta=33.37,44.75
XS Rating Curve= 0 ,0
Exp/Cntr=0.3,0.1

Type RM Length L Ch R = 1 ,3036.819,15.64,19.3,18.67
XS GIS Cut Line= 6
     616633.9158    4342291.3532     616610.6324    4342310.6678
     616589.7303    4342322.3095     616581.3959    4342344.5345
     616576.5011    4342360.0127     616525.3041    4342407.6378
#Sta/Elev= 28
       0  648.63    9.08  643.89    12.1  641.54   15.13  639.65   21.18  636.64
    24.2  635.49   27.23  634.77   36.23  633.52   38.69 632.903   39.22  632.77
   42.21  632.52   45.21  632.51   55.78632.9019   71.98  633.98   80.62  634.02
   86.03  634.26   91.44  634.79   100.2  635.48  109.28  635.92  121.44  636.29
  124.48   636.7  130.57   639.3  133.62  640.85  136.66  642.17   145.8  645.17
  148.85  646.47  151.89  647.63  164.07  652.14
#Mann= 3 , 0 , 0
       0      .1       0   38.69      .1       0   55.78      .1       0
Bank Sta=38.69,55.78
XS Rating Curve= 0 ,0
Exp/Cntr=0.3,0.1

Type RM Length L Ch R = 1 ,3017.52 ,85.98,91.44,84.82
XS GIS Cut Line= 6
     616629.8844    4342278.1644     616585.4343    4342306.7395
       616564.38    4342339.6082     616557.6643    4342352.1118
      616548.276    4342363.2623     616519.2884    4342387.7021
#Sta/Elev= 30
       0  650.84    2.94  648.47    5.87  646.81    8.81  645.94   11.74  644.73
   14.68  642.88   17.61  641.58   26.42  636.45   29.36  634.52   37.83632.7421
    41.1  632.27   44.04  632.16   55.85   632.4   65.42632.7413   70.86  632.82
   85.87  633.37   94.71  633.46   97.58  633.64  106.07  634.86  108.98  634.88
  123.56  635.64  126.48  635.92   129.4  636.95  132.31   638.6  135.23   640.1
  138.15  641.86  141.06  643.17   146.9  645.11  155.64  647.76  158.56  648.12
#Mann= 3 , 0 , 0
       0      .1       0   37.83      .1       0   65.42      .1       0
Bank Sta=37.83,65.42
XS Rating Curve= 0 ,0
Exp/Cntr=0.3,0.1

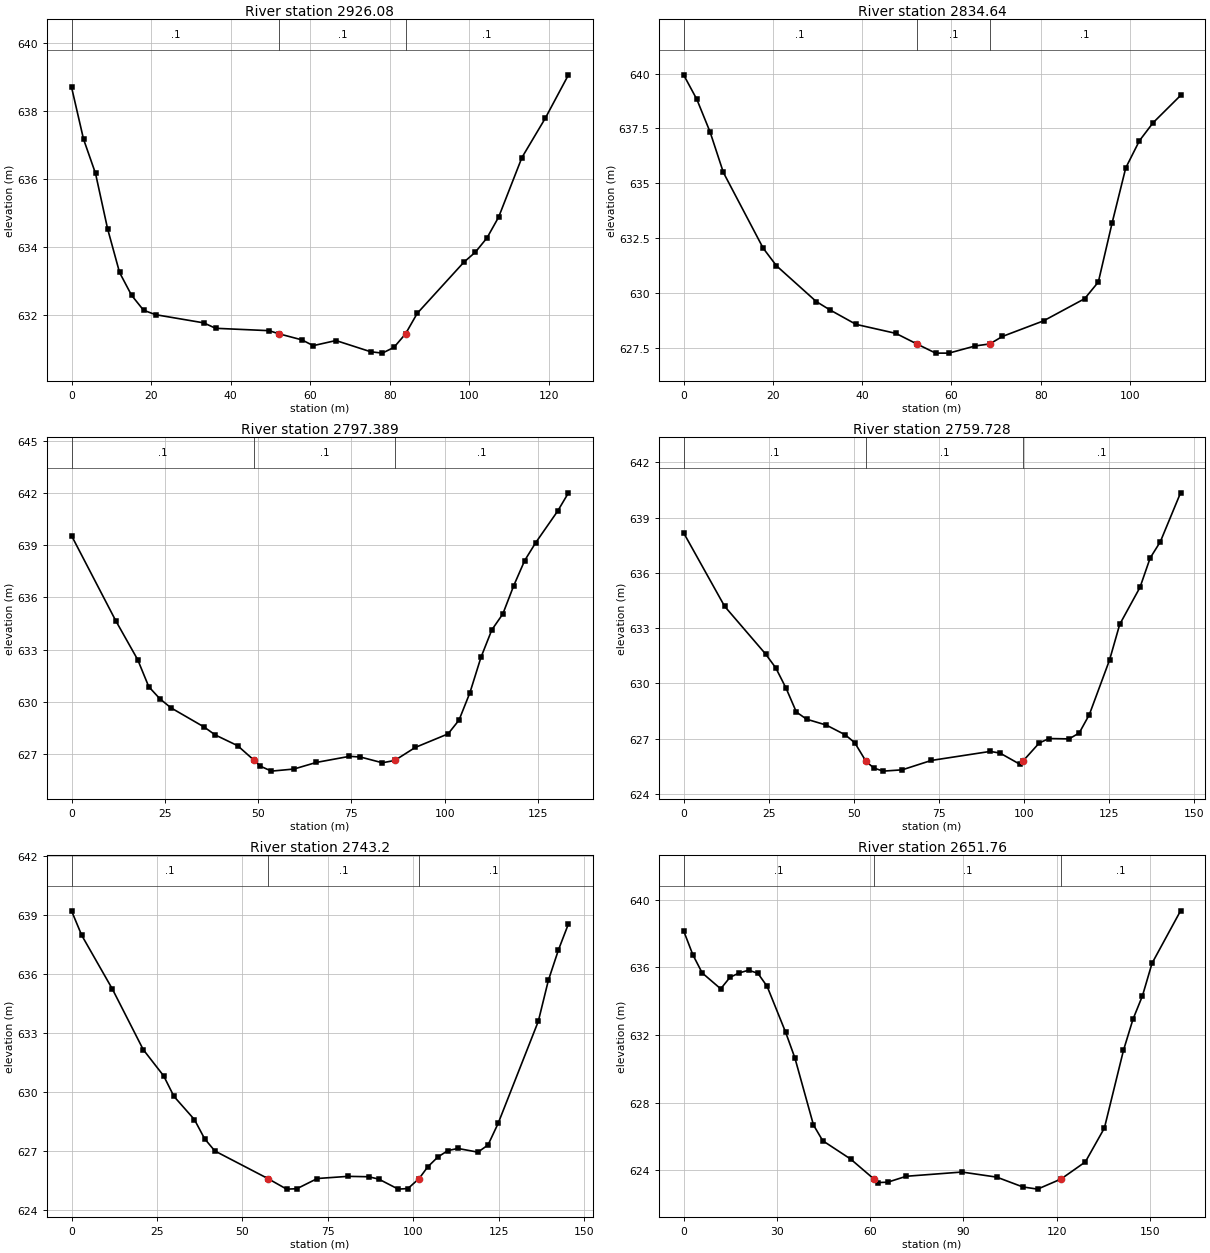
Type RM Length L Ch R = 1 ,2926.08 ,79.97,91.44,92.65
XS GIS Cut Line= 6
     616579.5978    4342226.6504      616550.377     4342248.079
     616540.6111    4342264.1682     616537.7176    4342275.2158
     616530.2686    4342287.7666      616492.603    4342310.2594
#Sta/Elev= 27
       0  638.69    3.02  637.16    6.04  636.15    9.06  634.53   12.08  633.24
    15.1  632.57   18.12  632.13   21.14     632   33.22  631.76   36.24   631.6
   49.68  631.53   52.16631.4378   57.91  631.26   60.77  631.09   66.48  631.24
   75.23  630.91   78.15  630.87   81.07  631.04   83.98631.4373   86.92  632.04
   98.62  633.54  101.55  633.84  104.47  634.26  107.39  634.87  113.24  636.62
  119.09  637.77  124.94  639.05
#Mann= 3 , 0 , 0
       0      .1       0   52.16      .1       0   83.98      .1       0
Bank Sta=52.16,83.98
XS Rating Curve= 0 ,0
Exp/Cntr=0.3,0.1

Type RM Length L Ch R = 1 ,2834.64 ,37.58,37.25,35.42
XS GIS Cut Line= 4
     616546.8956     4342147.311     616497.6551    4342194.7104
     616487.4705     4342201.585     616460.7952    4342216.7664
#Sta/Elev= 24
       0  639.94    2.97  638.82    5.94  637.33    8.91  635.49   17.83  632.04
    20.8  631.24   29.72  629.61   32.69  629.24   38.63  628.57   47.55  628.16
   52.25627.6786   56.46  627.26   59.43  627.26   65.38  627.59   68.59 627.679
   71.42  628.02   80.63  628.73   89.84  629.74   92.91   630.5   95.98  633.18
   99.05   635.7  102.12  636.94  105.19  637.76  111.33     639
#Mann= 3 , 0 , 0
       0      .1       0   52.25      .1       0   68.59      .1       0
Bank Sta=52.25,68.59
XS Rating Curve= 0 ,0
Exp/Cntr=0.3,0.1

Type RM Length L Ch R = 1 ,2797.389,35.87,37.66,38.57
XS GIS Cut Line= 5
     616542.0611    4342125.0622     616507.6652    4342133.7935
      616483.588    4342156.5477     616462.4743    4342176.9206
     616436.1217    4342200.2569
#Sta/Elev= 30
       0  639.55   11.83  634.67   17.74  632.42    20.7  630.87   23.66  630.18
   26.62  629.66   35.49  628.56    38.5   628.1   44.52  627.48   48.98626.6313
   50.54  626.31   53.56  626.02   59.58  626.14    65.6  626.52   74.48  626.87
   77.42  626.83   83.28   626.5   86.59626.6317   92.09  627.38  100.89  628.16
  103.82  628.95  106.75  630.53  109.69  632.55  112.62  634.14  115.56  635.05
  118.49  636.68  121.42  638.12  124.35  639.14  130.22  640.95  133.15  642.01
#Mann= 3 , 0 , 0
       0      .1       0   48.98      .1       0   86.59      .1       0
Bank Sta=48.98,86.59
XS Rating Curve= 0 ,0
Exp/Cntr=0.3,0.1

Type RM Length L Ch R = 1 ,2759.728,14.97,16.53,17.53
XS GIS Cut Line= 5
     616535.0231    4342100.2442     616498.5106     4342114.373
     616471.9993    4342122.9455     616436.3598    4342147.5122
     616407.2291    4342168.2291
#Sta/Elev= 30
       0  638.17   12.05  634.18   24.09  631.59    27.1  630.83   30.12  629.73
   33.13  628.44   36.14  628.05   41.94  627.73   47.51   627.2    50.3  626.77
   53.58625.7693   55.87   625.4   58.65  625.23   64.23   625.3   72.79  625.81
    90.1   626.3   92.99  626.21   98.76  625.61    99.7625.7699  104.53  626.76
  107.41     627  113.28  626.98  116.26   627.3  119.24   628.3  125.19  631.27
  128.17   633.2  134.13  635.21  137.11   636.8  140.09  637.68  146.05  640.34
#Mann= 3 , 0 , 0
       0      .1       0   53.58      .1       0    99.7      .1       0
Bank Sta=53.58,99.7
XS Rating Curve= 0 ,0
Exp/Cntr=0.3,0.1

Type RM Length L Ch R = 1 ,2743.2  ,68.06,91.44,88.43
XS GIS Cut Line= 4
      616523.083    4342075.3442     616446.3258    4342122.2157
     616435.9115    4342126.8102     616397.9044    4342149.2522
#Sta/Elev= 30
       0  639.21       3  637.96   11.99  635.22   20.99  632.15   26.98  630.81
   29.98  629.77   35.97  628.59   38.97  627.61   41.97  626.99   57.52 625.584
   62.96  625.05   65.95  625.07   71.95  625.59   80.94   625.7   86.94  625.68
   89.94  625.56   95.63  625.05   98.47  625.08  101.72625.5839  104.26  626.18
   107.2  626.68  110.15  627.01  113.09  627.12  118.97  626.93  121.92   627.3
  124.86  628.39  136.63  633.59  139.57  635.67  142.52  637.22  145.46  638.55
#Mann= 3 , 0 , 0
       0      .1       0   57.52      .1       0  101.72      .1       0
Bank Sta=57.52,101.72
XS Rating Curve= 0 ,0
Exp/Cntr=0.3,0.1

Type RM Length L Ch R = 1 ,2651.76 ,93.46,91.44,76.63
XS GIS Cut Line= 6
     616485.8429    4342029.7696     616410.3962    4342077.9301
     616390.8263    4342077.3519     616383.9301    4342075.5047
     616377.0663    4342075.2868     616340.5553    4342079.4686
#Sta/Elev= 30
       0  638.16    2.98  636.74    5.97  635.67   11.93  634.73   14.92  635.41
    17.9  635.67   20.89  635.83   23.87  635.65   26.85  634.88   32.82  632.16
    35.8  630.64   41.77  626.68   44.75  625.75    53.7  624.67   61.22623.4871
   62.66  623.28   65.64   623.3   71.61  623.65   89.51   623.9   100.7   623.6
  109.09  623.02  113.85  622.89  121.39623.4874  129.22   624.5  135.34   626.5
  141.47  631.09  144.53  632.93  147.59  634.32  150.66  636.24  159.84  639.34
#Mann= 3 , 0 , 0
       0      .1       0   61.22      .1       0  121.39      .1       0
Bank Sta=61.22,121.39
XS Rating Curve= 0 ,0
Exp/Cntr=0.3,0.1

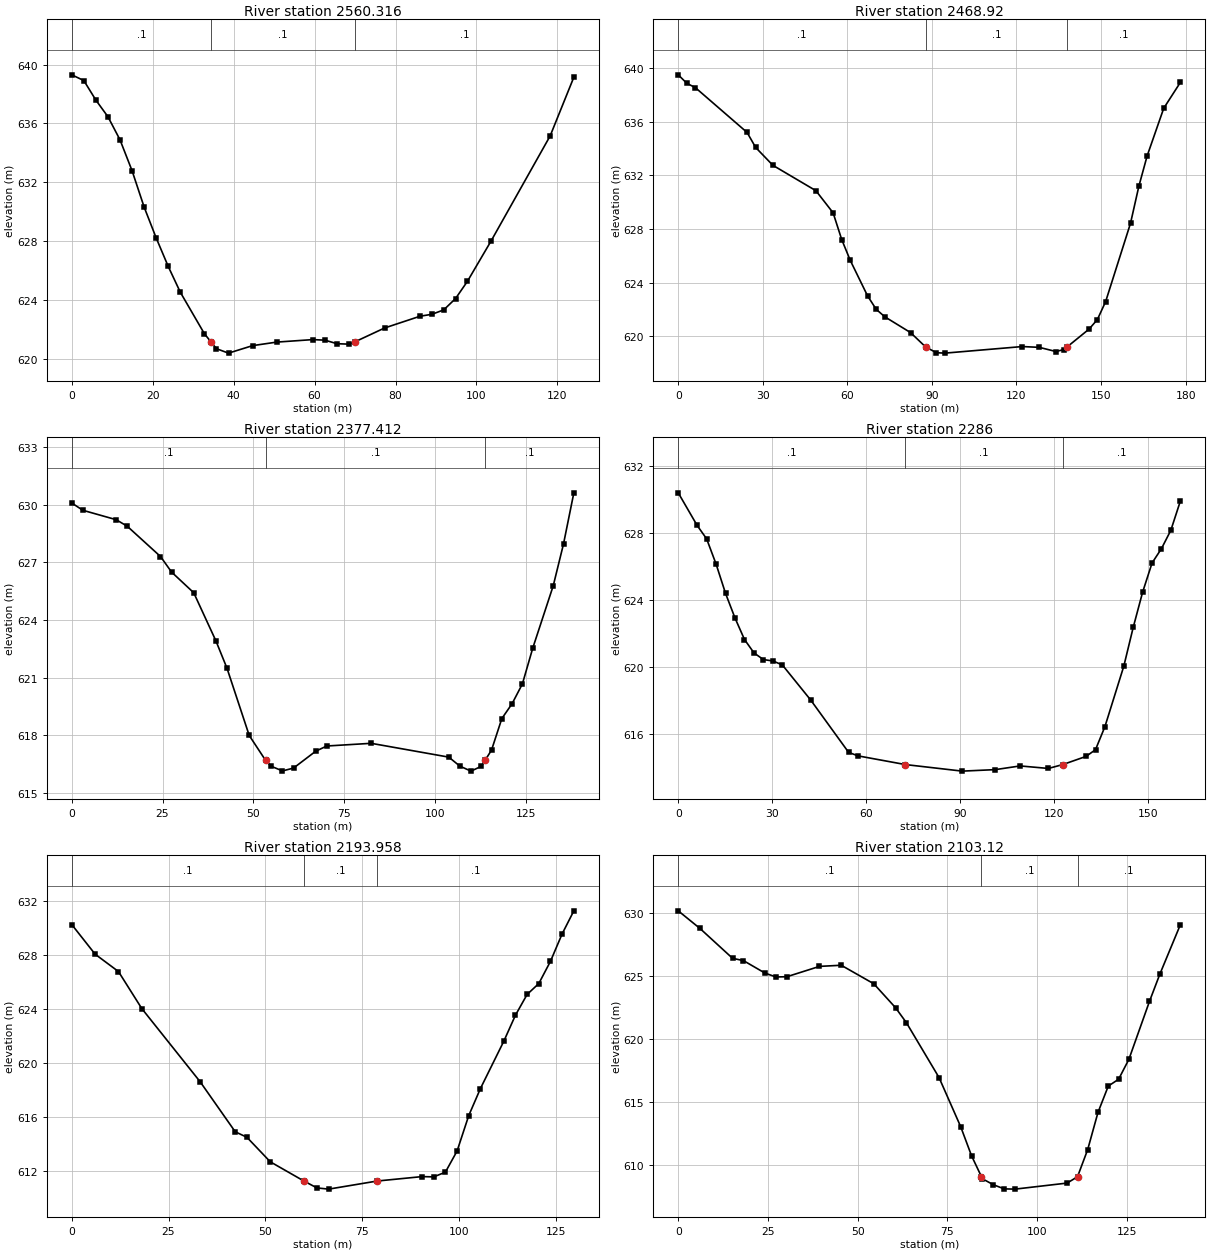
Type RM Length L Ch R = 1 ,2560.316,88.9,91.4,90.97
XS GIS Cut Line= 3
     616407.7906     4341965.608     616353.8284    4342007.8496
     616312.5404    4342044.9832
#Sta/Elev= 30
       0   639.3    2.98  638.91    5.96  637.58    8.94  636.45   11.92  634.88
    14.9  632.78   17.88  630.31   20.86  628.21   23.84  626.27   26.82  624.52
   32.77   621.7   34.39621.1455   35.75  620.68   38.73  620.38   44.69  620.89
   50.65  621.13   59.59   621.3   62.57  621.26   65.55  621.02   68.53  620.99
   69.95621.1456    77.3  622.09   86.07  622.89   88.99  623.02   91.91  623.32
   94.83  624.09   97.76  625.26   103.6     628  118.21  635.15  124.06  639.14
#Mann= 3 , 0 , 0
       0      .1       0   34.39      .1       0   69.95      .1       0
Bank Sta=34.39,69.95
XS Rating Curve= 0 ,0
Exp/Cntr=0.3,0.1

Type RM Length L Ch R = 1 ,2468.92 ,95.43,91.51,94.03
XS GIS Cut Line= 3
        616393.9    4341869.0349     616293.6344      4341943.94
     616249.7018    4341973.5456
#Sta/Elev= 30
       0  639.49    3.05  638.86    6.11  638.53   24.42   635.2   27.47  634.08
   33.58  632.75   48.84  630.86   54.95  629.21      58  627.22   61.05  625.66
   67.16  623.03   70.21  622.03   73.26  621.47   82.42  620.29   87.73619.2277
   91.58  618.79   94.63  618.76   122.1  619.25   128.1  619.19  133.99  618.88
  136.93  619.03  138.01619.2284  145.76  620.55   148.7  621.26  151.64   622.6
  160.47  628.44  163.42  631.19  166.36  633.45  172.25     637  178.13  638.92
#Mann= 3 , 0 , 0
       0      .1       0   87.73      .1       0  138.01      .1       0
Bank Sta=87.73,138.01
XS Rating Curve= 0 ,0
Exp/Cntr=0.3,0.1

Type RM Length L Ch R = 1 ,2377.412,95.29,91.41,88.71
XS GIS Cut Line= 3
     616301.5337    4341795.5423     616229.1695    4341878.3525
     616208.7708    4341898.0166
#Sta/Elev= 30
       0   630.1    3.05  629.72   12.22  629.23   15.27  628.89   24.44  627.31
   27.49   626.5    33.6  625.42   39.71  622.91   42.77  621.48   48.88  617.98
    53.4 616.679   54.99  616.37   58.04  616.13    61.1  616.28   67.21  617.16
   70.26  617.43   82.48  617.57  103.86  616.85  106.92  616.38  109.97  616.12
  112.81  616.37  113.85616.6793  115.64  617.22  118.47  618.86  121.31  619.64
  124.14  620.67  126.97  622.52  132.64  625.79  135.47  627.97  138.31  630.63
#Mann= 3 , 0 , 0
       0      .1       0    53.4      .1       0  113.85      .1       0
Bank Sta=53.4,113.85
XS Rating Curve= 0 ,0
Exp/Cntr=0.3,0.1

Type RM Length L Ch R = 1 ,2286    ,90.33,92.04,91.18
XS GIS Cut Line= 4
     616235.6524    4341708.2297     616184.5484    4341783.1115
     616178.6789    4341800.6348     616148.6035    4341841.9883
#Sta/Elev= 30
       0  630.42    6.04  628.47    9.07  627.67   12.09  626.16   15.11  624.41
   18.13  622.94   21.15  621.66   24.18  620.86    27.2  620.46   30.22  620.38
   33.24  620.14   42.31  618.04   54.39  614.92   57.42  614.71   72.47614.1927
   90.66   613.8  101.22  613.89  109.14  614.11  118.16  613.96  122.77614.1929
  130.19  614.68   133.2  615.08  136.21  616.46  142.22  620.06  145.23  622.38
  148.24  624.49  151.25  626.23  154.26  627.09  157.26  628.19  160.27  629.92
#Mann= 3 , 0 , 0
       0      .1       0   72.47      .1       0  122.77      .1       0
Bank Sta=72.47,122.77
XS Rating Curve= 0 ,0
Exp/Cntr=0.3,0.1

Type RM Length L Ch R = 1 ,2193.958,92.79,90.84,90.43
XS GIS Cut Line= 2
     616140.4022    4341681.2421     616077.6958    4341794.7486
#Sta/Elev= 25
       0  630.28    6.03  628.08   12.06  626.79   18.09  624.04   33.17   618.6
   42.22  614.89   45.24  614.48   51.27  612.66   59.96611.2316   63.33  610.72
   66.35  610.63   78.87611.2314   90.47  611.56   93.49  611.54    96.5  611.89
   99.52  613.46  102.53  616.09  105.55   618.1  111.58  621.61   114.6  623.55
  117.61  625.09  120.63   625.9  123.64  627.55  126.66  629.59  129.68   631.3
#Mann= 3 , 0 , 0
       0      .1       0   59.96      .1       0   78.87      .1       0
Bank Sta=59.96,78.87
XS Rating Curve= 0 ,0
Exp/Cntr=0.3,0.1

Type RM Length L Ch R = 1 ,2103.12 ,33.33,36.06,37.5
XS GIS Cut Line= 3
      616064.202    4341624.8858     616020.0474    4341711.1727
     616008.6194    4341752.6743
#Sta/Elev= 30
       0  630.21    6.06  628.81   15.15  626.44   18.17  626.26   24.23  625.26
   27.26  624.96   30.29  624.98   39.38   625.8   45.44  625.89   54.52  624.42
   60.58  622.52   63.61  621.33    72.7  616.98   78.75  613.07   81.78  610.76
   84.54609.1022   84.81  608.94   87.84  608.47   90.87  608.14    93.9  608.12
  108.41   608.6  111.31609.1028  114.15  611.26  117.02  614.21  119.89   616.3
  122.76  616.84  125.63  618.42  131.37  623.02  134.23  625.16  139.97   629.1
#Mann= 3 , 0 , 0
       0      .1       0   84.54      .1       0  111.31      .1       0
Bank Sta=84.54,111.31
XS Rating Curve= 0 ,0
Exp/Cntr=0.3,0.1

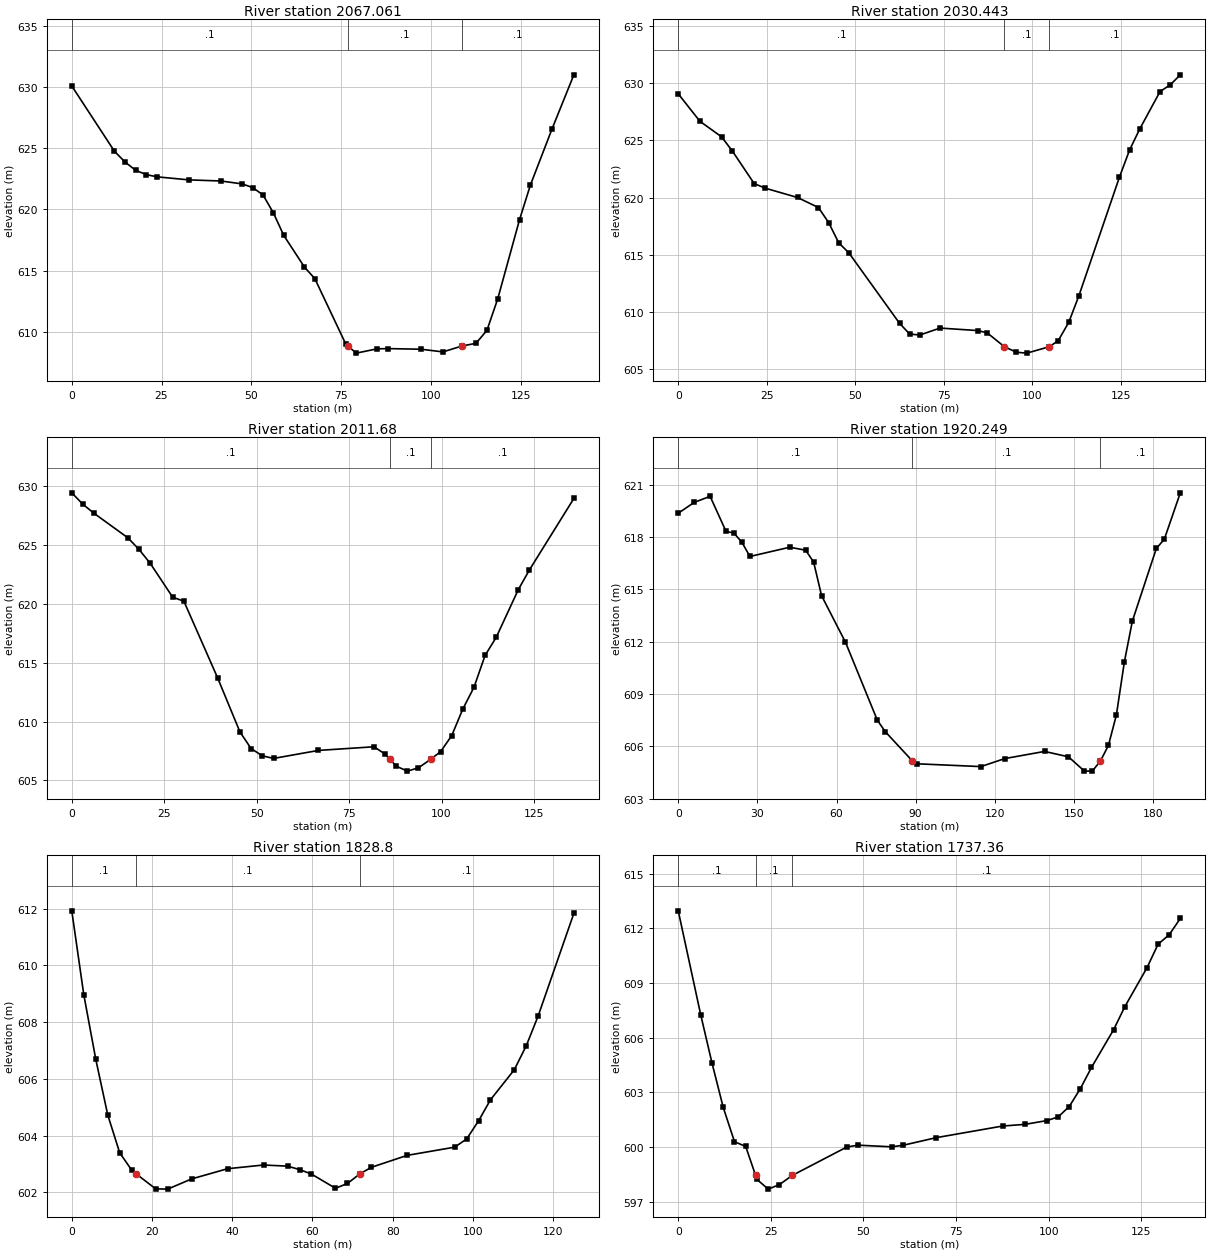
Type RM Length L Ch R = 1 ,2067.061,31.92,36.62,37.95
XS GIS Cut Line= 5
     616044.5647    4341616.7382     616022.4058    4341658.7409
     615997.9318    4341687.1836     615980.1551    4341712.1041
     615968.9103    4341733.5354
#Sta/Elev= 30
       0  630.11   11.87  624.77   14.84  623.88   17.81   623.2   20.78  622.85
   23.74  622.67   32.65  622.42   41.55  622.33   47.49  622.09   50.38  621.79
   53.26  621.19   56.15  619.72   59.03  617.88   64.81  615.28   67.69  614.34
   76.35  608.96   76.89608.8255   79.24  608.24   85.01  608.59   88.07  608.61
   97.26  608.56  103.38  608.34  108.71608.8264  112.56  609.04  115.62   610.1
  118.65   612.7   124.7  619.16  127.72  621.99  133.78  626.61  139.83  631.02
#Mann= 3 , 0 , 0
       0      .1       0   76.89      .1       0  108.71      .1       0
Bank Sta=76.89,108.71
XS Rating Curve= 0 ,0
Exp/Cntr=0.3,0.1

Type RM Length L Ch R = 1 ,2030.443,25.42,18.76,17.25
XS GIS Cut Line= 6
     616021.4302    4341607.5935     616002.5124     4341639.079
      615976.054    4341669.1093     615963.8832    4341679.0311
     615948.9342    4341688.6885     615934.6466    4341716.7343
#Sta/Elev= 30
       0  629.07    6.12  626.67   12.24  625.31    15.3  624.06   21.43  621.23
   24.49  620.83   33.67  620.01   39.59  619.13   42.45  617.82   45.31  616.05
   48.17  615.17   62.46  609.02   65.32  608.08   68.18  607.99    73.9   608.6
   84.61  608.38   87.22  608.18   92.06606.9738   95.42  606.49   98.39  606.41
   104.8 606.973  107.29  607.51  110.25  609.11  113.12  611.44  124.56   621.8
  127.42  624.17  130.28     626  136.01  629.27  138.87  629.85  141.73  630.73
#Mann= 3 , 0 , 0
       0      .1       0   92.06      .1       0   104.8      .1       0
Bank Sta=92.06,104.8
XS Rating Curve= 0 ,0
Exp/Cntr=0.3,0.1

Type RM Length L Ch R = 1 ,2011.68 ,86.01,91.43,93.06
XS GIS Cut Line= 3
     616000.7019    4341597.1045     615955.4715    4341650.1881
     615919.8794    4341705.8001
#Sta/Elev= 30
       0  629.44    3.03  628.46    6.06  627.69   15.16  625.62   18.19  624.63
   21.23  623.44   27.29  620.57   30.32  620.23   39.42  613.73   45.48  609.12
   48.51   607.7   51.55  607.09   54.58  606.87   66.71  607.55   81.74  607.86
   84.75  607.23   85.99606.8084   87.75  606.21   90.75  605.79   93.75  606.07
   97.11606.8069   99.75  607.45  102.75  608.81  105.75  611.07  108.76  612.91
  111.76  615.62  114.76  617.15  120.76  621.22  123.76  622.89  135.77  628.96
#Mann= 3 , 0 , 0
       0      .1       0   85.99      .1       0   97.11      .1       0
Bank Sta=85.99,97.11
XS Rating Curve= 0 ,0
Exp/Cntr=0.3,0.1

Type RM Length L Ch R = 1 ,1920.249,93.78,91.45,89.78
XS GIS Cut Line= 3
     615989.6423    4341519.9518     615872.6015    4341615.2785
     615843.8515    4341642.1699
#Sta/Elev= 30
       0  619.36    6.04  619.98   12.08  620.33   18.11  618.32   21.13  618.22
   24.15  617.69   27.17  616.88   42.27  617.41    48.3  617.24   51.32  616.56
   54.34  614.63    63.4  611.96   75.47  607.49   78.49  606.83   88.78  605.15
   90.57  604.99  114.72  604.83  123.78  605.29  138.87   605.7  147.93  605.39
  153.98  604.57  157.01  604.58  160.03  605.15  163.06  606.04  166.09  607.79
  169.12  610.84  172.15  613.18  181.23  617.34  184.26  617.87  190.32  620.53
#Mann= 3 , 0 , 0
       0      .1       0   88.78      .1       0  160.03      .1       0
Bank Sta=88.78,160.03
XS Rating Curve= 0 ,0
Exp/Cntr=0.3,0.1

Type RM Length L Ch R = 1 ,1828.8  ,95.48,91.44,88.85
XS GIS Cut Line= 3
     615875.8838    4341486.4373     615824.1715    4341540.3501
     615787.3799    4341574.8744
#Sta/Elev= 28
       0  611.92    2.99  608.97    5.98  606.69    8.96  604.73   11.95  603.39
   14.94  602.78   16.04602.6476   20.92  602.12   23.91  602.11   29.88  602.47
   38.85  602.83   47.81  602.96   53.79  602.92   56.78   602.8   59.76  602.64
   65.74  602.14   68.73  602.31   71.81602.6472    74.7  602.88   83.61   603.3
   95.48  603.59   98.45  603.88  101.42  604.52  104.38  605.26  110.32  606.32
  113.29  607.16  116.25  608.21  125.16  611.83
#Mann= 3 , 0 , 0
       0      .1       0   16.04      .1       0   71.81      .1       0
Bank Sta=16.04,71.81
XS Rating Curve= 0 ,0
Exp/Cntr=0.3,0.1

Type RM Length L Ch R = 1 ,1737.36 ,92.75,91.44,88.33
XS GIS Cut Line= 4
     615792.6457    4341420.4994     615771.0469    4341453.5546
     615763.5456    4341470.0554     615721.1458    4341535.4724
#Sta/Elev= 29
       0  612.96    6.07  607.26    9.11  604.62   12.15  602.18   15.19   600.3
   18.22  600.04   20.89598.4503   21.26  598.23    24.3   597.7   27.34  597.95
   30.78  598.45   45.53  600.01   48.55  600.11   57.61  600.02   60.61   600.1
   69.61  600.52    87.6  601.16   93.59  601.25   99.59  601.46  102.59  601.66
  105.58  602.23  108.58  603.21  111.58  604.37  117.58  606.45  120.58   607.7
  126.57  609.84  129.57  611.13  132.57  611.65  135.57  612.54
#Mann= 3 , 0 , 0
       0      .1       0   20.89      .1       0   30.78      .1       0
Bank Sta=20.89,30.78
XS Rating Curve= 0 ,0
Exp/Cntr=0.3,0.1