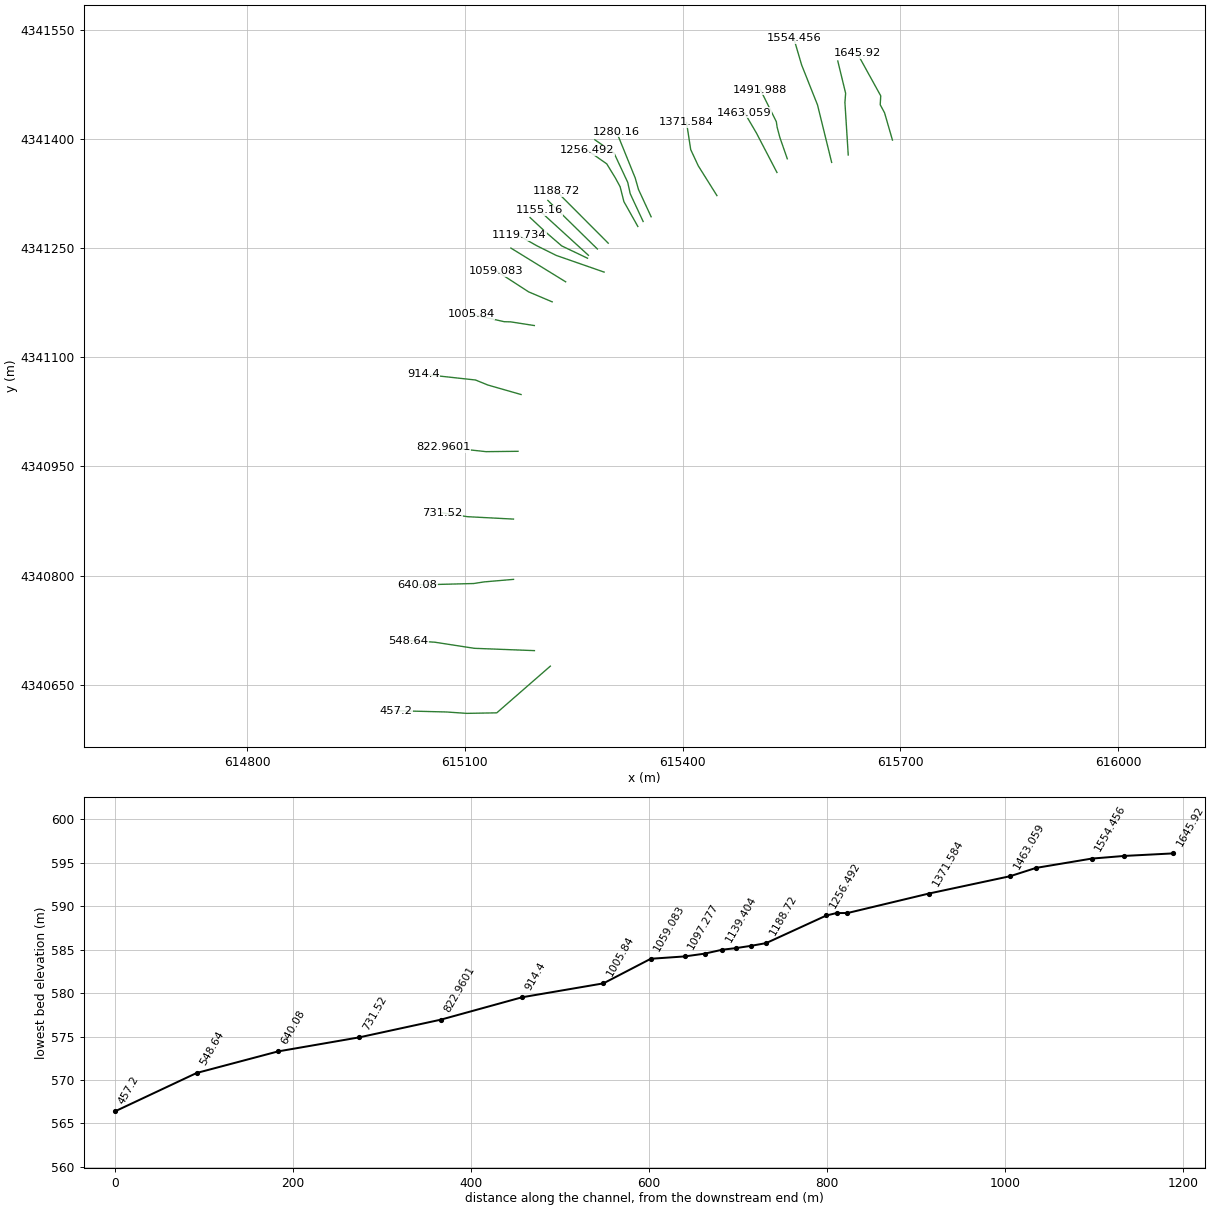
HEC-RAS study MinearRun.prj: MinearRun

--- MinearRun.g01 (geometry) --- (continued)

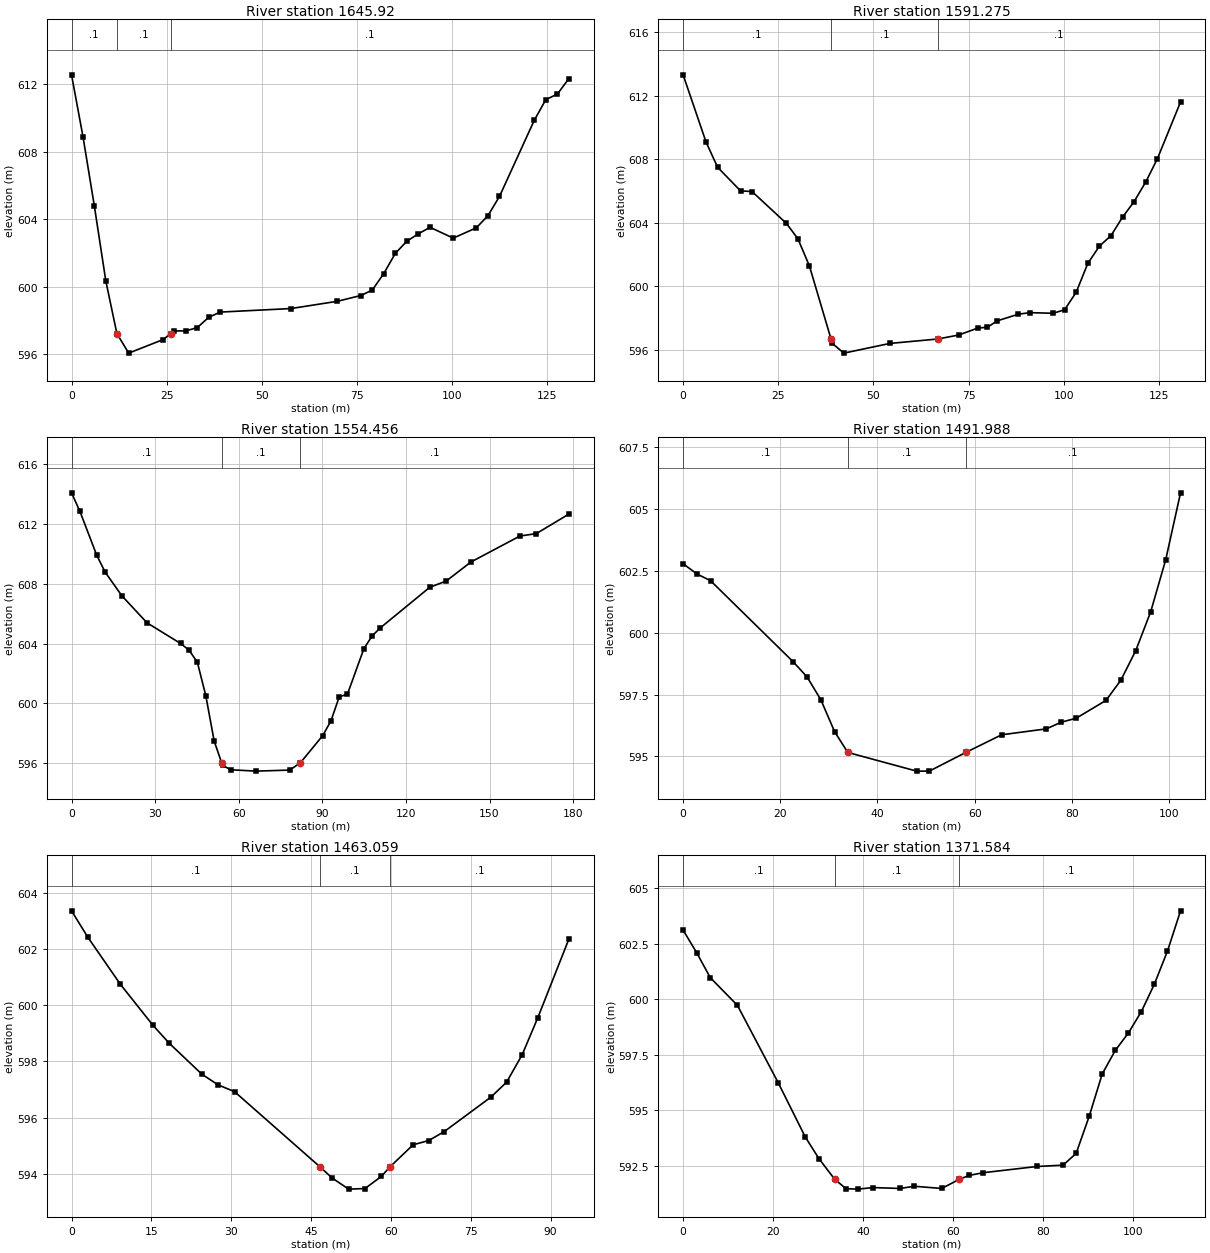
Type RM Length L Ch R = 1 ,1645.92 ,54.04,54.65,48.73
XS GIS Cut Line= 5
     615688.9707    4341398.2952     615678.0866    4341435.8353
      615672.131    4341446.8198     615672.8311    4341459.0833
     615640.3894    4341517.6742
#Sta/Elev= 30
       0  612.55    3.01  608.89    6.01  604.77    9.02  600.34   11.93 597.227
   15.03  596.07   24.05  596.87   26.13597.2224   27.06  597.38   30.07  597.39
   33.07  597.58   36.08  598.19   39.09   598.5   57.72  598.71   69.95  599.14
   76.04  599.48   79.09   599.8   82.13  600.78   85.17  601.98   88.22   602.7
   91.26  603.14   94.31  603.52   100.4  602.88  106.48  603.49  109.53  604.21
  112.57  605.35   121.7  609.85  124.75  611.08  127.79  611.41  130.84  612.33
#Mann= 3 , 0 , 0
       0      .1       0   11.93      .1       0   26.13      .1       0
Bank Sta=11.93,26.13
XS Rating Curve= 0 ,0
Exp/Cntr=0.3,0.1

Type RM Length L Ch R = 1 ,1591.275,35.03,36.82,41.31
XS GIS Cut Line= 4
     615628.0884    4341377.7909     615623.5007    4341450.0155
     615624.4929    4341462.5833     615613.6706    4341506.9548
#Sta/Elev= 30
       0  613.31    6.03  609.07    9.05  607.49   15.08     606   18.09  605.96
   27.14  603.95   30.15  602.98   33.17  601.27   38.85596.6667    39.2  596.39
   42.22  595.78   54.28  596.39   66.84596.6683   72.37  596.92   77.41  597.36
   79.93  597.41   82.46  597.81   88.02  598.23   91.07  598.33   97.16  598.29
   100.2  598.51  103.25  599.62  106.29  601.43  109.34  602.52  112.38  603.18
  115.43  604.35  118.47  605.33  121.51  606.56  124.56  608.02  130.65   611.6
#Mann= 3 , 0 , 0
       0      .1       0   38.85      .1       0   66.84      .1       0
Bank Sta=38.85,66.84
XS Rating Curve= 0 ,0
Exp/Cntr=0.3,0.1

Type RM Length L Ch R = 1 ,1554.456,61.83,62.47,64.13
XS GIS Cut Line= 4
     615605.2416    4341367.6573      615585.766    4341446.5857
     615563.8777    4341501.4719     615553.1186    4341538.0493
#Sta/Elev= 30
       0  614.09    3.01  612.85    9.03  609.92   12.04  608.79   18.07   607.2
    27.1  605.39   39.14  604.01   42.15  603.57   45.16  602.75   48.18  600.52
   51.19  597.48   53.88596.0233    54.2  595.85   57.21  595.56   66.24  595.47
   78.28  595.54   82.11596.0229   90.16  597.85   93.11  598.84   96.07  600.44
   99.02  600.62  104.93  603.67  107.89  604.52  110.84  605.06  128.57  607.77
  134.48  608.19  143.32  609.46  160.92   611.2  166.78  611.36  178.51  612.67
#Mann= 3 , 0 , 0
       0      .1       0   53.88      .1       0   82.11      .1       0
Bank Sta=53.88,82.11
XS Rating Curve= 0 ,0
Exp/Cntr=0.3,0.1

Type RM Length L Ch R = 1 ,1491.988,28.15,28.93,31.79
XS GIS Cut Line= 5
     615544.1256    4341372.6248     615533.8399    4341402.0531
     615530.1886    4341415.8644     615529.0245    4341423.5902
      615507.064    4341467.5111
#Sta/Elev= 21
       0  602.79    2.83  602.38    5.67   602.1   22.67  598.82   25.51  598.21
   28.34  597.29   31.17     596   33.88595.1567   48.06   594.4   50.67   594.4
    58.2595.1578   65.55  595.87   74.76  596.11   77.83  596.38   80.89  596.54
   87.03  597.26    90.1  598.08   93.17  599.28   96.24  600.85   99.31  602.94
  102.38  605.66
#Mann= 3 , 0 , 0
       0      .1       0   33.88      .1       0    58.2      .1       0
Bank Sta=33.88,58.2
XS Rating Curve= 0 ,0
Exp/Cntr=0.3,0.1

Type RM Length L Ch R = 1 ,1463.059,91.19,91.47,91.46
XS GIS Cut Line= 3
     615529.8903    4341353.8218      615501.548    4341408.1225
     615485.2282    4341435.8734
#Sta/Elev= 22
       0  603.36    3.06  602.42    9.19  600.74   15.31  599.28   18.38  598.64
    24.5  597.54   27.56  597.16   30.63  596.92   46.63594.2505      49  593.84
   52.06  593.45   55.13  593.47   58.19   593.9   59.86594.2493   64.18  595.03
   67.11  595.18   70.03   595.5   78.81  596.73   81.74  597.26   84.67  598.24
   87.59  599.55   93.45  602.36
#Mann= 3 , 0 , 0
       0      .1       0   46.63      .1       0   59.86      .1       0
Bank Sta=46.63,59.86
XS Rating Curve= 0 ,0
Exp/Cntr=0.3,0.1

Type RM Length L Ch R = 1 ,1371.584,91.92,91.42,89.33
XS GIS Cut Line= 4
     615447.2079    4341322.0717     615421.5115    4341362.9356
     615411.1193    4341385.2128     615405.3335    4341422.4795
#Sta/Elev= 28
       0  603.12    3.02   602.1    6.03  600.98   12.07  599.73   21.12  596.25
   27.15   593.8   30.17  592.83   33.68 591.897    36.2  591.47   38.87  591.45
   42.24  591.52   48.27  591.48   51.34  591.58   57.49  591.48   61.41591.8962
   63.64  592.07   66.71  592.19   78.66  592.47   84.46  592.53   87.36  593.06
   90.26  594.73   93.16  596.64   96.06   597.7   98.96  598.48  101.86  599.45
  104.76  600.69  107.67  602.18  110.57  603.99
#Mann= 3 , 0 , 0
       0      .1       0   33.68      .1       0   61.41      .1       0
Bank Sta=33.68,61.41
XS Rating Curve= 0 ,0
Exp/Cntr=0.3,0.1

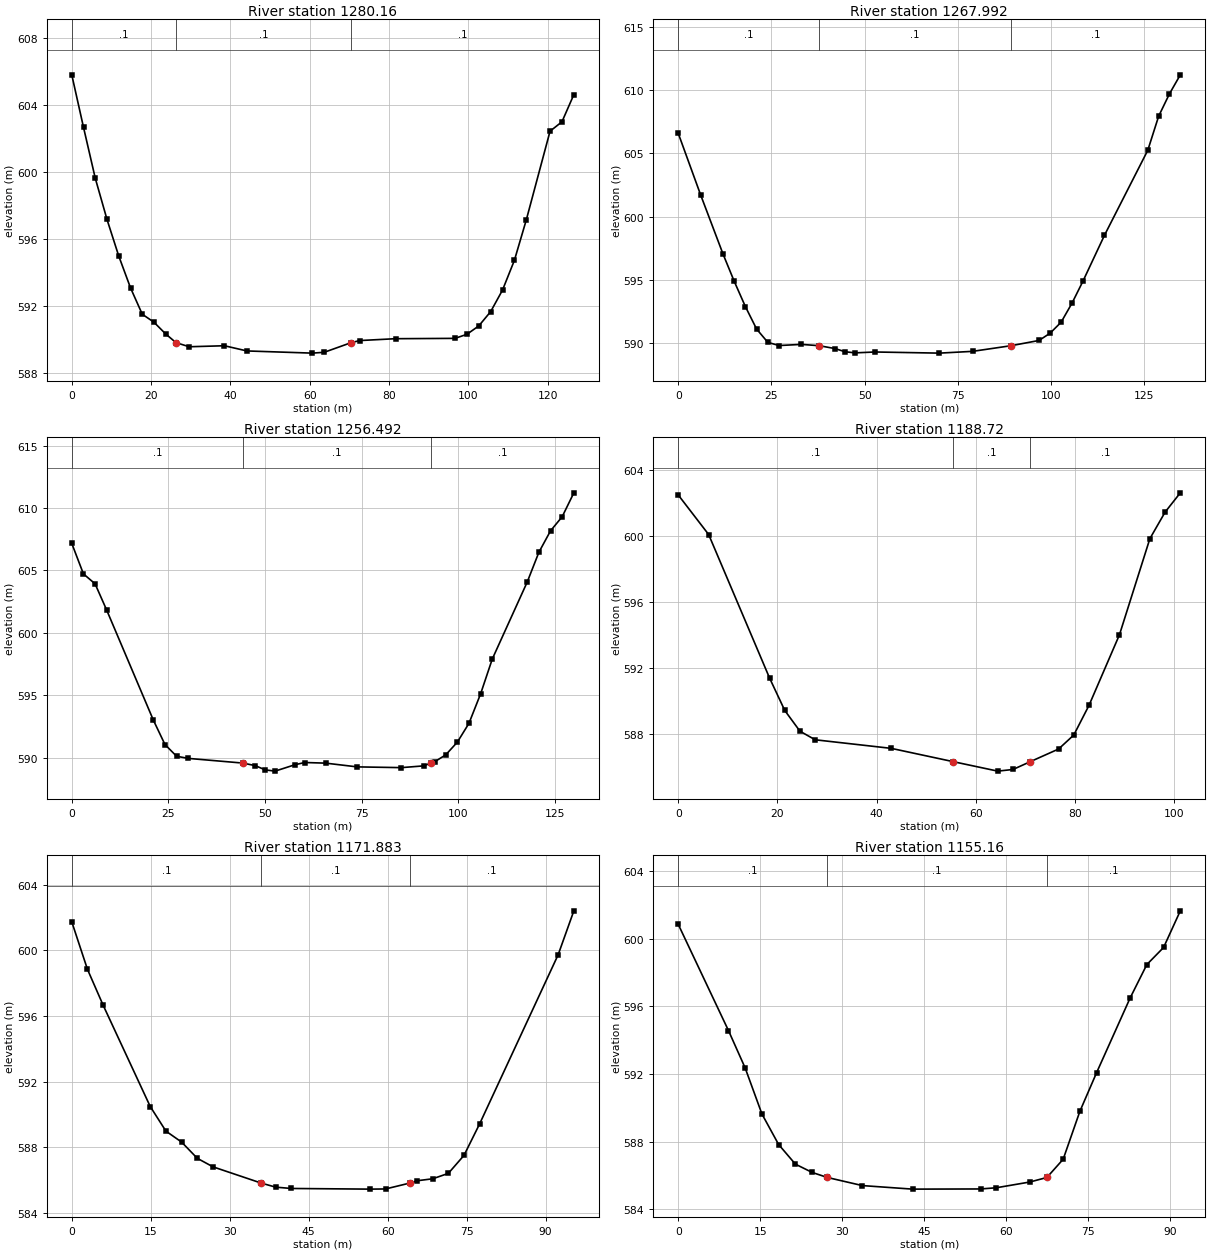
Type RM Length L Ch R = 1 ,1280.16 ,12.82,12.17,12.25
XS GIS Cut Line= 4
     615356.5879    4341292.9675     615339.1373    4341330.5705
     615334.7182    4341346.1461      615308.788    4341410.0052
#Sta/Elev= 28
       0   605.8    2.96  602.67    5.92  599.64    8.88  597.18   11.84     595
   14.81   593.1   17.77  591.53   20.73  591.05   23.69  590.35   26.27589.8358
   29.61  589.59   38.49  589.65   44.15  589.34   60.64  589.21   63.64  589.26
   70.45589.8365   72.63  589.96   81.62  590.07    96.6  590.09    99.6  590.33
  102.59  590.83  105.59  591.68  108.59  592.97  111.58  594.74  114.58  597.15
  120.57  602.44  123.57     603  126.57  604.62
#Mann= 3 , 0 , 0
       0      .1       0   26.27      .1       0   70.45      .1       0
Bank Sta=26.27,70.45
XS Rating Curve= 0 ,0
Exp/Cntr=0.3,0.1

Type RM Length L Ch R = 1 ,1267.992,11.78,11.5,12.51
XS GIS Cut Line= 5
     615345.5948    4341286.4769     615327.8147     4341324.577
     615324.3222    4341340.2932     615305.4309    4341380.6158
     615279.0784    4341398.7134
#Sta/Elev= 27
       0  606.58    6.01  601.71   12.01  597.04   15.02  594.88   18.02  592.88
   21.02  591.11   24.03  590.06   27.03  589.81   33.04   589.9   37.84 589.796
   42.04  589.57   44.73  589.32   47.41  589.23   52.78   589.3   70.02  589.21
   78.92  589.35   89.24 589.796   96.74  590.21    99.7  590.78  102.67  591.65
  105.58  593.15  108.49  594.87   114.3  598.52  125.92  605.24  128.83  607.93
  131.73   609.7  134.64   611.2
#Mann= 3 , 0 , 0
       0      .1       0   37.84      .1       0   89.24      .1       0
Bank Sta=37.84,89.24
XS Rating Curve= 0 ,0
Exp/Cntr=0.3,0.1

Type RM Length L Ch R = 1 ,1256.492,61.35,67.77,71.18
XS GIS Cut Line= 6
     615338.2923    4341279.6506     615319.0835    4341313.7819
     615313.8976    4341334.2078     615307.4418    4341346.1141
     615295.4896    4341365.6369     615268.2904    4341384.5811
#Sta/Elev= 30
       0  607.17    3.01  604.73    6.03  603.93    9.04  601.82   21.09  593.02
    24.1  591.06   27.11  590.12   30.13  589.95   44.29589.5731   47.45  589.37
   50.01  589.03   52.57  588.93   57.69  589.44   60.25  589.62   65.67  589.57
    73.8  589.27   85.24  589.21   90.96  589.35    92.9589.5731   93.83  589.68
   96.69  590.23    99.7  591.25  102.71  592.76  105.73  595.13  108.74  597.91
  117.78  604.08  120.79  606.46  123.81  608.18  126.82  609.31  129.83  611.22
#Mann= 3 , 0 , 0
       0      .1       0   44.29      .1       0    92.9      .1       0
Bank Sta=44.29,92.9
XS Rating Curve= 0 ,0
Exp/Cntr=0.3,0.1

Type RM Length L Ch R = 1 ,1188.72 ,16.7,16.84,16.91
XS GIS Cut Line= 2
     615297.4999    4341256.7018      615225.898    4341328.3039
#Sta/Elev= 18
       0  602.49    6.14  600.09   18.41   591.4   21.48  589.43   24.55  588.17
   27.62  587.65   42.96  587.13   55.41586.3271   64.44  585.75   67.51  585.85
   71.03586.3276   76.71  587.09   79.78  587.94   82.85  589.74   88.99  594.02
   95.12  599.84   98.19  601.45  101.26  602.62
#Mann= 3 , 0 , 0
       0      .1       0   55.41      .1       0   71.03      .1       0
Bank Sta=55.41,71.03
XS Rating Curve= 0 ,0
Exp/Cntr=0.3,0.1

Type RM Length L Ch R = 1 ,1171.883,16.29,16.72,16.96
XS GIS Cut Line= 2
     615282.5145    4341248.7437     615214.3576    4341315.4188
#Sta/Elev= 21
       0  601.75    2.98  598.85    5.96  596.66    14.9  590.48   17.88  588.98
   20.86  588.31   23.84  587.32   26.82   586.8   35.95585.8119   38.73  585.56
   41.71  585.48   56.61  585.44   59.59  585.45   64.23585.8127   65.55  585.95
   68.53  586.07   71.51   586.4   74.49   587.5   77.47  589.43   92.37  599.74
   95.35  602.42
#Mann= 3 , 0 , 0
       0      .1       0   35.95      .1       0   64.23      .1       0
Bank Sta=35.95,64.23
XS Rating Curve= 0 ,0
Exp/Cntr=0.3,0.1

Type RM Length L Ch R = 1 ,1155.16 ,15.43,15.76,15.93
XS GIS Cut Line= 2
     615270.2378    4341240.0654     615202.2926    4341301.8721
#Sta/Elev= 21
       0  600.86    9.19  594.57   12.25  592.35   15.31  589.63   18.37  587.82
   21.43  586.66   24.49  586.17   27.28585.8701   33.68  585.39   42.86  585.18
   55.31  585.19   58.17  585.26    64.3   585.6   67.44585.8691   70.42  586.95
   73.48  589.79   76.54  592.08   82.67   596.5   85.73  598.48   88.79  599.49
   91.85  601.66
#Mann= 3 , 0 , 0
       0      .1       0   27.28      .1       0   67.44      .1       0
Bank Sta=27.28,67.44
XS Rating Curve= 0 ,0
Exp/Cntr=0.3,0.1

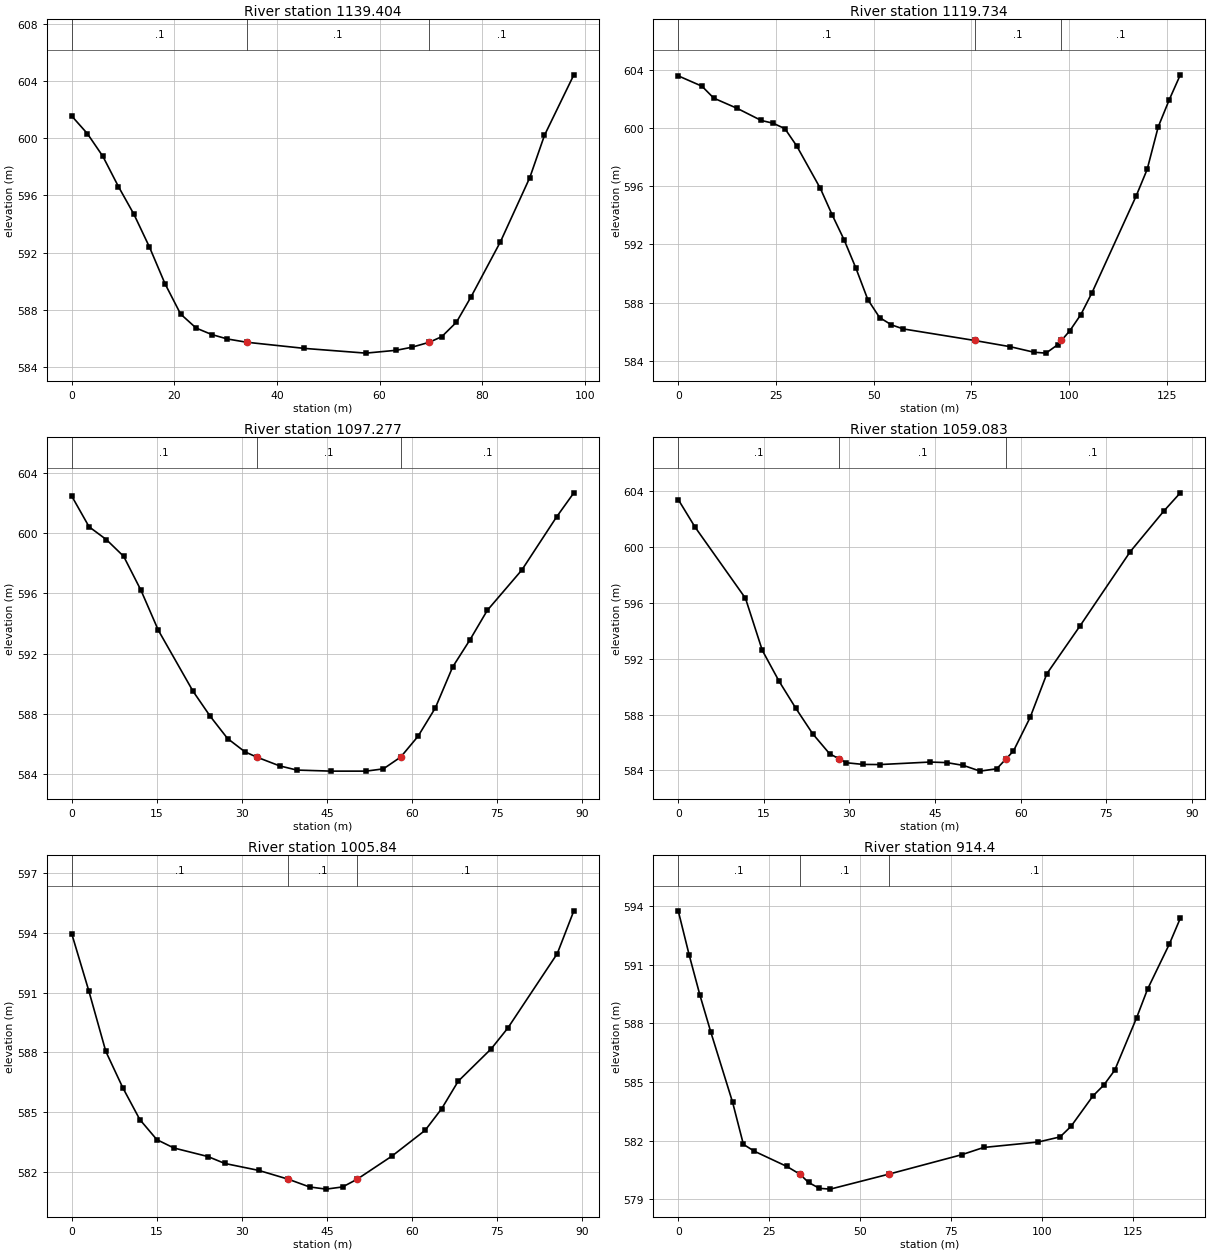
Type RM Length L Ch R = 1 ,1139.404,16.76,19.67,21.22
XS GIS Cut Line= 4
     615268.9678    4341236.0437     615233.4077     4341252.977
     615210.7593    4341272.4504     615189.8043    4341291.9238
#Sta/Elev= 24
       0  601.54    3.03  600.32    6.06  598.73    9.09  596.62   12.12  594.68
   15.15  592.39   18.18  589.83   21.21  587.72   24.24  586.74   27.27  586.29
    30.3  585.98   34.11585.7491   45.36  585.32   57.31  584.99   63.28  585.19
   66.27   585.4   69.69585.7491   72.12  586.14   74.98  587.15   77.84  588.93
   83.56  592.77   89.28  597.25   92.14   600.2   97.86  604.42
#Mann= 3 , 0 , 0
       0      .1       0   34.11      .1       0   69.69      .1       0
Bank Sta=34.11,69.69
XS Rating Curve= 0 ,0
Exp/Cntr=0.3,0.1

Type RM Length L Ch R = 1 ,1119.734,24.5,22.46,22.14
XS GIS Cut Line= 4
     615291.8278    4341216.9936     615225.9993    4341239.8537
     615198.6943    4341253.4004     615174.1409    4341267.3704
#Sta/Elev= 30
       0  603.57    6.06  602.86    9.09  602.04   15.15  601.33   21.21  600.51
   24.24  600.32   27.27  599.95    30.3  598.76   36.36  595.84   39.39  594.02
   42.42  592.32   45.45  590.37   48.48  588.22   51.51  586.98   54.54  586.48
   57.57   586.2   75.79585.4094   84.93  584.98   91.02   584.6   94.07  584.54
   97.12  585.13   98.02585.4103  100.17  586.08  102.99  587.19  105.82  588.68
  117.12  595.32  119.94  597.15  122.77  600.07  125.59  601.93  128.42  603.64
#Mann= 3 , 0 , 0
       0      .1       0   75.79      .1       0   98.02      .1       0
Bank Sta=75.79,98.02
XS Rating Curve= 0 ,0
Exp/Cntr=0.3,0.1

Type RM Length L Ch R = 1 ,1097.277,38.37,38.19,38.11
XS GIS Cut Line= 2
     615238.8481    4341203.6705     615163.4417    4341249.9726
#Sta/Elev= 25
       0  602.44    3.05  600.41     6.1  599.56    9.15  598.45   12.21  596.19
   15.26  593.55   21.36  589.52   24.41  587.85   27.46  586.38   30.51   585.5
   32.59585.1522   36.62  584.57   39.67  584.29   45.77  584.22   51.87  584.22
   54.92  584.37   57.98585.1545   61.03  586.53   64.08  588.41   67.13  591.12
   70.18  592.92   73.23  594.87   79.33  597.55   85.44  601.06   88.49  602.66
#Mann= 3 , 0 , 0
       0      .1       0   32.59      .1       0   57.98      .1       0
Bank Sta=32.59,57.98
XS Rating Curve= 0 ,0
Exp/Cntr=0.3,0.1

Type RM Length L Ch R = 1 ,1059.083,48.38,53.24,54.83
XS GIS Cut Line= 3
     615220.3227    4341176.1243     615187.7789    4341189.8826
     615143.5934    4341218.4577
#Sta/Elev= 25
       0  603.39    2.94  601.42   11.78  596.32   14.72   592.6   17.67  590.38
   20.61  588.44   23.56  586.62    26.5   585.2   28.22584.8197   29.44  584.55
   32.39  584.43   35.33  584.42    44.1   584.6   47.03  584.56   49.95  584.36
   52.87  583.95    55.8  584.12   57.41584.8203   58.72  585.39   61.64  587.79
   64.57  590.92   70.41  594.36   79.18  599.66   85.03  602.55   87.95  603.87
#Mann= 3 , 0 , 0
       0      .1       0   28.22      .1       0   57.41      .1       0
Bank Sta=28.22,57.41
XS Rating Curve= 0 ,0
Exp/Cntr=0.3,0.1

Type RM Length L Ch R = 1 ,1005.84 ,92.73,91.44,89.95
XS GIS Cut Line= 4
     615195.7337      4341143.57     615163.1251    4341148.6348
     615154.1927     4341148.861      615108.739    4341159.1432
#Sta/Elev= 23
       0  593.96       3   591.1       6  588.05       9  586.22      12  584.62
      15  583.61      18  583.19      24  582.76      27  582.41      33  582.06
    38.2581.6171   41.93  581.23   44.85  581.12   47.76  581.23   50.32581.6171
    56.5  582.79   62.32  584.08   65.24  585.17   68.15  586.55   73.97  588.18
   76.89  589.22   85.62  592.97   88.54  595.12
#Mann= 3 , 0 , 0
       0      .1       0    38.2      .1       0   50.32      .1       0
Bank Sta=38.2,50.32
XS Rating Curve= 0 ,0
Exp/Cntr=0.3,0.1

Type RM Length L Ch R = 1 ,914.4   ,90.46,91.44,93.19
XS GIS Cut Line= 4
     615177.4587    4341048.8242     615131.5531    4341061.9401
     615114.7488    4341068.7747     615043.1222     4341076.593
#Sta/Elev= 25
       0  593.75    2.98  591.51    5.97  589.43    8.95  587.55   14.92  583.97
    17.9  581.81   20.89  581.46   29.84  580.68    33.4580.2872   35.81  579.86
   38.79  579.56   41.77  579.52   57.89580.2877   77.89  581.28    83.9  581.65
   98.91  581.93  104.91  582.19  107.91  582.73  113.92  584.28  116.92  584.84
  119.92   585.6  125.93  588.28  128.93  589.74  134.93  592.05  137.94  593.37
#Mann= 3 , 0 , 0
       0      .1       0    33.4      .1       0   57.89      .1       0
Bank Sta=33.4,57.89
XS Rating Curve= 0 ,0
Exp/Cntr=0.3,0.1

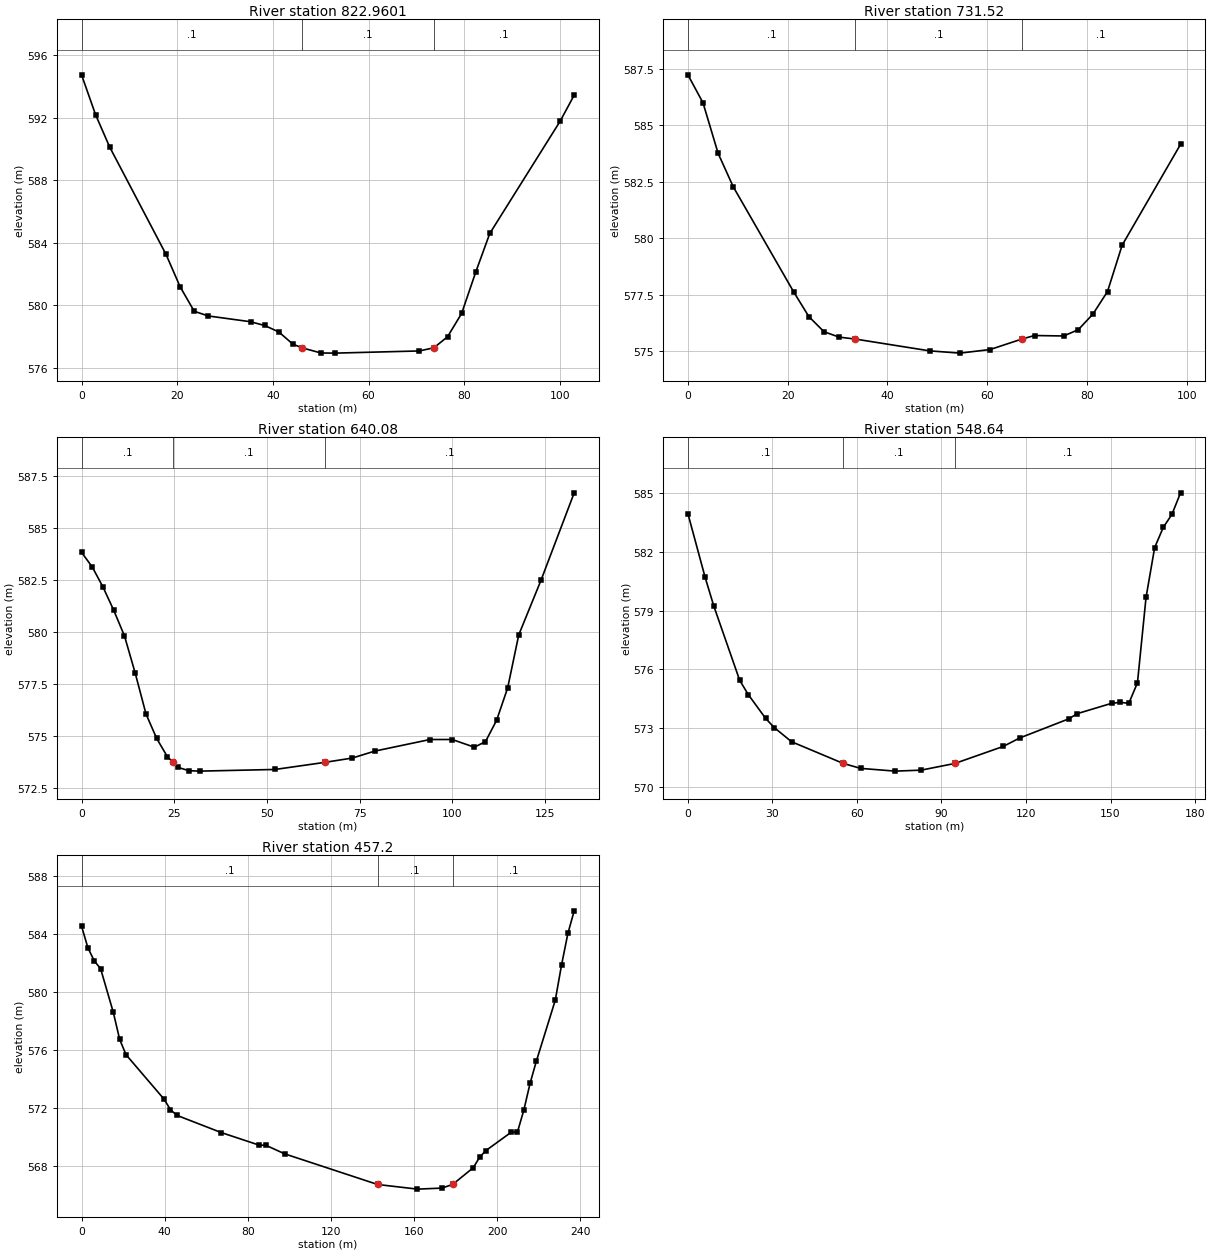
Type RM Length L Ch R = 1 ,822.9601,94.7,91.44,91.53
XS GIS Cut Line= 3
     615173.2853     4340970.841     615129.1365    4340970.3694
     615070.6689    4340976.7476
#Sta/Elev= 22
       0  594.76    2.94   592.2    5.89  590.13   17.66  583.26    20.6  581.19
   23.55  579.62   26.49  579.32   35.32  578.95   38.26  578.71   41.21   578.3
   44.15  577.52   46.03577.2834   50.03  576.95   52.97  576.94   70.62  577.08
   73.66577.2849    76.5  577.99   79.44  579.48   82.38  582.12   85.32   584.6
  100.03  591.79  102.97  593.46
#Mann= 3 , 0 , 0
       0      .1       0   46.03      .1       0   73.66      .1       0
Bank Sta=46.03,73.66
XS Rating Curve= 0 ,0
Exp/Cntr=0.3,0.1

Type RM Length L Ch R = 1 ,731.52  ,89.13,91.44,92.71
XS GIS Cut Line= 3
     615166.9774    4340877.7464     615103.4429    4340881.0556
     615068.7178    4340886.3772
#Sta/Elev= 20
       0  587.24    3.03     586    6.06  583.76    9.09  582.28   21.21  577.62
   24.24  576.53   27.27  575.86    30.3  575.62   33.54575.5337   48.47  575.01
   54.53  574.91   60.59  575.07   66.94 575.534   69.48  575.69   75.33  575.67
   78.26  575.95   81.19  576.64   84.11  577.64   87.04  579.69   98.75  584.16
#Mann= 3 , 0 , 0
       0      .1       0   33.54      .1       0   66.94      .1       0
Bank Sta=33.54,66.94
XS Rating Curve= 0 ,0
Exp/Cntr=0.3,0.1

Type RM Length L Ch R = 1 ,640.08  ,92.13,91.44,86.51
XS GIS Cut Line= 4
     615167.0769    4340794.9635     615126.6832    4340791.4864
     615112.2898    4340789.2606     615034.5203    4340787.2906
#Sta/Elev= 26
       0  583.81     2.9   583.1    5.79  582.14    8.69  581.02   11.58  579.79
   14.48     578   17.38  576.04   20.27  574.86   23.17  573.98   24.69573.7117
   26.06  573.47   28.96  573.31   31.86  573.29   52.19  573.37   65.63573.7113
   73.06  573.92   79.04  574.25      94  574.81   99.99  574.81  105.97  574.44
  108.97  574.71  111.96  575.73  114.95  577.29  117.94  579.84  123.93  582.46
   132.9  586.67
#Mann= 3 , 0 , 0
       0      .1       0   24.69      .1       0   65.63      .1       0
Bank Sta=24.69,65.63
XS Rating Curve= 0 ,0
Exp/Cntr=0.3,0.1

Type RM Length L Ch R = 1 ,548.64  ,88.77,91.44,93.32
XS GIS Cut Line= 4
     615195.8371    4340697.0807     615113.1244    4340700.2574
     615058.4091    4340708.6752     615021.7694    4340710.8988
#Sta/Elev= 26
       0  583.95    6.13  580.69     9.2  579.23   18.39  575.44   21.46  574.71
   27.59   573.5   30.66  573.03   36.79  572.31   55.16571.2011   61.31  570.95
   73.58  570.81   82.77  570.86   94.73571.2012  111.91  572.07  117.74   572.5
  135.22  573.48  138.13  573.74  150.37  574.27  153.43  574.32  156.49  574.27
  159.55  575.32   162.6  579.68  165.66  582.22  168.72  583.25  171.78  583.91
  174.84  585.01
#Mann= 3 , 0 , 0
       0      .1       0   55.16      .1       0   94.73      .1       0
Bank Sta=55.16,94.73
XS Rating Curve= 0 ,0
Exp/Cntr=0.3,0.1

Type RM Length L Ch R = 1 ,457.2   ,45.57,91.44,92.07
XS GIS Cut Line= 5
     615217.7698    4340675.7966     615143.9787    4340611.6466
     615102.7611    4340610.9018     615074.5517    4340612.8252
      615004.803    4340614.5877
#Sta/Elev= 30
       0  584.54    3.06  583.05    6.11  582.15    9.17  581.61   15.28   578.6
   18.33  576.74   21.39  575.68   39.72  572.61   42.78  571.89   45.83   571.5
   67.22  570.31   85.55  569.44   88.61  569.44   97.78  568.84  142.47566.7296
  161.62  566.41  173.34  566.48  178.54566.7297  188.51  567.89  191.54  568.61
  194.58  569.07  206.71  570.33  209.75  570.35  212.78  571.84  215.81   573.7
  218.85  575.24  227.95  579.44  230.98  581.88  234.01  584.04  237.05   585.6
#Mann= 3 , 0 , 0
       0      .1       0  142.47      .1       0  178.54      .1       0
Bank Sta=142.47,178.54
XS Rating Curve= 0 ,0
Exp/Cntr=0.3,0.1