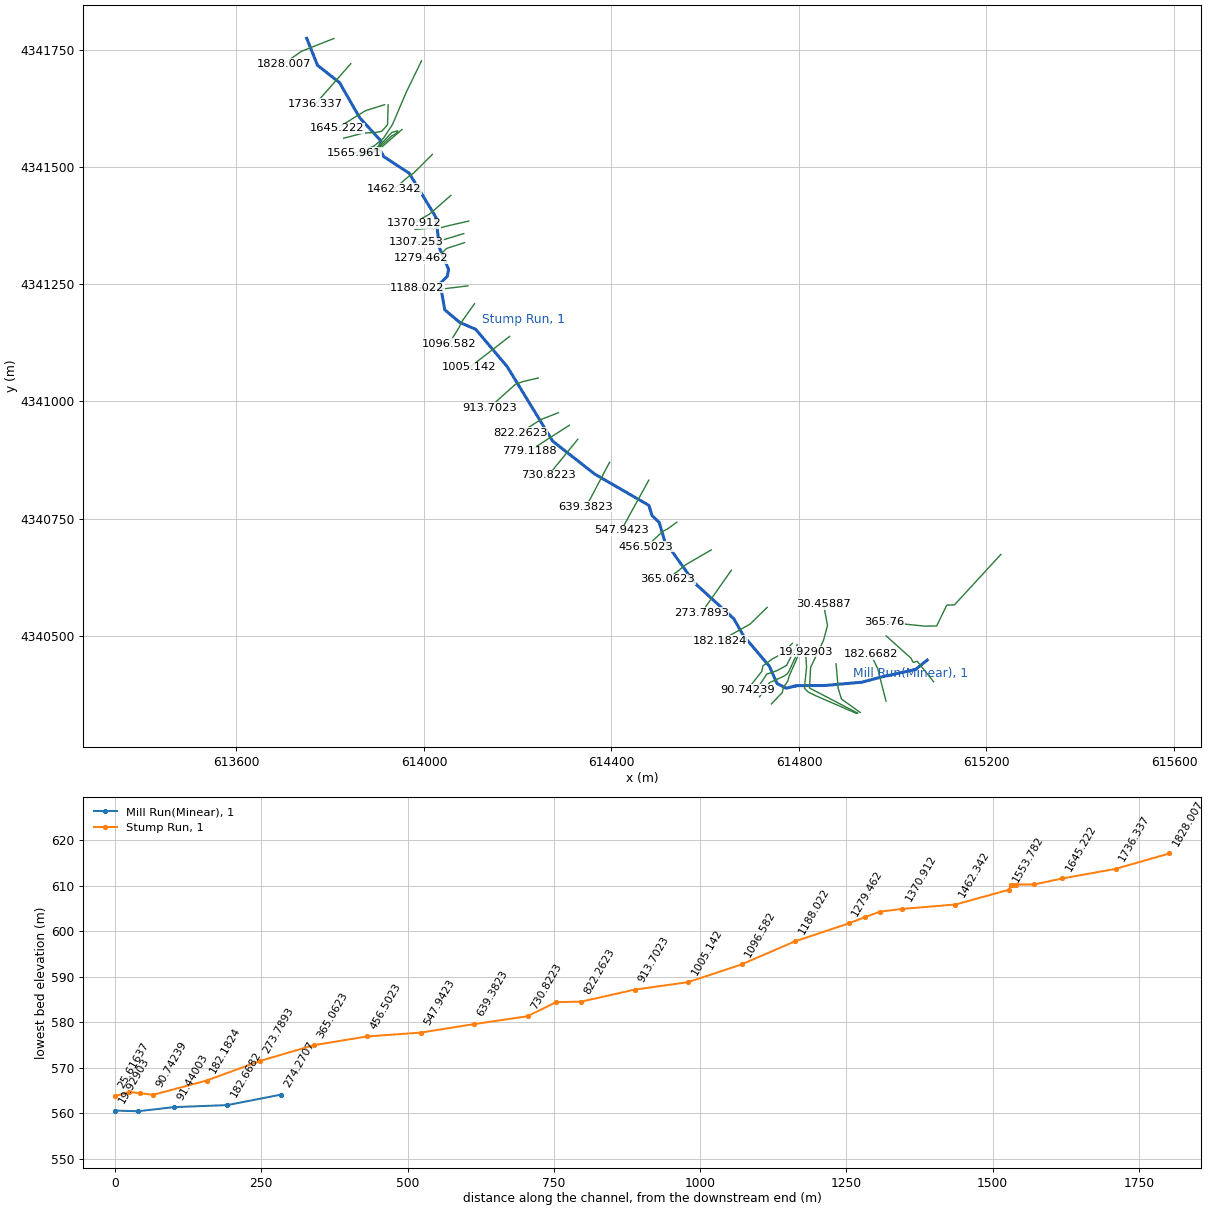
HEC-RAS study MinearRun.prj: MinearRun

--- MinearRun.g01 (geometry) --- (continued)

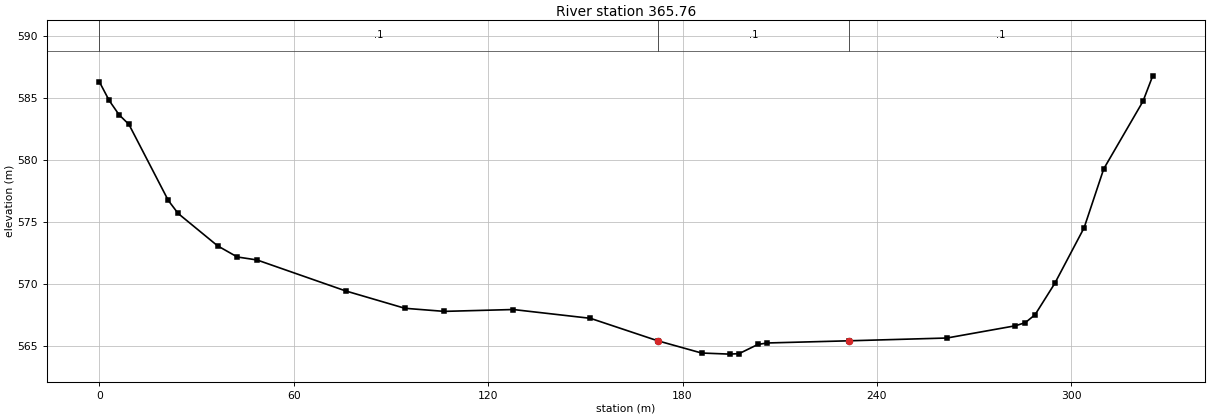
Type RM Length L Ch R = 1 ,365.76  ,45.19,91.49,77.95
XS GIS Cut Line= 6
     615230.7431    4340673.5738      615131.874    4340566.1382
     615115.2052    4340565.3444      615093.785    4340520.9884
     615068.3662    4340520.5849     614981.0612    4340529.6256
#Sta/Elev= 30
       0  586.34    3.04  584.83    6.08  583.68    9.13   582.9   21.29  576.76
   24.33  575.71    36.5   573.1   42.58   572.2   48.67  571.96   76.04  569.46
    94.3  568.06  106.46  567.81  127.75  567.96  151.57  567.25  172.37565.4352
  185.87  564.45  194.57  564.36  197.46   564.4  203.26  565.14  206.16  565.26
  231.41565.4356  261.59  565.66  282.77  566.65   285.8   566.9  288.82  567.54
  294.88  570.06  303.96  574.56  310.01  579.31  322.12  584.76  325.14  586.82
#Mann= 3 , 0 , 0
       0      .1       0  172.37      .1       0  231.41      .1       0
Bank Sta=172.37,231.41
XS Rating Curve= 0 ,0
Exp/Cntr=0.3,0.1

River Reach=Mill Run(Minear),1
Reach XY= 30
     615073.5775    4340448.2522     615069.0555    4340444.5961
     615064.5335    4340440.9401     615057.7506    4340435.4559
     615048.7066    4340428.1438     615034.0342    4340424.9478
     615031.0998    4340424.3087     615025.2308    4340423.0303
     614998.8206    4340417.2775     614995.8861    4340416.6384
     614978.2793    4340412.8032      614934.559    4340401.0659
     614925.6513    4340400.2721     614922.6821    4340400.0076
     614904.8668      4340398.42     614901.8976    4340398.1555
     614887.0514    4340396.8325     614884.0822     4340396.568
     614866.2669    4340394.9804     614863.2977    4340394.7159
       614854.39    4340393.9221     614845.5645    4340393.8978
     614842.6227    4340393.8898     614827.9136    4340393.8493
     614824.9718    4340393.8413     614807.3209    4340393.7927
     614804.3791    4340393.7847     614795.5536    4340393.7604
     614793.7014    4340393.3115     614791.8493    4340392.8625

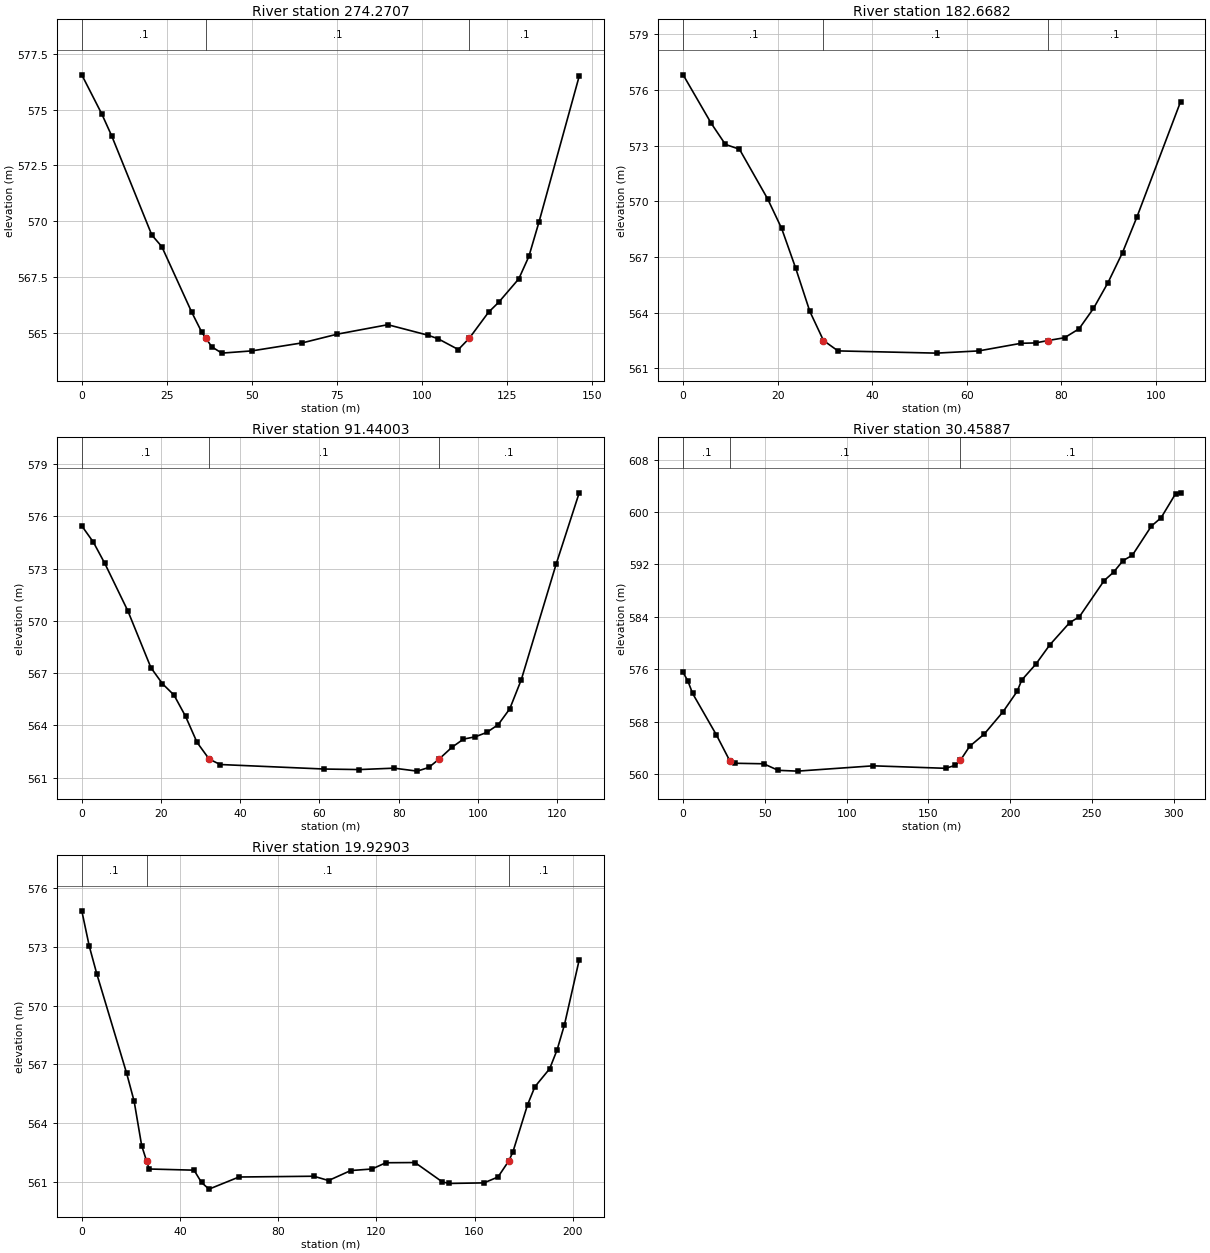
Type RM Length L Ch R = 1 ,274.2707,93.1,91.6,76.07
XS GIS Cut Line= 5
     615087.3297    4340401.9924     615052.4042    4340445.5803
     615043.7345    4340443.1728      615038.972     4340452.301
     614986.0891    4340499.7599
#Sta/Elev= 24
       0  576.55    5.88   574.8    8.82  573.81   20.58  569.39   23.52  568.87
   32.34  565.93   35.28  565.04   36.47564.7769   38.22  564.39   41.16  564.11
   49.97  564.21   64.85  564.57   75.15  564.96   89.95  565.38  101.79  564.91
  104.75  564.75  110.68  564.27   113.9564.7762  119.56  565.94  122.52  566.38
  128.44  567.43   131.4  568.43  134.36  569.96   146.2  576.49
#Mann= 3 , 0 , 0
       0      .1       0   36.47      .1       0   113.9      .1       0
Bank Sta=36.47,113.9
XS Rating Curve= 0 ,0
Exp/Cntr=0.3,0.1

Type RM Length L Ch R = 1 ,182.6682,91.79,91.23,89.94
XS GIS Cut Line= 3
     614985.7295    4340360.7173     614967.9515    4340429.9711
       614953.22    4340460.3458
#Sta/Elev= 22
       0  576.82    5.96   574.2    8.94  573.07   11.92  572.81   17.87  570.14
   20.85  568.54   23.83  566.39   26.81  564.07    29.7 562.499   32.77  561.94
   53.62  561.82   62.56  561.94    71.5  562.35   74.57  562.37   77.21 562.499
   80.71  562.65   83.78  563.13   86.84  564.23   89.91  565.62   92.98  567.24
   96.05  569.17  105.26  575.37
#Mann= 3 , 0 , 0
       0      .1       0    29.7      .1       0   77.21      .1       0
Bank Sta=29.7,77.21
XS Rating Curve= 0 ,0
Exp/Cntr=0.3,0.1

Type RM Length L Ch R = 1 ,91.44003,35.79,60.98,60.98
XS GIS Cut Line= 4
     614930.6961    4340336.3756     614890.5713    4340365.3014
     614883.8379    4340387.8394     614879.1706    4340440.2164
#Sta/Elev= 26
       0  575.46    2.91  574.53    5.82   573.3   11.64  570.57   17.46  567.31
   20.37  566.39   23.28  565.74   26.19  564.52    29.1  563.02   32.15562.0641
   34.92  561.75   61.23  561.49   70.05  561.46   78.83  561.54   84.67  561.37
   87.59  561.58   90.21562.0645   93.44  562.74   96.36  563.21   99.28  563.34
   102.2  563.59  105.12  564.04  108.04  564.95  110.96  566.63  119.73  573.25
  125.57  577.36
#Mann= 3 , 0 , 0
       0      .1       0   32.15      .1       0   90.21      .1       0
Bank Sta=32.15,90.21
XS Rating Curve= 0 ,0
Exp/Cntr=0.3,0.1

Type RM Length L Ch R = 1 ,30.45887,6990.96,39.6,39.9
XS GIS Cut Line= 6
     614925.4365    4340334.9901     614822.4798    4340388.6715
     614824.8946    4340432.5554     614852.3452    4340490.1024
     614860.9442    4340522.1832     614852.3452    4340567.8239
#Sta/Elev= 30
       0  575.53     2.9  574.22     5.8  572.32   20.29  566.02   28.44562.0888
   31.88  561.67   49.27  561.59   58.15  560.59      70  560.47  116.22  561.28
  160.47   560.9  166.36  561.35  169.46562.0922  175.19  564.25  184.03   566.1
  195.64  569.53  204.22  572.63  207.07  574.37  215.65  576.78  224.23  579.74
  236.31  583.11  242.35  584.04  257.45  589.54   263.2  590.82  268.96  592.58
  274.71  593.41  286.32  597.85  292.27  599.13  301.19  602.82  304.16  602.93
#Mann= 3 , 0 , 0
       0      .1       0   28.44      .1       0  169.46      .1       0
Bank Sta=28.44,169.46
XS Rating Curve= 0 ,0
Exp/Cntr=0.3,0.1

Type RM Length L Ch R = 1 ,19.92903,6980.35,19.93,21.72
XS GIS Cut Line= 6
     614922.5719    4340334.5377     614835.8678    4340372.1615
     614819.6753     4340380.099     614811.7025     4340388.149
     614816.2665    4340433.4788      614814.044    4340466.4989
#Sta/Elev= 30
       0  574.85    3.05  573.04     6.1  571.63   18.29  566.53   21.34   565.1
   24.39  562.84   26.44562.0334   27.44  561.64   45.73  561.58   48.78  560.95
   51.83  560.61   64.03  561.23   94.52  561.27  100.53  561.05  109.54  561.56
  118.21  561.64  123.88  561.96  135.75  561.97  146.87  560.98  149.65   560.9
  163.86  560.93  169.55  561.23  173.86562.0355  175.57  562.49  181.58  564.92
  184.59  565.85  190.61  566.77  193.62  567.73  196.63  569.02  202.64  572.34
#Mann= 3 , 0 , 0
       0      .1       0   26.44      .1       0  173.86      .1       0
Bank Sta=26.44,173.86
XS Rating Curve= 0 ,0
Exp/Cntr=0.3,0.1

River Reach=Stump Run       ,1
Reach XY= 30
     613750.0511    4341774.4173     613773.0699    4341716.8703
     613820.1658    4341679.8815 613863.137906794341604.96250459
613908.6759792654341555.33853266613904.393046605 4341540.2789233
613914.3083790824341522.16844422     613968.7296    4341486.6824
     614025.4829    4341393.0197     614033.4204    4341326.7414
      614052.735    4341281.6299     614049.8412    4341266.6644
     614034.5615    4341251.6823      614044.533    4341195.2962
     614076.6799     4341168.388     614110.6789    4341153.6375
     614177.9415    4341073.7948     614274.7209    4340915.1812
     614364.4148    4340844.9342     614479.9057    4340778.2591
     614486.6526    4340756.4309     614502.0391    4340741.6855
 614513.684223124340701.91768147     614577.8297    4340612.2957
     614661.2779    4340536.1649     614681.1217    4340500.8429
     614737.0812    4340434.9615     614753.2637    4340398.2811
        614772.8    4340388.1302     614791.8493    4340392.8625

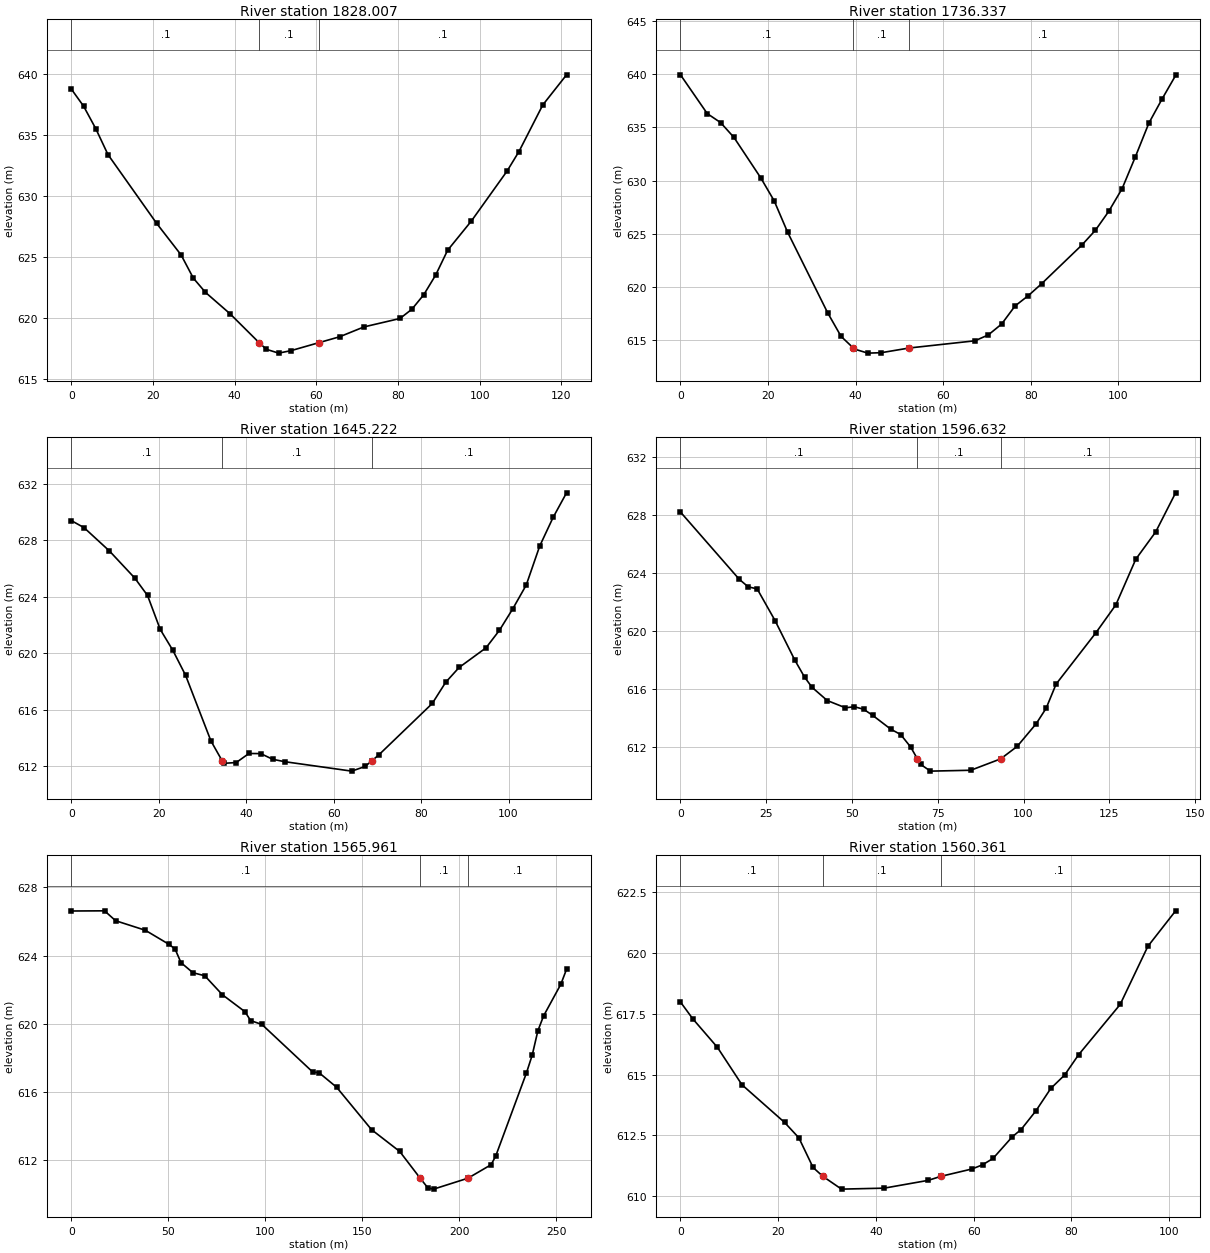
Type RM Length L Ch R = 1 ,1828.007,86.32,91.67,99.41
XS GIS Cut Line= 3
     613808.2343    4341774.1507     613738.8208    4341746.7557
     613700.6979    4341719.9217
#Sta/Elev= 26
       0  638.78    2.98  637.39    5.97  635.54    8.95  633.42   20.89  627.77
   26.86  625.19   29.85  623.29   32.83  622.12    38.8  620.38   45.96617.9978
   47.76  617.45   50.74  617.14   53.73  617.34    60.6617.9976   65.67  618.48
   71.64  619.29   80.45  619.98   83.37  620.74   86.28  621.93   89.19  623.54
   92.11  625.57   97.93  627.97  106.68  632.07  109.59  633.67  115.42  637.49
  121.24  639.96
#Mann= 3 , 0 , 0
       0      .1       0   45.96      .1       0    60.6      .1       0
Bank Sta=45.96,60.6
XS Rating Curve= 0 ,0
Exp/Cntr=0.3,0.1

Type RM Length L Ch R = 1 ,1736.337,100.42,91.11,87.21
XS GIS Cut Line= 2
     613843.9531    4341720.1756     613769.3405    4341635.2442
#Sta/Elev= 28
       0  639.95    6.11   636.3    9.17  635.45   12.22  634.05   18.33  630.25
   21.39  628.09   24.44  625.15   33.61  617.54   36.66  615.33   39.45614.2359
   39.72  614.13   42.78  613.75   45.83  613.79   52.26614.2346   67.22  614.91
   70.27  615.46   73.33  616.49   76.39  618.19   79.44  619.17    82.5   620.3
   91.66  623.93   94.72  625.31   97.77  627.09  100.83  629.23  103.88  632.25
  106.94   635.4  109.99   637.7  113.05  639.89
#Mann= 3 , 0 , 0
       0      .1       0   39.45      .1       0   52.26      .1       0
Bank Sta=39.45,52.26
XS Rating Curve= 0 ,0
Exp/Cntr=0.3,0.1

Type RM Length L Ch R = 1 ,1645.222,51.57,48.59,43.48
XS GIS Cut Line= 4
     613916.1128    4341632.8664     613877.3649    4341620.7026
     613870.1537    4341616.9402     613815.3781    4341582.8566
#Sta/Elev= 30
       0  629.38     2.9  628.88     8.7  627.23    14.5  625.31   17.41  624.08
   20.31  621.68   23.21  620.19   26.11  618.43   31.91  613.78   34.51612.3545
   34.81  612.19   37.71  612.25   40.61  612.89   43.32  612.88   46.03  612.48
   48.75  612.31   64.11  611.64   67.18  611.97   68.66612.3557   70.25  612.77
   82.54  616.43   85.61  617.93   88.68  618.98   94.83  620.37    97.9  621.61
  100.97  623.14  104.04  624.82  107.12  627.58  110.19  629.61  113.26  631.35
#Mann= 3 , 0 , 0
       0      .1       0   34.51      .1       0   68.66      .1       0
Bank Sta=34.51,68.66
XS Rating Curve= 0 ,0
Exp/Cntr=0.3,0.1

Type RM Length L Ch R = 1 ,1596.632,21.35,30.67,32.67
XS GIS Cut Line= 6
     613923.7625    4341632.7634     613922.4396    4341590.0992
     613910.2026    4341576.2086     613895.9812    4341573.5627
     613871.0707    4341572.4118     613828.9489    4341561.4051
#Sta/Elev= 30
       0  628.22   17.14  623.57   19.74  623.05   22.35  622.91   27.56  620.72
   33.29     618   36.16  616.81   38.36   616.1   42.78  615.19   48.07  614.69
   50.71  614.76   53.36  614.59      56  614.17   61.29  613.21   64.18  612.84
   67.08  611.98   69.06611.1579   69.97  610.78   72.86  610.31   84.61  610.37
   93.33611.1573   98.14  612.02  103.69  613.59  106.59  614.66  109.49  616.33
   121.1  619.88  126.91  621.81  132.71  624.96  138.52  626.85  144.32  629.55
#Mann= 3 , 0 , 0
       0      .1       0   69.06      .1       0   93.33      .1       0
Bank Sta=69.06,93.33
XS Rating Curve= 0 ,0
Exp/Cntr=0.3,0.1

Type RM Length L Ch R = 1 ,1565.961,5.89,5.6,5.63
XS GIS Cut Line= 6
     613994.9832    4341726.6351     613962.3124    4341659.2614
     613933.2611    4341591.1576     613914.2111    4341561.9475
      613893.256    4341544.3262     613851.6634    4341529.7212
#Sta/Elev= 30
       0  626.62   17.08  626.63   22.77  626.05    38.1  625.49   50.36  624.66
   53.43  624.39   56.49  623.59   62.62     623   68.75  622.82    77.8  621.71
   89.48  620.71    92.4  620.19   98.24  619.96  124.52  617.16  127.57  617.14
  136.72  616.28  154.74  613.79  169.27  612.51  179.81610.9413   183.8  610.37
  186.73   610.3  204.46610.9415  216.34  611.73  218.73  612.23  234.61  617.12
  237.57  618.16  240.52   619.6  243.47  620.47  252.33  622.32  255.28   623.2
#Mann= 3 , 0 , 0
       0      .1       0  179.81      .1       0  204.46      .1       0
Bank Sta=179.81,204.46
XS Rating Curve= 0 ,0
Exp/Cntr=0.3,0.1

Type RM Length L Ch R = 1 ,1560.361,3.06,3.83,3.89
XS GIS Cut Line= 6
     613943.8753     4341577.057     613931.7045     4341573.882
      613911.896    4341552.5565     613898.4551    4341540.5973
     613892.6475    4341537.8854     613859.3774    4341526.3442
#Sta/Elev= 24
       0  617.98    2.52  617.29    7.55  616.12   12.58  614.58   21.31  613.03
   24.22   612.4   27.13  611.18   29.13610.8157   32.95  610.29   41.68  610.33
   50.68  610.65   53.31610.8166   59.68  611.12   61.81  611.29   63.95  611.55
   67.89  612.44    69.7  612.74   72.74  613.51   75.78  614.43   78.61  614.98
   81.45  615.81   89.97  617.88   95.64  620.27  101.32  621.73
#Mann= 3 , 0 , 0
       0      .1       0   29.13      .1       0   53.31      .1       0
Bank Sta=29.13,53.31
XS Rating Curve= 0 ,0
Exp/Cntr=0.3,0.1

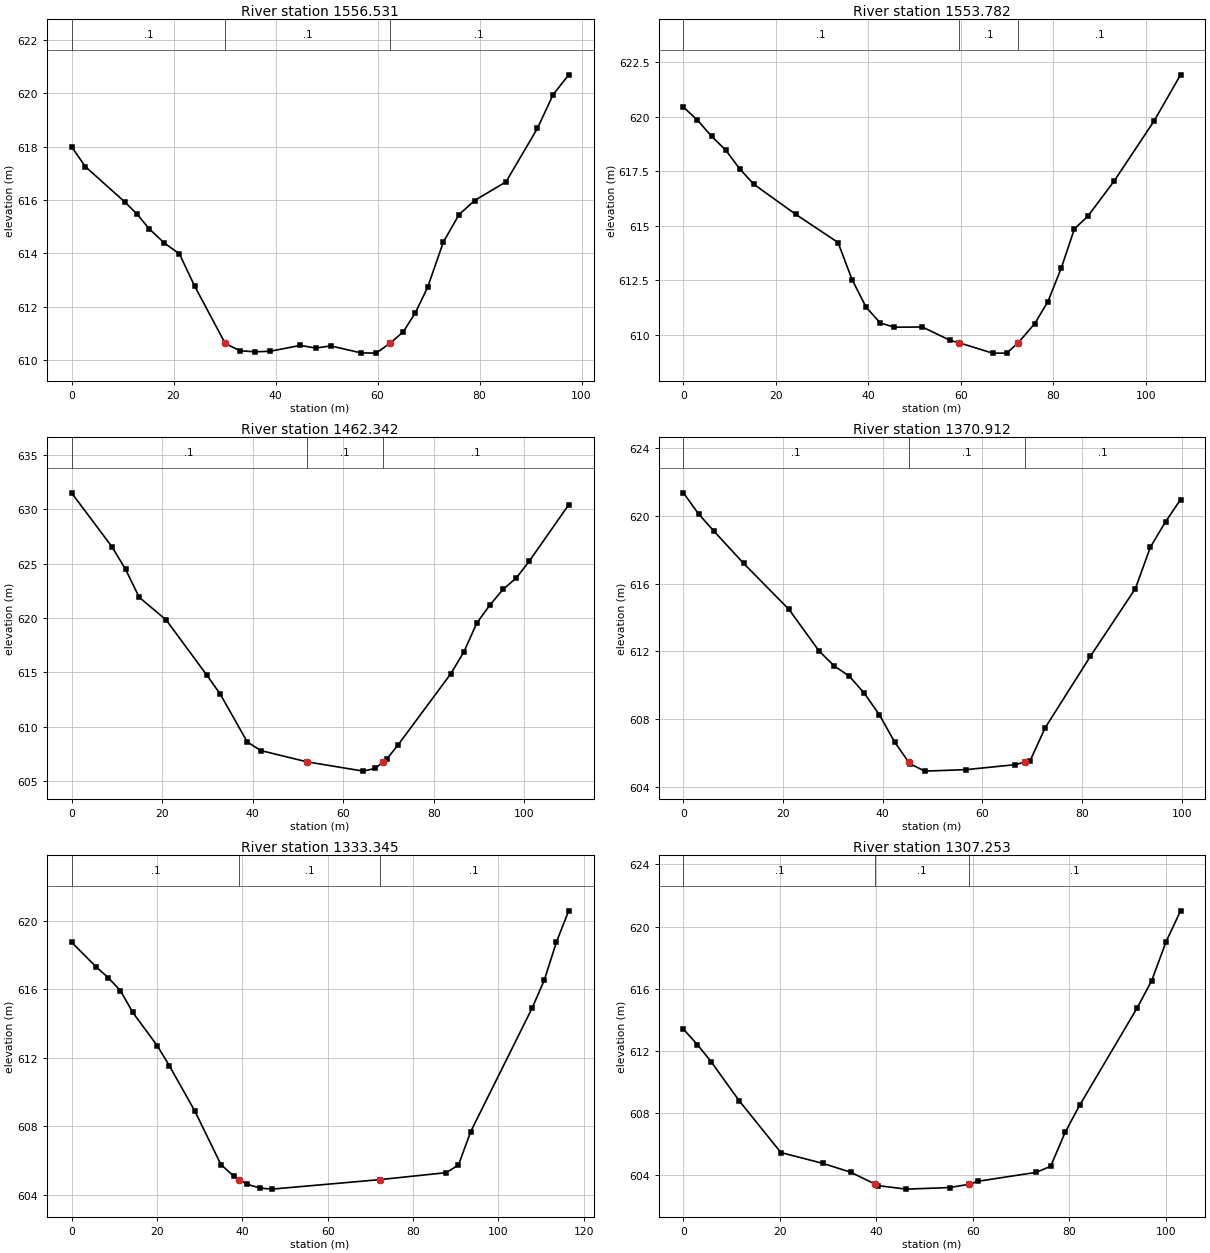
Type RM Length L Ch R = 1 ,1556.531,3.26,2.75,2.99
XS GIS Cut Line= 6
     613944.4433      4341575.01     613938.1991    4341569.8242
     613931.8491    4341566.6492     613898.9349    4341536.6983
     613894.1724    4341534.2773     613863.2875    4341524.4361
#Sta/Elev= 28
       0     618    2.71  617.25   10.48  615.92   12.85  615.47   15.22  614.92
   18.18  614.39   21.15  613.98   24.12  612.78   30.14610.6215   33.02  610.35
   35.98  610.31   38.95  610.33   44.88  610.55   47.85  610.45   50.82  610.53
   56.75  610.27   59.72  610.26    62.4610.6216   65.06  611.06   67.44  611.78
   69.83  612.73    72.9  614.42   75.97  615.45   79.04  615.98   85.19  616.68
   91.34  618.68   94.41  619.94   97.48  620.69
#Mann= 3 , 0 , 0
       0      .1       0   30.14      .1       0    62.4      .1       0
Bank Sta=30.14,62.4
XS Rating Curve= 0 ,0
Exp/Cntr=0.3,0.1

Type RM Length L Ch R = 1 ,1553.782,87.86,91.44,95.51
XS GIS Cut Line= 4
     613953.3926    4341579.9629     613900.4898    4341534.2925
     613895.0075    4341531.7227     613865.0878    4341521.7544
#Sta/Elev= 26
       0  620.45    3.04  619.85    6.08  619.11    9.12  618.48   12.15  617.62
   15.19  616.91   24.31  615.52   33.43  614.23   36.46  612.53    39.5  611.26
   42.54  610.54   45.58  610.34   51.66  610.35   57.73  609.73   59.55609.6282
   66.85  609.15   69.89  609.15   72.39609.6285   75.94   610.5   78.81  611.52
   81.68  613.05   84.54  614.86   87.41  615.43   93.15  617.06  101.75  619.81
  107.48  621.93
#Mann= 3 , 0 , 0
       0      .1       0   59.55      .1       0   72.39      .1       0
Bank Sta=59.55,72.39
XS Rating Curve= 0 ,0
Exp/Cntr=0.3,0.1

Type RM Length L Ch R = 1 ,1462.342,92.5,91.43,91.59
XS GIS Cut Line= 4
     614017.9964    4341526.7648     613977.8334    4341486.7079
     613965.0954    4341478.0137     613937.0337    4341452.9459
#Sta/Elev= 23
       0   631.5    8.96  626.52   11.94  624.46   14.93   621.9    20.9  619.81
   29.85  614.75   32.84  612.99   38.81  608.59    41.8   607.8   51.97606.7657
   64.44  605.91   67.01  606.16   68.86606.7643   69.58     607   72.15  608.35
   83.72  614.85   86.62  616.87   89.51  619.54   92.41   621.2    95.3  622.63
    98.2  623.67  101.09  625.23  109.77   630.4
#Mann= 3 , 0 , 0
       0      .1       0   51.97      .1       0   68.86      .1       0
Bank Sta=51.97,68.86
XS Rating Curve= 0 ,0
Exp/Cntr=0.3,0.1

Type RM Length L Ch R = 1 ,1370.912,42.65,37.57,30.52
XS GIS Cut Line= 3
      614057.684    4341439.4522     614012.1458    4341399.5967
      613978.013    4341380.2561
#Sta/Elev= 24
       0  621.36    3.03  620.12    6.05  619.12    12.1  617.19   21.18  614.48
   27.23  612.02   30.26  611.14   33.28  610.54   36.31  609.52   39.34  608.25
   42.36  606.66   45.19605.4645   45.39  605.38   48.41  604.93   56.79  605.02
   66.55  605.31   68.52605.4666   69.57  605.55   72.59  607.49   81.64   611.7
   90.69  615.71   93.71  618.16   96.73  619.65   99.75  620.96
#Mann= 3 , 0 , 0
       0      .1       0   45.19      .1       0   68.52      .1       0
Bank Sta=45.19,68.52
XS Rating Curve= 0 ,0
Exp/Cntr=0.3,0.1

Type RM Length L Ch R = 1 ,1333.345,26.22,26.09,26.49
XS GIS Cut Line= 6
     614095.7897    4341384.6384     614052.6625    4341374.8488
     614034.4062    4341370.0863     614020.9124    4341368.7634
     614009.7999    4341369.2925     613981.2249    4341366.9113
#Sta/Elev= 22
       0  618.74    5.73  617.31     8.6  616.67   11.47  615.91   14.33  614.65
   20.07  612.71   22.93  611.53   28.87   608.9   35.01  605.77   38.08  605.08
   39.33604.8927   41.15  604.62   44.22   604.4   46.92  604.34   72.17604.8932
   87.78   605.3   90.64  605.75   93.51   607.7  107.85  614.88  110.71  616.51
  113.58  618.75  116.45  620.57
#Mann= 3 , 0 , 0
       0      .1       0   39.33      .1       0   72.17      .1       0
Bank Sta=39.33,72.17
XS Rating Curve= 0 ,0
Exp/Cntr=0.3,0.1

Type RM Length L Ch R = 1 ,1307.253,19.57,27.79,34.79
XS GIS Cut Line= 3
     614084.9417    4341357.9154     614040.7562    4341344.4216
     613984.1353    4341339.3945
#Sta/Elev= 21
       0  613.41    2.89  612.42    5.78   611.3   11.55  608.81   20.21  605.47
   28.87  604.78   34.65  604.21    39.8603.4316   40.43  603.34    46.2  603.12
   55.18  603.22   59.19 603.432   61.16  603.63   73.13   604.2   76.12  604.59
   79.11  606.77    82.1   608.5   94.07  614.79   97.06  616.53  100.05  619.04
  103.04  621.02
#Mann= 3 , 0 , 0
       0      .1       0    39.8      .1       0   59.19      .1       0
Bank Sta=39.8,59.19
XS Rating Curve= 0 ,0
Exp/Cntr=0.3,0.1

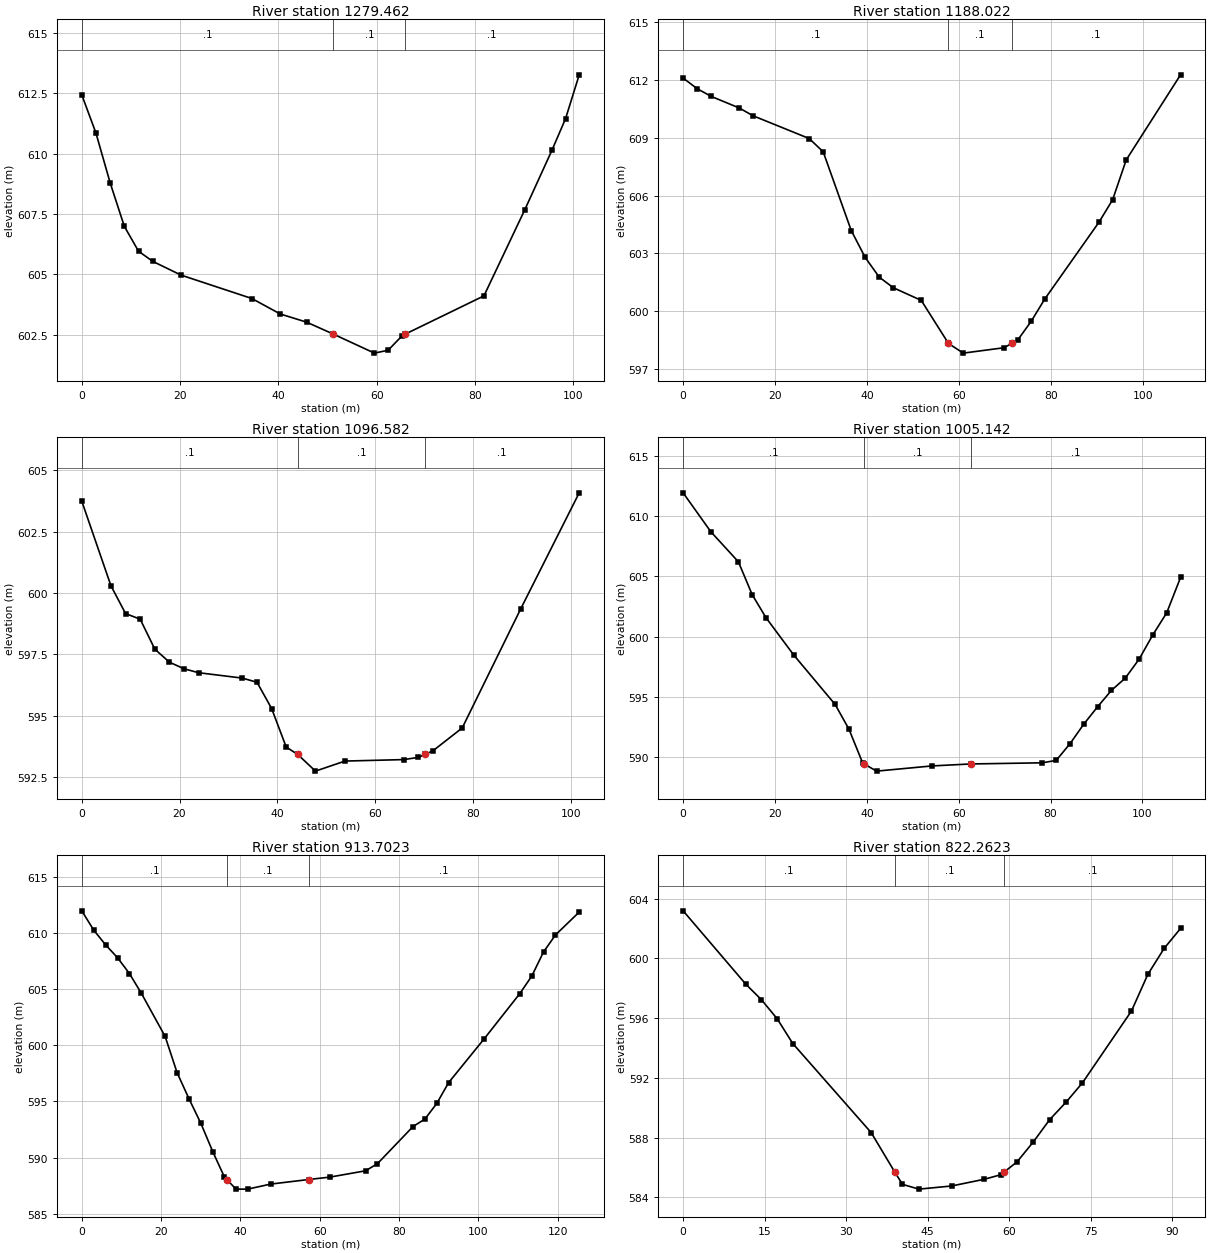
Type RM Length L Ch R = 1 ,1279.462,97.85,91.44,70.95
XS GIS Cut Line= 5
     614086.7542    4341338.7134     614048.3562    4341326.2049
     614040.7612    4341318.5797     614021.8863    4341306.5683
     613994.2649    4341304.8213
#Sta/Elev= 20
       0  612.43    2.88  610.85    5.77  608.79    8.65  606.99   11.54  605.96
   14.42  605.54   20.19  604.97   34.61     604   40.38  603.36   45.77  603.02
   51.21602.5244   59.54  601.74   62.33  601.86   65.13  602.45   65.79602.5255
   81.82  604.11   90.12  607.67   95.66  610.14   98.43  611.45   101.2  613.26
#Mann= 3 , 0 , 0
       0      .1       0   51.21      .1       0   65.79      .1       0
Bank Sta=51.21,65.79
XS Rating Curve= 0 ,0
Exp/Cntr=0.3,0.1

Type RM Length L Ch R = 1 ,1188.022,83.63,91.44,108.45
XS GIS Cut Line= 3
     614093.8961    4341246.4506     614033.3915    4341239.0203
     613986.2463    4341242.6018
#Sta/Elev= 23
       0  612.11    3.05  611.56     6.1  611.16   12.19  610.56   15.24  610.15
   27.43  608.97   30.48  608.28   36.58  604.19   39.62  602.79   42.67  601.77
   45.72  601.22   51.82  600.56   57.74598.3235   60.96  597.82   69.82   598.1
   71.52 598.324   72.78  598.49   75.73  599.47   78.69  600.63   90.51  604.63
   93.46  605.79   96.42  607.86  108.24  612.28
#Mann= 3 , 0 , 0
       0      .1       0   57.74      .1       0   71.52      .1       0
Bank Sta=57.74,71.52
XS Rating Curve= 0 ,0
Exp/Cntr=0.3,0.1

Type RM Length L Ch R = 1 ,1096.582,95.71,91.44,83.03
XS GIS Cut Line= 4
     614108.1389    4341208.4563     614080.3507    4341169.5655
     614075.4818    4341158.4998     614053.6094    4341122.7982
#Sta/Elev= 22
       0  603.74    5.97  600.29    8.96  599.16   11.95  598.93   14.94  597.71
   17.92  597.18   20.91  596.91    23.9  596.75   32.86  596.53   35.85  596.36
   38.84  595.29   41.82  593.72   44.18593.4201    47.8  592.74   53.84  593.15
   65.87  593.21   68.86   593.3    70.2 593.421   71.85  593.57   77.83   594.5
   89.79  599.35  101.76  604.08
#Mann= 3 , 0 , 0
       0      .1       0   44.18      .1       0    70.2      .1       0
Bank Sta=44.18,70.2
XS Rating Curve= 0 ,0
Exp/Cntr=0.3,0.1

Type RM Length L Ch R = 1 ,1005.142,95.33,91.44,89.07
XS GIS Cut Line= 2
     614182.9134    4341138.5398      614097.221    4341072.3368
#Sta/Elev= 24
       0  611.92    6.02   608.7   12.03   606.2   15.04  603.47   18.05  601.56
   24.06  598.48   33.09  594.37    36.1  592.32    39.1   589.5    39.4589.4342
   42.11  588.84   54.14  589.27   62.58589.4343   78.21  589.53   81.22  589.73
   84.22  591.11   87.23  592.74   90.24  594.18   93.25  595.54   96.25  596.55
   99.26  598.12  102.27  600.15  105.28  601.97  108.29   604.9
#Mann= 3 , 0 , 0
       0      .1       0    39.4      .1       0   62.58      .1       0
Bank Sta=39.4,62.58
XS Rating Curve= 0 ,0
Exp/Cntr=0.3,0.1

Type RM Length L Ch R = 1 ,913.7023,90.61,91.44,91.51
XS GIS Cut Line= 4
     614243.6691    4341049.8337     614211.4862    4341042.3922
     614195.0428    4341036.2339     614139.3346    4340986.2729
#Sta/Elev= 30
       0  611.95       3  610.24    6.01  608.92    9.01  607.78   12.01  606.37
   15.01  604.62   21.02  600.77   24.02  597.56   27.03  595.23   30.03  593.04
   33.03  590.52   35.96  588.27   36.57588.0435   38.88  587.19   41.81  587.19
   47.66  587.64    57.2588.0449   62.56  588.26   71.54  588.82   74.54  589.45
   83.52  592.76   86.51  593.42    89.5  594.81    92.5  596.67  101.48  600.57
  110.45  604.59  113.45  606.14  116.44   608.3  119.43   609.8  125.42  611.84
#Mann= 3 , 0 , 0
       0      .1       0   36.57      .1       0    57.2      .1       0
Bank Sta=36.57,57.2
XS Rating Curve= 0 ,0
Exp/Cntr=0.3,0.1

Type RM Length L Ch R = 1 ,822.2623,43.12,43.14,43.21
XS GIS Cut Line= 3
     614286.9724    4340975.9541     614249.3903    4340961.1724
     614206.2841    4340933.5649
#Sta/Elev= 22
       0  603.18   11.54  598.27   14.42  597.23   17.31  595.96   20.19   594.3
   34.62  588.34   38.95585.7092   40.38  584.88    43.4  584.56   49.42  584.77
   55.44  585.22   58.45  585.52   59.11585.7086   61.46  586.38   64.47  587.72
   67.48  589.21    70.5  590.38   73.51  591.67   82.54  596.48   85.55  598.93
   88.56  600.67   91.57     602
#Mann= 3 , 0 , 0
       0      .1       0   38.95      .1       0   59.11      .1       0
Bank Sta=38.95,59.11
XS Rating Curve= 0 ,0
Exp/Cntr=0.3,0.1

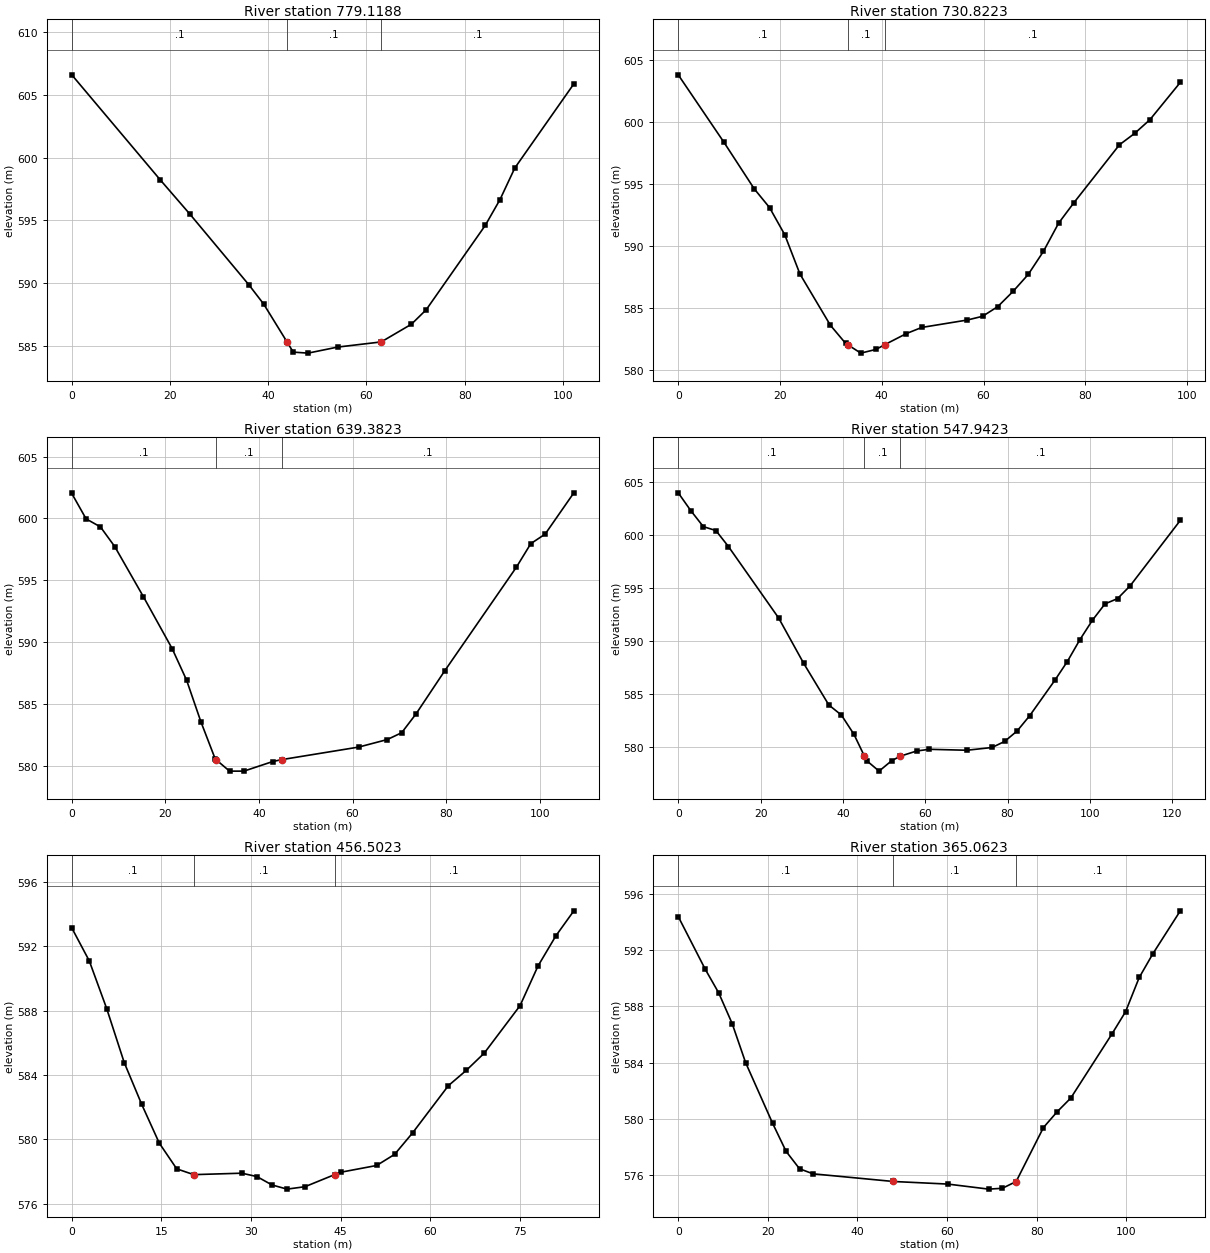
Type RM Length L Ch R = 1 ,779.1188,45.24,48.3,51.85
XS GIS Cut Line= 2
     614310.3672    4340949.1333     614224.3774    4340893.8353
#Sta/Elev= 16
       0  606.59   18.04  598.22   24.06   595.5   36.08  589.87   39.09  588.34
   43.83585.3328    45.1  584.52   48.11  584.44   54.12  584.92   63.01585.3317
   69.16  586.74   72.17  587.89   84.19   594.6    87.2  596.66   90.21  599.17
  102.24  605.87
#Mann= 3 , 0 , 0
       0      .1       0   43.83      .1       0   63.01      .1       0
Bank Sta=43.83,63.01
XS Rating Curve= 0 ,0
Exp/Cntr=0.3,0.1

Type RM Length L Ch R = 1 ,730.8223,89.46,91.44,93.93
XS GIS Cut Line= 2
     614328.3939    4340919.3099     614266.0587    4340842.8074
#Sta/Elev= 26
       0  603.79    8.97  598.36   14.95  594.59   17.94  593.09   20.93   590.9
   23.92  587.73    29.9   583.6   32.89  582.14   33.32 582.027   35.88  581.35
   38.88  581.65   40.56582.0261   44.86  582.93   47.85  583.42   56.82  584.02
   59.81  584.32    62.8   585.1   65.79  586.32   68.78  587.69   71.77  589.55
   74.76  591.83   77.75  593.47   86.72  598.15   89.71  599.07    92.7  600.17
   98.68  603.18
#Mann= 3 , 0 , 0
       0      .1       0   33.32      .1       0   40.56      .1       0
Bank Sta=33.32,40.56
XS Rating Curve= 0 ,0
Exp/Cntr=0.3,0.1

Type RM Length L Ch R = 1 ,639.3823,91.27,91.44,91.28
XS GIS Cut Line= 2
     614396.0531    4340870.0236     614345.9461    4340775.1781
#Sta/Elev= 23
       0  602.02    3.06  599.97    6.13  599.32    9.19  597.73   15.32  593.68
   21.45   589.5   24.52  586.97   27.58  583.61   30.65   580.6   30.82580.5455
   33.71  579.62   36.78  579.62   42.91  580.39   44.81580.5452    61.3  581.56
   67.43  582.17   70.49  582.72   73.56  584.24   79.68  587.71   95.01  596.08
   98.07  597.97  101.14  598.74  107.27  602.07
#Mann= 3 , 0 , 0
       0      .1       0   30.82      .1       0   44.81      .1       0
Bank Sta=30.82,44.81
XS Rating Curve= 0 ,0
Exp/Cntr=0.3,0.1

Type RM Length L Ch R = 1 ,547.9423,94.04,91.44,84.2
XS GIS Cut Line= 2
     614479.7893    4340832.1381      614421.037    4340725.2558
#Sta/Elev= 30
       0  604.01    3.05  602.33     6.1  600.82    9.15  600.45    12.2  598.94
   24.39   592.2   30.49  587.91   36.59  583.99   39.64  583.04   42.69  581.22
   45.23579.1633   45.74  578.75   48.79  577.75   51.84  578.73   53.96579.1624
   57.93  579.65   60.98  579.81   70.13  579.72   76.23  579.98   79.28  580.55
   82.33  581.54   85.38  582.98   91.47  586.31   94.52  588.09   97.57  590.15
  100.62  591.99  103.67  593.53  106.72  594.03  109.77  595.23  121.97  601.41
#Mann= 3 , 0 , 0
       0      .1       0   45.23      .1       0   53.96      .1       0
Bank Sta=45.23,53.96
XS Rating Curve= 0 ,0
Exp/Cntr=0.3,0.1

Type RM Length L Ch R = 1 ,456.5023,86.55,91.44,90.14
XS GIS Cut Line= 4
      614539.533    4340742.4072     614520.6384    4340728.5736
     614509.5084    4340722.6534     614474.3507    4340689.9919
#Sta/Elev= 25
       0  593.14    2.93  591.09    5.85  588.12    8.78  584.77   11.71  582.17
   14.64  579.77   17.56  578.17   20.41577.8101   28.46   577.9   30.98  577.69
    33.5  577.17   36.02  576.91   39.02  577.06   43.97577.8095   45.02  577.96
   51.02  578.38   54.02  579.07   57.02   580.4   63.02  583.34   66.02  584.29
   69.02  585.36   75.01  588.31   78.01  590.77   81.01  592.65   84.01   594.2
#Mann= 3 , 0 , 0
       0      .1       0   20.41      .1       0   43.97      .1       0
Bank Sta=20.41,43.97
XS Rating Curve= 0 ,0
Exp/Cntr=0.3,0.1

Type RM Length L Ch R = 1 ,365.0623,88.57,91.27,93.6
XS GIS Cut Line= 3
     614613.0207     4340683.255     614558.4013    4340651.5156
     614520.3039    4340620.9178
#Sta/Elev= 22
       0   594.4    6.02  590.65    9.02  588.97   12.03  586.78   15.04  583.99
   21.06  579.67   24.07  577.67   27.07  576.43   30.08  576.07   47.98 575.525
   60.16  575.34   69.28  574.98   72.33  575.04   75.41575.5227    81.5  579.37
   84.55  580.49    87.6  581.47   96.77  586.03   99.82  587.62  102.87  590.06
  105.93  591.76  112.04  594.81
#Mann= 3 , 0 , 0
       0      .1       0   47.98      .1       0   75.41      .1       0
Bank Sta=47.98,75.41
XS Rating Curve= 0 ,0
Exp/Cntr=0.3,0.1

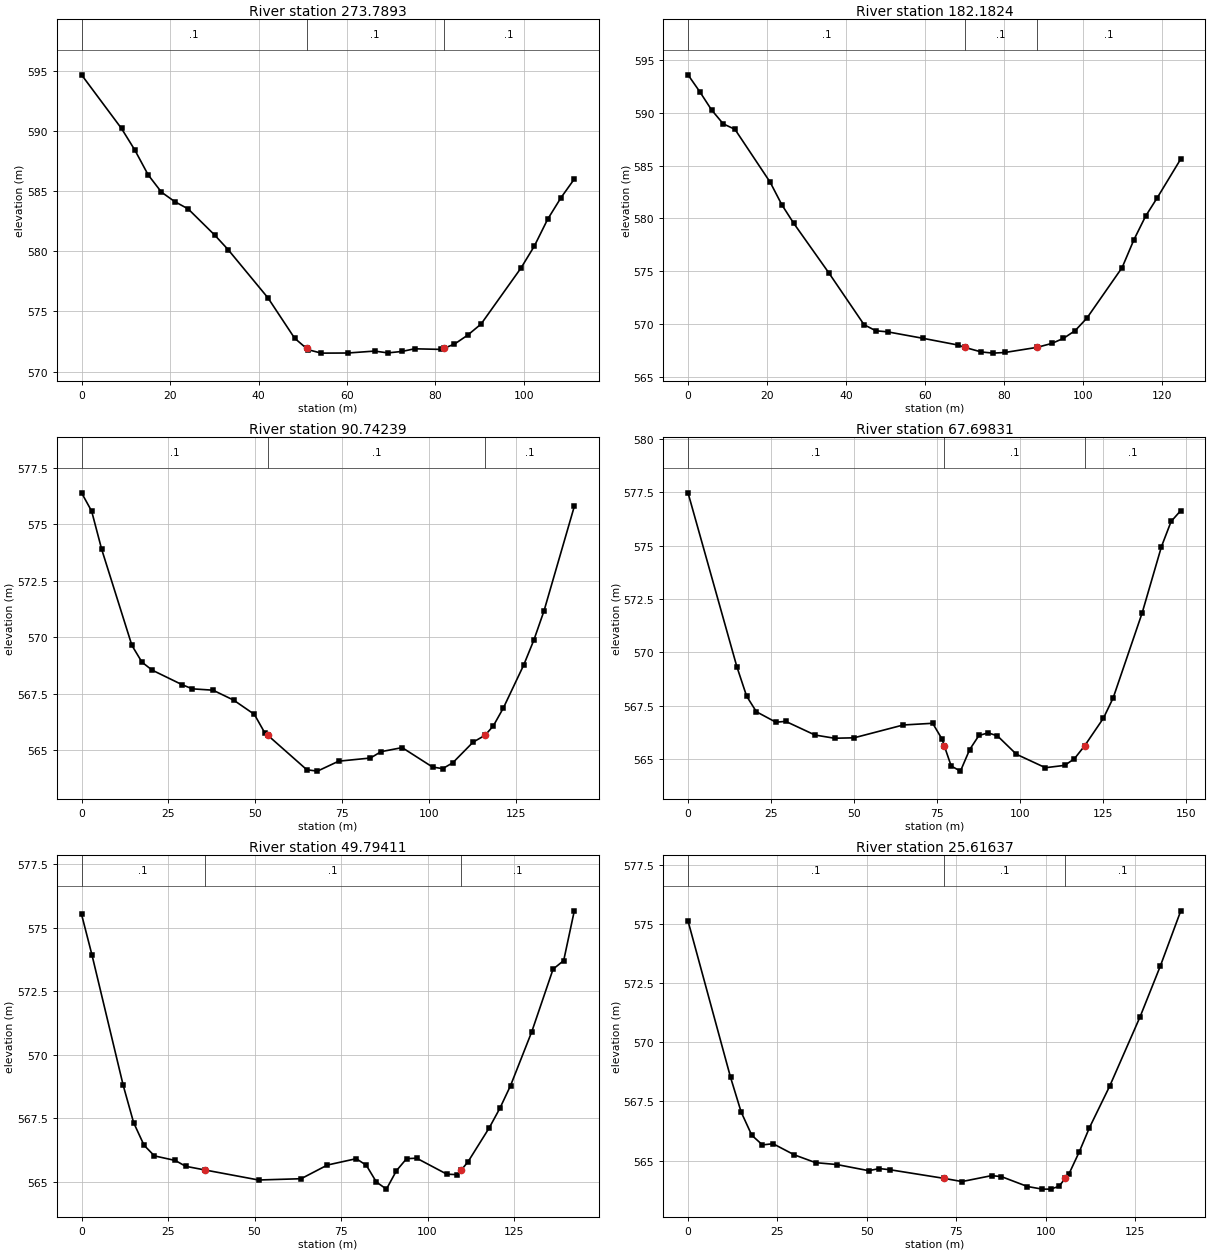
Type RM Length L Ch R = 1 ,273.7893,96.51,91.61,87.3
XS GIS Cut Line= 2
     614655.9081    4340639.9326     614591.7877    4340548.8626
#Sta/Elev= 29
       0  594.66    9.03   590.2   12.04  588.41   15.05  586.35   18.06  584.91
   21.07  584.12   24.08  583.52    30.1  581.34   33.11  580.14   42.14  576.12
   48.16  572.77   50.86571.9178   51.17  571.82   54.18  571.53    60.2  571.54
   66.23   571.7   69.24  571.55   72.43  571.67   75.26  571.89   81.28  571.84
   81.82571.9189   84.29  572.28    87.3  573.03   90.31  573.95   99.34  578.61
  102.35  580.43  105.36  582.66  108.37  584.45  111.38     586
#Mann= 3 , 0 , 0
       0      .1       0   50.86      .1       0   81.82      .1       0
Bank Sta=50.86,81.82
XS Rating Curve= 0 ,0
Exp/Cntr=0.3,0.1

Type RM Length L Ch R = 1 ,182.1824,92.36,91.44,99.64
XS GIS Cut Line= 3
     614732.1083    4340560.5575      614696.112    4340525.1935
     614631.4455     4340488.864
#Sta/Elev= 28
       0  593.62    2.97  592.02    5.94   590.3     8.9  588.97   11.87  588.45
   20.78  583.43   23.75  581.28   26.71  579.55   35.62  574.83   44.52  569.92
   47.49  569.34   50.46  569.24   59.36  568.63   68.26  567.99   69.94567.7693
    74.2  567.33   77.16  567.22   80.13  567.28   88.31567.7688      92  568.14
   94.96  568.62   97.93  569.36   100.9  570.55   109.8  575.34  112.77  577.97
  115.73  580.21   118.7  581.97  124.63  585.64
#Mann= 3 , 0 , 0
       0      .1       0   69.94      .1       0   88.31      .1       0
Bank Sta=69.94,88.31
XS Rating Curve= 0 ,0
Exp/Cntr=0.3,0.1

Type RM Length L Ch R = 1 ,90.74239,26.56,23.04,20.43
XS GIS Cut Line= 6
     614786.2252    4340484.2169     614763.8158    4340461.5834
     614742.8308     4340450.395     614723.1998    4340435.9132
     614720.6886    4340424.0125     614690.0394    4340385.1384
#Sta/Elev= 30
       0  576.39     2.9  575.58    5.79  573.89   14.48  569.64   17.37   568.9
   20.27  568.55   28.96   567.9   31.85  567.72    37.8  567.66   43.74  567.22
   49.69  566.59   52.66  565.78   53.53565.6687   64.78  564.14   67.83  564.08
   73.93  564.52   83.07  564.66   86.11  564.94   92.19  565.12  100.93  564.26
  103.84  564.19  106.75  564.45  112.57  565.36  116.04565.6678   118.4  566.08
  121.31  566.88  127.13  568.77  130.04  569.87  132.96  571.16  141.69  575.79
#Mann= 3 , 0 , 0
       0      .1       0   53.53      .1       0  116.04      .1       0
Bank Sta=53.53,116.04
XS Rating Curve= 0 ,0
Exp/Cntr=0.3,0.1

Type RM Length L Ch R = 1 ,67.69831,17.17,17.9,18.89
XS GIS Cut Line= 5
     614796.3328    4340481.1991     614773.4727    4340436.7491
     614752.6764    4340425.4778     614731.5627     4340418.334
     614702.3526    4340374.8364
#Sta/Elev= 30
       0  577.47    14.7  569.33   17.64  567.95   20.58  567.22   26.46  566.73
    29.4  566.77   38.22  566.13    44.1  565.98   49.98     566   64.77   566.6
   73.64  566.68   76.42  565.95   77.13565.6268   79.21  564.68      82  564.44
   84.78  565.45   87.57  566.11   90.36  566.23   93.14  566.09   98.84  565.23
  107.57   564.6  113.39  564.71   116.3  565.02  119.39565.6276  125.04  566.92
  127.95  567.86  136.68  571.84   142.5  574.95  145.41  576.13  148.32  576.64
#Mann= 3 , 0 , 0
       0      .1       0   77.13      .1       0  119.39      .1       0
Bank Sta=77.13,119.39
XS Rating Curve= 0 ,0
Exp/Cntr=0.3,0.1

Type RM Length L Ch R = 1 ,49.79411,12.46,24.18,33.74
XS GIS Cut Line= 6
     614802.3344     4340475.515     614778.2573    4340423.6566
     614774.6854    4340418.4972     614766.2187    4340412.9409
     614736.9822    4340399.9763     614715.8155    4340369.8138
#Sta/Elev= 30
       0  575.53    3.01  573.93   12.04  568.79   15.05  567.32   18.06  566.43
   21.06  566.01   27.08  565.83   30.09   565.6   35.61565.4566   51.16  565.06
   63.45  565.11   71.05  565.65   79.39   565.9    82.3  565.64   85.21  564.98
   88.11   564.7   91.02  565.43   93.93   565.9   96.84  565.92  105.56  565.29
  108.63  565.27  109.75565.4561   111.7  565.78  117.84  567.12  120.91  567.89
  123.98  568.78  130.13  570.91  136.27  573.37  139.34  573.71  142.41  575.67
#Mann= 3 , 0 , 0
       0      .1       0   35.61      .1       0  109.75      .1       0
Bank Sta=35.61,109.75
XS Rating Curve= 0 ,0
Exp/Cntr=0.3,0.1

Type RM Length L Ch R = 1 ,25.61637,3.68,15.83,18.82
XS GIS Cut Line= 6
     614805.5094    4340473.7952      614779.051    4340413.9993
     614776.1406    4340403.1513     614766.6156    4340389.6575
     614764.7635    4340379.2065     614741.2156    4340354.6002
#Sta/Elev= 28
       0  575.13   11.89  568.52   14.86  567.05   17.83  566.07   20.81  565.66
   23.78  565.71   29.72  565.24   35.67  564.91   41.61  564.83   50.53  564.57
    53.5  564.66   56.47  564.61   71.69564.2429   76.62  564.11   84.88  564.36
   87.63  564.32   94.94   563.9   99.08  563.79  101.42  563.79  103.75  563.91
   105.5564.2427  106.59  564.45  109.43  565.37  112.27  566.39  117.94  568.15
  126.46  571.09  132.13  573.24  137.81  575.56
#Mann= 3 , 0 , 0
       0      .1       0   71.69      .1       0   105.5      .1       0
Bank Sta=71.69,105.5
XS Rating Curve= 0 ,0
Exp/Cntr=0.3,0.1