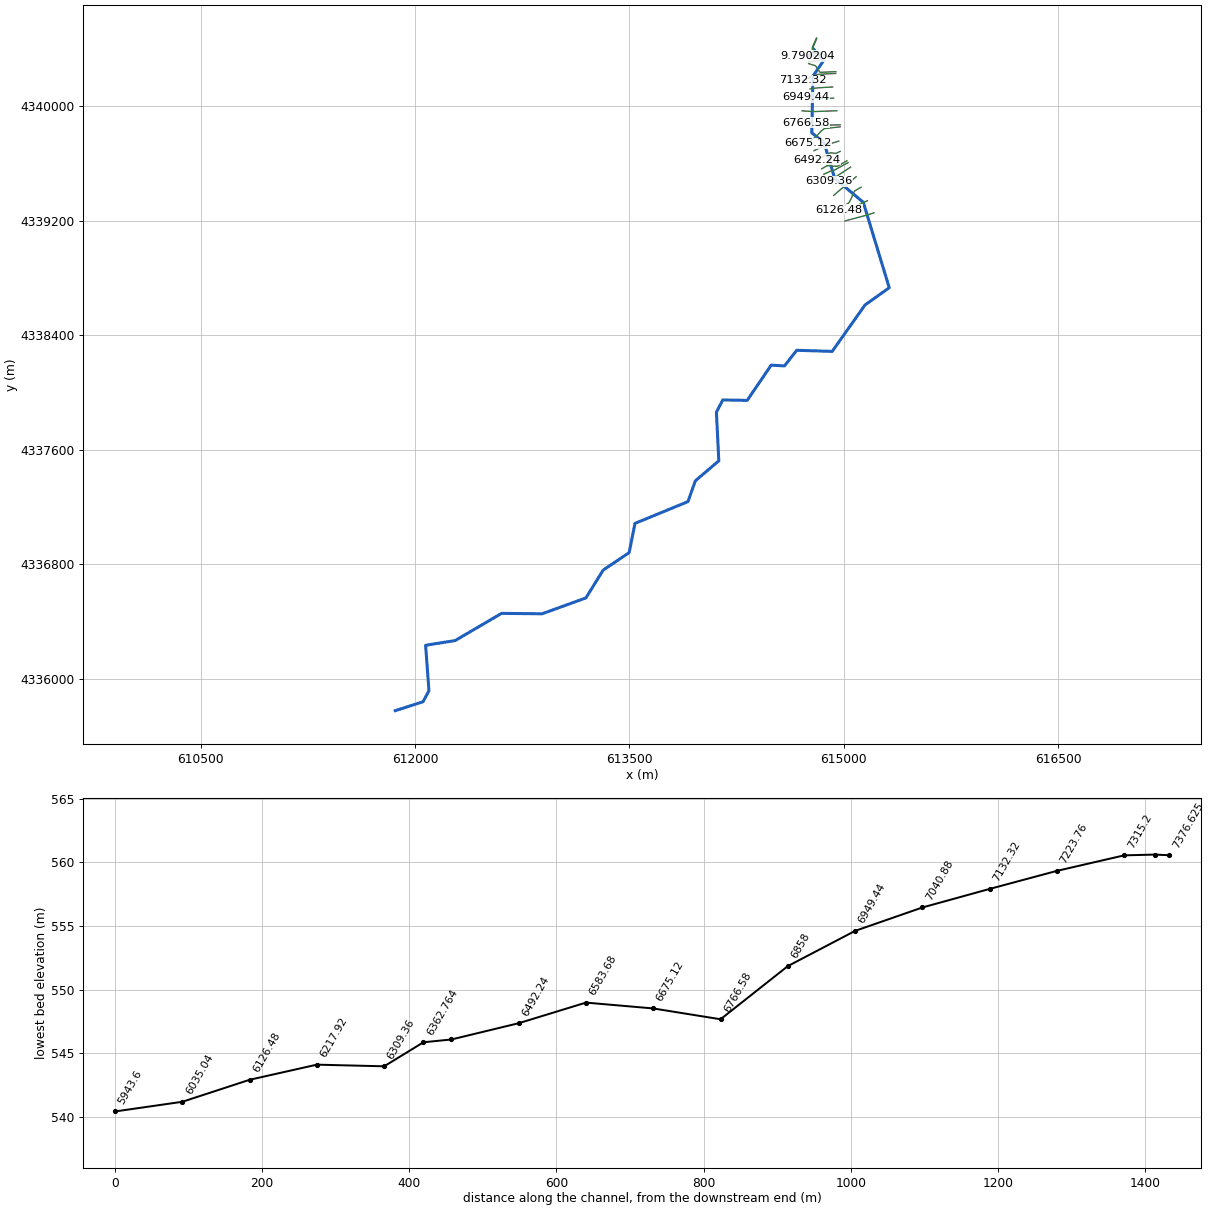
HEC-RAS study MinearRun.prj: MinearRun

--- MinearRun.g01 (geometry) --- (continued)

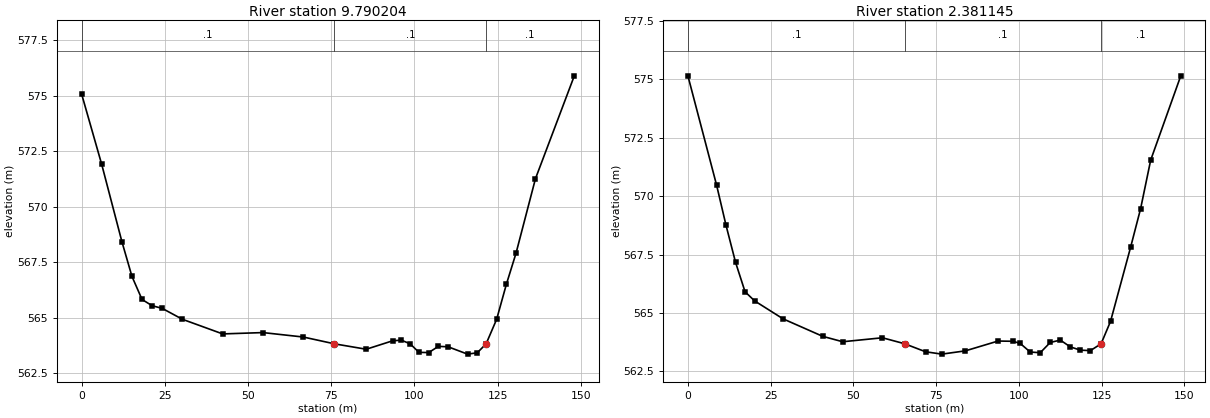
Type RM Length L Ch R = 1 ,9.790204,6.55,7.41,6.4
XS GIS Cut Line= 6
      614808.705    4340472.7552     614781.5852    4340411.9009
     614779.8654     4340401.053     614784.0987    4340383.0613
     614784.0987    4340377.7696     614747.6817    4340348.6075
#Sta/Elev= 28
       0  575.09    6.06  571.91   12.11  568.44   15.14  566.87   18.17  565.83
    21.2  565.55   24.23  565.43   30.28  564.94    42.4  564.28   54.51  564.34
   66.62  564.14   75.99 563.833   85.53  563.59   93.45  563.97   96.09     564
   98.74  563.83  101.38  563.45   104.3  563.44  107.21  563.72  110.13   563.7
  115.96  563.37  118.88  563.43  121.54563.8322  124.71  564.94  127.62  566.51
  130.54  567.92  136.37  571.27  148.04   575.9
#Mann= 3 , 0 , 0
       0      .1       0   75.99      .1       0  121.54      .1       0
Bank Sta=75.99,121.54
XS Rating Curve= 0 ,0
Exp/Cntr=0.3,0.1

Type RM Length L Ch R = 1 ,2.381145,3.23,2.38,6985.42
XS GIS Cut Line= 6
       614810.91    4340471.9916     614800.7236    4340445.1364
     614786.9652    4340415.1061     614787.0975    4340402.5384
      614791.882    4340381.4599     614750.1439     4340348.916
#Sta/Elev= 30
       0  575.13    8.62  570.48   11.49  568.75   14.36  567.17   17.23  565.91
   20.11  565.52   28.72  564.75   40.73     564   46.74  563.77   58.75  563.94
   65.43563.6853   71.81  563.34   76.69  563.24   83.81  563.38   93.68   563.8
   98.16  563.79  100.36   563.7   103.4  563.33  106.43   563.3  109.46  563.74
   112.5  563.84  115.53  563.55  118.56  563.41   121.6  563.39  124.82563.6838
  127.67  564.64  133.73  567.81  136.77  569.47   139.8  571.54   148.9  575.15
#Mann= 3 , 0 , 0
       0      .1       0   65.43      .1       0  124.82      .1       0
Bank Sta=65.43,124.82
XS Rating Curve= 0 ,0
Exp/Cntr=0.3,0.1

River Reach=Minear Run      ,1
Reach XY= 30
     614791.8493    4340392.8625     614860.5088    4340318.2499
614784.485673688  4340207.897208614776.638240182 4339812.2588788
     614861.6883    4339745.2618     614936.8412    4339494.8649
     615136.8607    4339326.9823     615318.4129    4338730.7414
     615148.8676     4338610.197     614919.2353    4338286.3463
      614670.791     4338293.887     614585.4627    4338184.7461
     614492.5938    4338190.3024     614324.3185    4337944.2394
     614153.6619    4337947.4144     614109.1555    4337861.7661
     614125.8806    4337521.9636     613961.9709     4337383.057
     613909.9801    4337237.4036     613539.2982    4337085.4002
     613498.4199     4336881.406     613316.7094    4336759.2345
     613196.0006     4336565.096     612889.6125    4336454.3677
     612605.8836    4336457.2243     612281.2019    4336267.4392
     612074.4296    4336234.4985     612097.8453    4335917.3947
     612056.5702    4335840.4008     611861.7042    4335777.6944

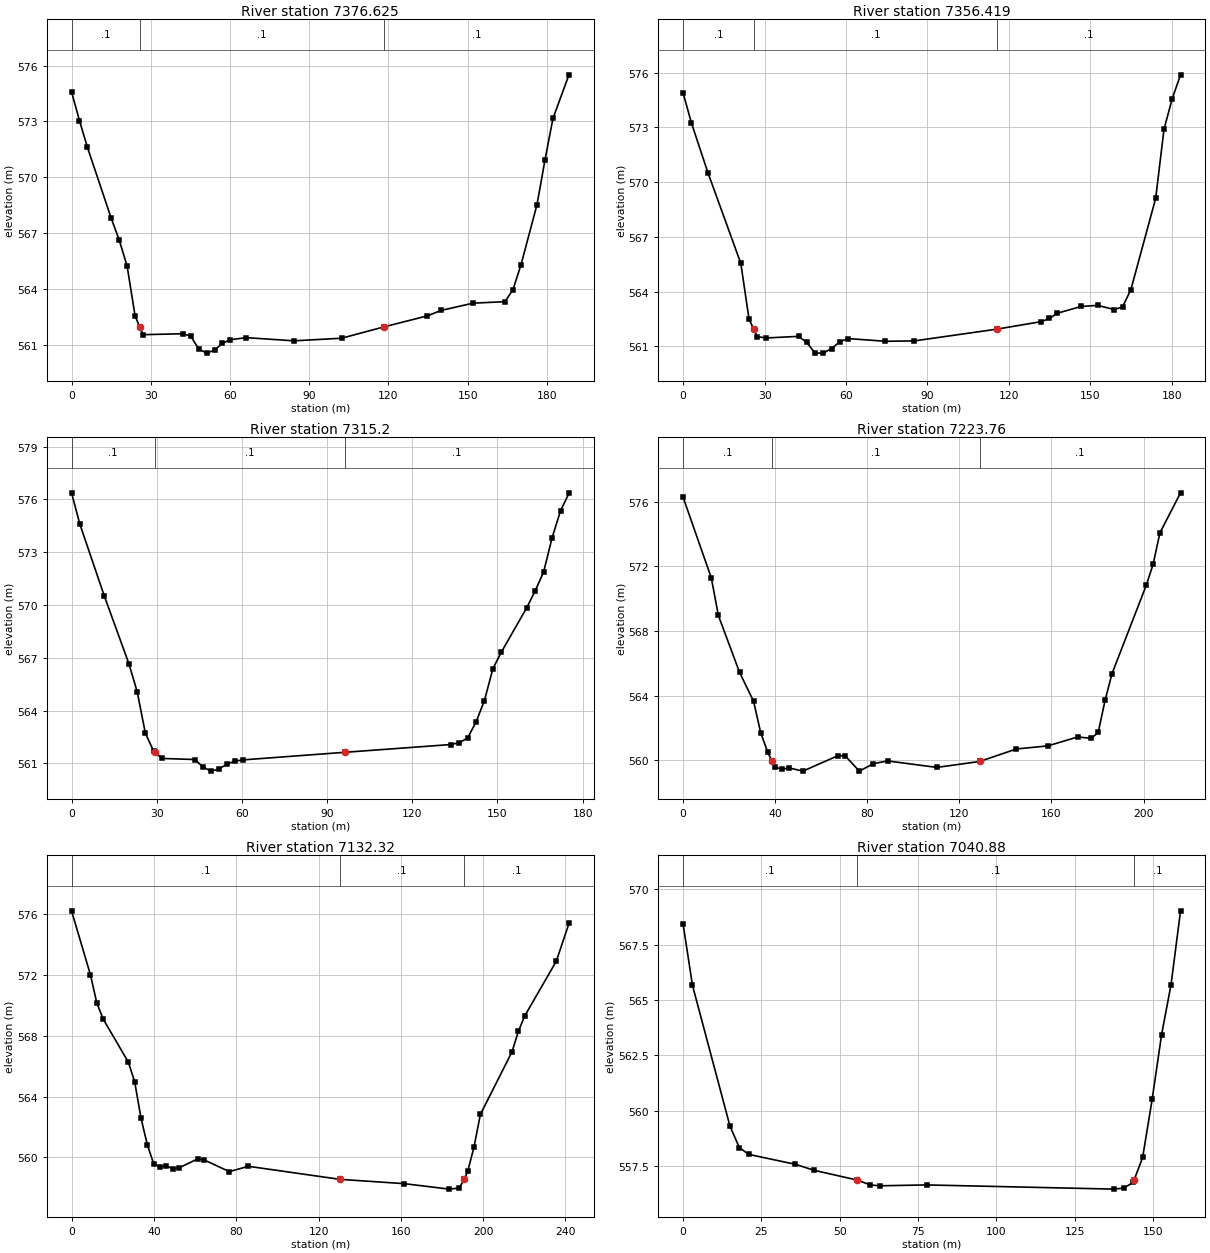
Type RM Length L Ch R = 1 ,7376.625,3.84,20.21,21.05
XS GIS Cut Line= 5
     614921.8183    4340334.0535      614816.461    4340378.4507
     614809.1585    4340371.4656     614796.4585    4340362.5756
     614750.4209    4340347.5473
#Sta/Elev= 30
       0  574.59    3.01  573.04    6.02  571.61   15.04   567.8   18.05  566.64
   21.06  565.23   24.07  562.56    25.8561.9852   27.08  561.56   42.12  561.61
   45.13  561.48   48.14   560.8   51.15  560.57   54.16  560.73   57.16   561.1
   60.17  561.29   66.19   561.4   84.24  561.23  102.29  561.37  118.49561.9846
  134.77  562.57  139.94  562.86  152.04  563.25  164.15  563.33  167.18  563.98
  170.21  565.31  176.26  568.53  179.29  570.93  182.31  573.16  188.37   575.5
#Mann= 3 , 0 , 0
       0      .1       0    25.8      .1       0  118.49      .1       0
Bank Sta=25.8,118.49
XS Rating Curve= 0 ,0
Exp/Cntr=0.3,0.1

Type RM Length L Ch R = 1 ,7356.419,24.59,41.22,36.09
XS GIS Cut Line= 6
     614921.9307    4340333.2703     614847.3181      4340362.11
     614832.5014     4340366.211     614814.2451    4340349.2776
      614787.919    4340348.8808     614751.5387    4340344.7797
#Sta/Elev= 30
       0  574.89    3.04  573.26    9.11  570.53   21.26  565.54   24.29  562.47
   26.01561.9382   27.33  561.53   30.37  561.45   42.51  561.54   45.55  561.21
   48.58  560.62   51.62  560.62   54.66  560.87   57.69  561.24   60.73  561.42
   74.49  561.27   85.12  561.29   115.6561.9369     132  562.35  134.92  562.52
  137.85  562.81  146.62  563.18  152.72  563.24  158.83  563.01  161.88  563.16
  164.93   564.1  174.08  569.12  177.13   572.9  180.18  574.59  183.23  575.89
#Mann= 3 , 0 , 0
       0      .1       0   26.01      .1       0   115.6      .1       0
Bank Sta=26.01,115.6
XS Rating Curve= 0 ,0
Exp/Cntr=0.3,0.1

Type RM Length L Ch R = 1 ,7315.2  ,115.4,91.44,62.82
XS GIS Cut Line= 6
     614923.7331    4340330.6606     614881.7077    4340341.3124
     614860.1677    4340333.5245     614844.8513    4340325.1005
     614818.2076    4340313.7957     614755.7658    4340310.6207
#Sta/Elev= 30
       0  576.37    2.89  574.61   11.56   570.5   20.23  566.65   23.12  565.07
   26.01  562.71    28.9   561.7   29.37561.6317   31.79  561.28   43.35  561.22
   46.22  560.81   49.08  560.56   51.94  560.68   54.81  560.97   57.67  561.13
   60.53   561.2   96.44561.6317  133.52  562.07   136.5  562.17  139.48  562.44
  142.45  563.34  145.43  564.57  148.41  566.38  151.39  567.32  160.32  569.84
   163.3   570.8  166.27  571.87  169.25  573.81  172.23  575.35   175.2  576.34
#Mann= 3 , 0 , 0
       0      .1       0   29.37      .1       0   96.44      .1       0
Bank Sta=29.37,96.44
XS Rating Curve= 0 ,0
Exp/Cntr=0.3,0.1

Type RM Length L Ch R = 1 ,7223.76 ,28.52,91.44,99.01
XS GIS Cut Line= 6
     614944.8998    4340239.3791     614834.7882      4340234.35
     614821.9166    4340250.4367     614809.1126     4340272.071
     614800.3923    4340280.9168     614754.8839    4340295.2043
#Sta/Elev= 30
       0  576.26   12.25  571.28   15.31  568.96   24.49  565.45   30.62  563.65
   33.68  561.72   36.74  560.51   38.69559.9365    39.8  559.61   42.87  559.45
   45.93  559.54   52.05  559.34   67.36   560.3   70.42  560.28   76.55  559.34
   82.67   559.8   88.79  559.97  110.23  559.57  128.78559.9354   144.8  560.71
  158.45   560.9  171.37  561.45  177.33  561.37  180.31  561.73   183.3  563.71
  186.28  565.35  201.18  570.82  204.16  572.12  207.14  574.07  216.09  576.54
#Mann= 3 , 0 , 0
       0      .1       0   38.69      .1       0  128.78      .1       0
Bank Sta=38.69,128.78
XS Rating Curve= 0 ,0
Exp/Cntr=0.3,0.1

Type RM Length L Ch R = 1 ,7132.32 ,94.7,91.44,84.91
XS GIS Cut Line= 6
     614944.2384    4340226.8114     614821.7178    4340220.4329
     614812.1927    4340216.0673     614775.3633    4340212.6856
     614760.0147    4340196.6551     614714.0504    4340179.1863
#Sta/Elev= 30
       0   576.2     9.2  571.99   12.27  570.15   15.34   569.1    27.6  566.26
   30.67  564.98   33.74  562.59   36.81  560.84   39.87   559.6   42.94  559.38
   46.01  559.45   49.07  559.27   52.14  559.31   61.34  559.91   64.41  559.84
   76.68  559.07   85.88  559.42  130.46558.5621  161.61  558.28  183.53  557.92
  188.31  557.99  190.84558.5604   192.5  559.09  195.58  560.71  198.65  562.83
  214.02  566.94  217.09  568.28  220.16  569.29  235.53  572.89  241.68  575.37
#Mann= 3 , 0 , 0
       0      .1       0  130.46      .1       0  190.84      .1       0
Bank Sta=130.46,190.84
XS Rating Curve= 0 ,0
Exp/Cntr=0.3,0.1

Type RM Length L Ch R = 1 ,7040.88 ,81.12,91.44,80.84
XS GIS Cut Line= 4
     614922.6172    4340132.2182     614827.1536    4340126.7722
     614803.4331    4340124.3014     614764.5141    4340118.7668
#Sta/Elev= 20
       0  568.42    2.99  565.66   14.94  559.31   17.93  558.34   20.92  558.03
   35.86  557.58   41.83  557.31   55.52556.8704   59.76  556.65   62.75  556.61
   77.69  556.65  137.61  556.46  140.63  556.51  143.66  556.76  143.95556.8685
  146.68  557.89  149.71  560.51  152.73  563.44  155.75   565.7  158.78  569.03
#Mann= 3 , 0 , 0
       0      .1       0   55.52      .1       0  143.95      .1       0
Bank Sta=55.52,143.95
XS Rating Curve= 0 ,0
Exp/Cntr=0.3,0.1

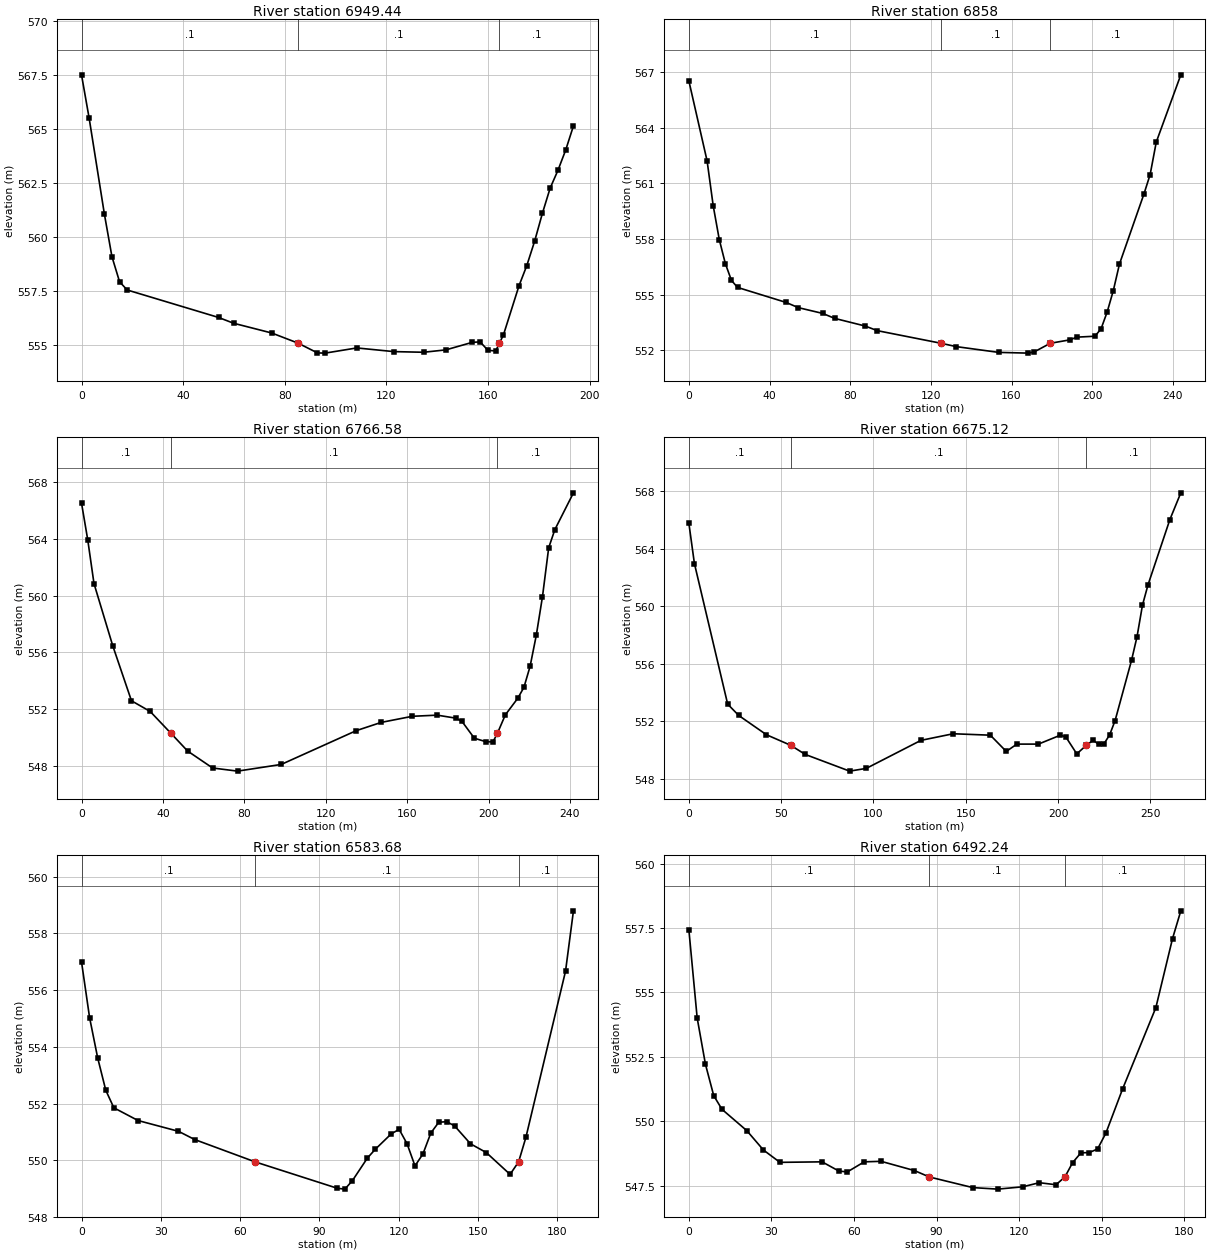
Type RM Length L Ch R = 1 ,6949.44 ,92.2,91.44,91.98
XS GIS Cut Line= 6
     614928.9716    4340054.3005     614827.1594    4340051.0485
     614821.5375    4340054.2897     614786.4796    4340054.0251
     614776.3781    4340051.3474     614737.6887    4340060.6328
#Sta/Elev= 30
       0  567.49       3  565.49    8.99  561.06   11.98  559.08   14.98  557.92
   17.98  557.54   53.93  556.27   59.92     556    74.9  555.55   85.28555.0803
   92.88  554.63   95.87  554.62  108.35  554.86  122.96  554.69  134.65  554.66
  143.41  554.77  153.86  555.12  156.92  555.14  159.98  554.75  163.04  554.72
  164.51555.0791  166.11  555.47  172.23  557.74  175.29  558.67  178.35  559.79
  181.41  561.08  184.47  562.25  187.53  563.07  190.59  564.01  193.65  565.13
#Mann= 3 , 0 , 0
       0      .1       0   85.28      .1       0  164.51      .1       0
Bank Sta=85.28,164.51
XS Rating Curve= 0 ,0
Exp/Cntr=0.3,0.1

Type RM Length L Ch R = 1 ,6858    ,97.76,91.42,90.44
XS GIS Cut Line= 4
     614951.9301    4339966.5014     614804.3427    4339960.8563
     614768.9503    4339961.6607     614708.2472    4339965.7377
#Sta/Elev= 30
       0  566.51    9.04   562.2   12.06  559.79   15.07  557.97   18.09  556.67
    21.1  555.77   24.11  555.39   48.23  554.58   54.26   554.3   66.31  553.99
   72.34  553.72   87.41  553.31   93.44  553.06  125.11552.3798  132.62   552.2
   153.6  551.89  168.35  551.85   171.3  551.92  179.21552.3801  189.18  552.57
  192.22  552.71  201.35  552.76  204.39  553.16  207.43  554.07  210.47  555.22
  213.52  556.65  225.68  560.43  228.73  561.47  231.77  563.22  243.94  566.84
#Mann= 3 , 0 , 0
       0      .1       0  125.11      .1       0  179.21      .1       0
Bank Sta=125.11,179.21
XS Rating Curve= 0 ,0
Exp/Cntr=0.3,0.1

Type RM Length L Ch R = 1 ,6766.58 ,38.34,91.46,98.28
XS GIS Cut Line= 3
     614974.9477    4339868.1062     614806.3292    4339863.4347
     614736.0285    4339883.1875
#Sta/Elev= 30
       0  566.49    3.07   563.9    6.13  560.84   15.33  556.48   24.54  552.61
   33.74  551.86   43.84550.3406   52.14  549.08   64.41  547.89   76.67  547.67
   98.14  548.14  134.95  550.51  147.21  551.09  162.55  551.52  174.77   551.6
   183.9  551.39  186.94  551.16  193.02  549.98  198.62  549.74  202.15  549.72
  204.39 550.339  208.24  551.62  214.32  552.78  217.37  553.55  220.41  555.03
  223.45  557.21  226.49  559.92  229.54  563.35  232.58  564.63  241.71  567.21
#Mann= 3 , 0 , 0
       0      .1       0   43.84      .1       0  204.39      .1       0
Bank Sta=43.84,204.39
XS Rating Curve= 0 ,0
Exp/Cntr=0.3,0.1

Type RM Length L Ch R = 1 ,6675.12 ,109.06,91.44,84.63
XS GIS Cut Line= 5
     614974.9477    4339853.8187     614864.4877    4339841.6965
     614841.2438    4339823.9856      614812.361     4339791.971
     614747.9348    4339739.5185
#Sta/Elev= 30
       0  565.76       3  562.96   21.02  553.18   27.03  552.39   42.05  551.05
   55.13550.3194   63.07  549.68    87.1  548.52   96.11  548.71  125.73  550.66
  143.22  551.12  163.34  551.02  171.97  549.89  177.71   550.4   189.4   550.4
  201.27  551.02  204.23   550.9  210.17  549.72  215.37550.3198  219.07  550.67
  222.04  550.38     225  550.44  227.97  551.04  230.94  552.04  239.84  556.23
  242.81  557.87  245.77  560.07  248.74  561.47  260.61  566.02  266.54  567.88
#Mann= 3 , 0 , 0
       0      .1       0   55.13      .1       0  215.37      .1       0
Bank Sta=55.13,215.37
XS Rating Curve= 0 ,0
Exp/Cntr=0.3,0.1

Type RM Length L Ch R = 1 ,6583.68 ,80.25,91.44,68.51
XS GIS Cut Line= 4
     614965.1285    4339754.0368     614885.8765    4339730.7853
     614862.1109    4339721.1446     614791.7432     4339687.558
#Sta/Elev= 30
       0     557    3.06  555.03    6.12  553.61    9.18  552.47   12.24  551.85
   21.41   551.4   36.71  551.02   42.83  550.73   65.72549.9413   96.84  549.01
   99.69  548.98  102.54  549.28  108.24  550.08  111.24  550.39  117.24  550.93
  120.23  551.09  123.23  550.58  126.23   549.8  129.23  550.22  132.23  550.96
  135.23  551.34  138.23  551.36  141.23  551.21  147.23  550.58  153.22  550.27
  162.22   549.5  165.45549.9421  168.22  550.81  183.21  556.67  186.21   558.8
#Mann= 3 , 0 , 0
       0      .1       0   65.72      .1       0  165.45      .1       0
Bank Sta=65.72,165.45
XS Rating Curve= 0 ,0
Exp/Cntr=0.3,0.1

Type RM Length L Ch R = 1 ,6492.24 ,91.03,91.44,89.14
XS GIS Cut Line= 4
     614975.3913    4339682.3137     614945.2024    4339668.7588
     614905.5935    4339672.7197     614811.7473    4339623.7682
#Sta/Elev= 30
       0  557.43    3.01  554.01    6.02  552.21    9.03  550.99   12.03  550.46
   21.06  549.63   27.08  548.88   33.09   548.4    48.4  548.42   54.53  548.06
   57.59  548.03   63.71  548.42   69.84  548.44   81.97  548.08   87.39547.8313
  103.14  547.42  112.21  547.36  121.29  547.45  127.33  547.61  133.38  547.53
  136.62547.8317  139.43  548.39  142.45  548.77  145.48  548.78   148.5  548.92
  151.53  549.54  157.58  551.25  169.67  554.41  175.72  557.09  178.74  558.17
#Mann= 3 , 0 , 0
       0      .1       0   87.39      .1       0  136.62      .1       0
Bank Sta=87.39,136.62
XS Rating Curve= 0 ,0
Exp/Cntr=0.3,0.1

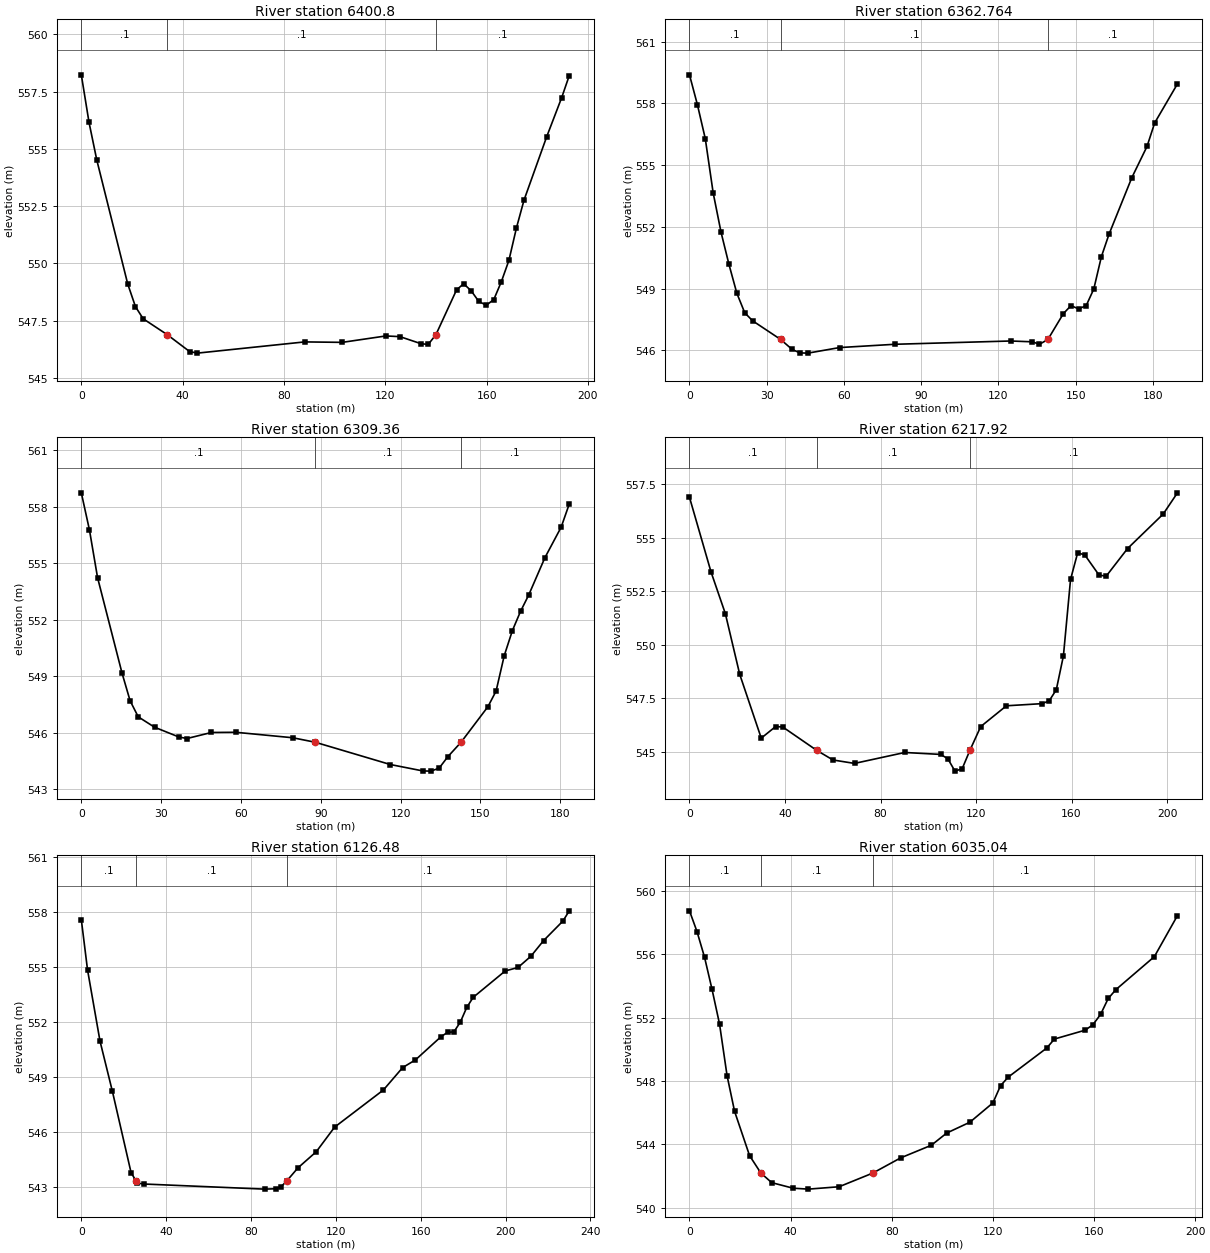
Type RM Length L Ch R = 1 ,6400.8  ,26.4,38.04,41.19
XS GIS Cut Line= 6
     615022.1906    4339616.7443     614956.1175    4339578.5458
     614920.5575    4339579.3598     614901.4602    4339583.0861
     614881.9018    4339582.1177     614846.0246    4339560.8701
#Sta/Elev= 29
       0  558.23    3.05  556.15    6.11  554.51   18.32   549.1   21.37  548.11
   24.42  547.58   33.97546.8818   42.74  546.15   45.79  546.08   88.18  546.57
     103  546.55  120.23  546.83  125.79   546.8  134.14  546.49  136.94  546.46
  139.97546.8818  148.13  548.84  150.93  549.11  153.91   548.8  156.89  548.34
  159.86  548.17  162.84  548.42  165.82   549.2   168.8  550.13  171.78  551.55
  174.76  552.76  183.69  555.52  189.65  557.24  192.63   558.2
#Mann= 3 , 0 , 0
       0      .1       0   33.97      .1       0  139.97      .1       0
Bank Sta=33.97,139.97
XS Rating Curve= 0 ,0
Exp/Cntr=0.3,0.1

Type RM Length L Ch R = 1 ,6362.764,43.91,53.4,54.47
XS GIS Cut Line= 6
     615030.7603    4339604.2333     614931.1444    4339549.8613
     614911.9886    4339545.1517     614903.8923    4339543.5642
     614900.7173    4339541.5005     614860.4609    4339522.9664
#Sta/Elev= 30
       0  559.39    3.07  557.94    6.13  556.29     9.2  553.65   12.27  551.73
   15.34  550.17    18.4  548.77   21.47  547.82   24.54  547.43   35.42546.5239
   39.87  546.04   42.94  545.87   46.01  545.86   58.28  546.13   79.75  546.29
  124.76  546.45  133.21  546.41  135.96  546.29  139.23546.5236  145.25  547.78
  148.21  548.17  151.16  548.01  154.12  548.17  157.07  548.98  160.02  550.55
  162.98  551.64  171.84  554.39  177.75  555.91  180.71  557.05  189.57  558.95
#Mann= 3 , 0 , 0
       0      .1       0   35.42      .1       0  139.23      .1       0
Bank Sta=35.42,139.23
XS Rating Curve= 0 ,0
Exp/Cntr=0.3,0.1

Type RM Length L Ch R = 1 ,6309.36 ,88.47,91.44,92.2
XS GIS Cut Line= 2
     615048.0692    4339572.8479     614894.4643    4339472.6714
#Sta/Elev= 28
       0  558.73    3.06  556.76    6.11  554.23   15.28  549.18   18.34   547.7
   21.39  546.85   27.51   546.3   36.68  545.78   39.73   545.7    48.9  546.02
   58.07  546.03   79.47  545.74   87.95545.5003  116.14  544.32  128.37  543.98
  131.43  543.97  134.48  544.13  137.77  544.74   142.7 545.501  152.82  547.39
  155.88  548.22  158.93  550.09  161.99  551.42  165.05  552.44   168.1   553.3
  174.22  555.29  180.33  556.91  183.38  558.14
#Mann= 3 , 0 , 0
       0      .1       0   87.95      .1       0   142.7      .1       0
Bank Sta=87.95,142.7
XS Rating Curve= 0 ,0
Exp/Cntr=0.3,0.1

Type RM Length L Ch R = 1 ,6217.92 ,79.53,91.44,95.56
XS GIS Cut Line= 4
     615086.9543    4339505.7853     614998.9218    4339433.0556
     614986.3529    4339423.8952     614929.7568    4339375.2703
#Sta/Elev= 30
       0  556.88    9.01   553.4   15.02  551.45   21.03  548.62   30.05  545.64
   36.06  546.18   39.06  546.16   53.21545.0745    60.1  544.62   69.11  544.46
   90.15  544.97  105.17  544.88  108.18  544.68  111.18   544.1  114.19  544.21
  117.45545.0743  121.97  546.18  132.73  547.15  147.65  547.25  150.64  547.38
  153.62   547.9   156.6  549.48  159.59  553.05  162.57  554.29  165.56  554.19
  171.53  553.25  174.51   553.2  183.47  554.49  198.39   556.1  204.36  557.09
#Mann= 3 , 0 , 0
       0      .1       0   53.21      .1       0  117.45      .1       0
Bank Sta=53.21,117.45
XS Rating Curve= 0 ,0
Exp/Cntr=0.3,0.1

Type RM Length L Ch R = 1 ,6126.48 ,96.45,91.44,76.2
XS GIS Cut Line= 6
     615121.3357    4339432.4955     615075.7976    4339405.8167
     615060.4673    4339375.8865     615055.9232    4339360.8342
     615037.2787     4339325.108     614964.6819    4339276.0513
#Sta/Elev= 30
       0  557.61    2.93  554.87     8.8  550.99   14.66  548.24   23.46  543.81
   25.69543.3762   26.39  543.24   29.32  543.19   86.41  542.91   91.65  542.93
   94.27  543.05      97543.3772  102.13  544.07  110.76  544.95   119.4  546.29
  142.43  548.32  151.49  549.54  157.53  549.96  169.62  551.23  172.64  551.46
  175.66  551.49  178.68  552.02   181.7  552.82  184.73  553.37  199.83  554.81
  205.87     555  211.92  555.61  217.96  556.47  227.02  557.53  230.04  558.09
#Mann= 3 , 0 , 0
       0      .1       0   25.69      .1       0      97      .1       0
Bank Sta=25.69,97
XS Rating Curve= 0 ,0
Exp/Cntr=0.3,0.1

Type RM Length L Ch R = 1 ,6035.04 ,92.24,91.44,87.52
XS GIS Cut Line= 4
     615165.4776     4339338.319     615138.5001    4339325.8717
     615127.8799    4339322.2762     614994.7651    4339248.7463
#Sta/Elev= 30
       0  558.74    2.97  557.43    5.94  555.82    8.91  553.79   11.88   551.6
   14.86  548.34   17.83  546.09   23.77  543.29   28.24542.1929   32.51  541.59
   40.92  541.24   47.01  541.18   59.17  541.33   72.52542.1938    83.5  543.15
   95.67  543.95  101.75  544.72  110.88   545.4     120  546.62  123.04  547.71
  126.08  548.25  141.29  550.08  144.33  550.65   156.5  551.21  159.54  551.55
  162.58   552.2  165.62  553.21  168.66  553.77  183.87  555.85     193  558.44
#Mann= 3 , 0 , 0
       0      .1       0   28.24      .1       0   72.52      .1       0
Bank Sta=28.24,72.52
XS Rating Curve= 0 ,0
Exp/Cntr=0.3,0.1

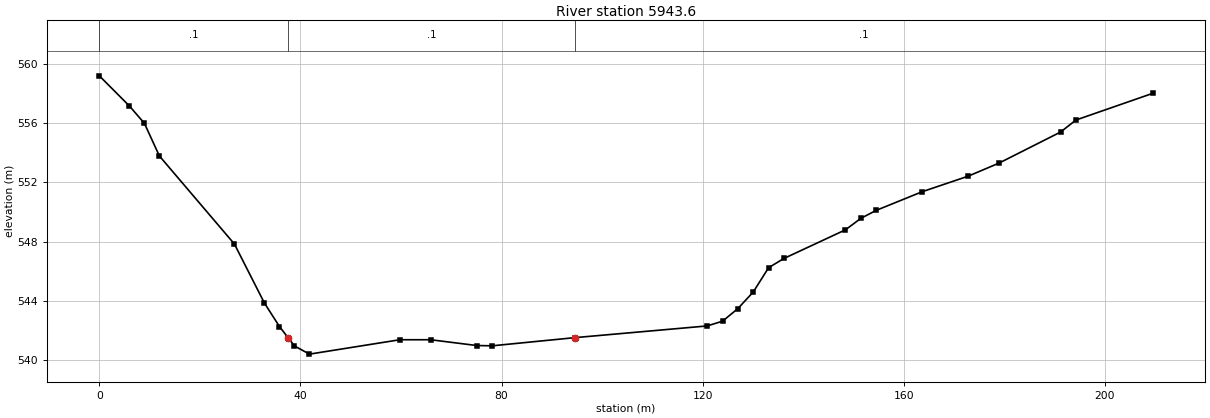
Type RM Length L Ch R = 1 ,5943.6  ,92.43,91.44,86.01
XS GIS Cut Line= 3
     615211.6135    4339253.5264     615157.4438      4339236.69
     615009.8463    4339197.1524
#Sta/Elev= 30
       0  559.18    5.97  557.15    8.96  555.98   11.94  553.78   26.87  547.84
   32.84  543.86   35.83  542.28   37.54541.5283   38.81  540.97    41.8  540.42
   59.78  541.39   65.89  541.39   75.06     541   78.12  540.98   94.55541.5302
   120.9  542.32  123.96  542.64  127.01  543.49  130.07  544.61  133.13  546.25
  136.18  546.87  148.41   548.8  151.46  549.57  154.52  550.11  163.69  551.37
  172.85  552.42  178.97   553.3  191.19  555.39  194.25   556.2  209.53     558
#Mann= 3 , 0 , 0
       0      .1       0   37.54      .1       0   94.55      .1       0
Bank Sta=37.54,94.55
XS Rating Curve= 0 ,0
Exp/Cntr=0.3,0.1