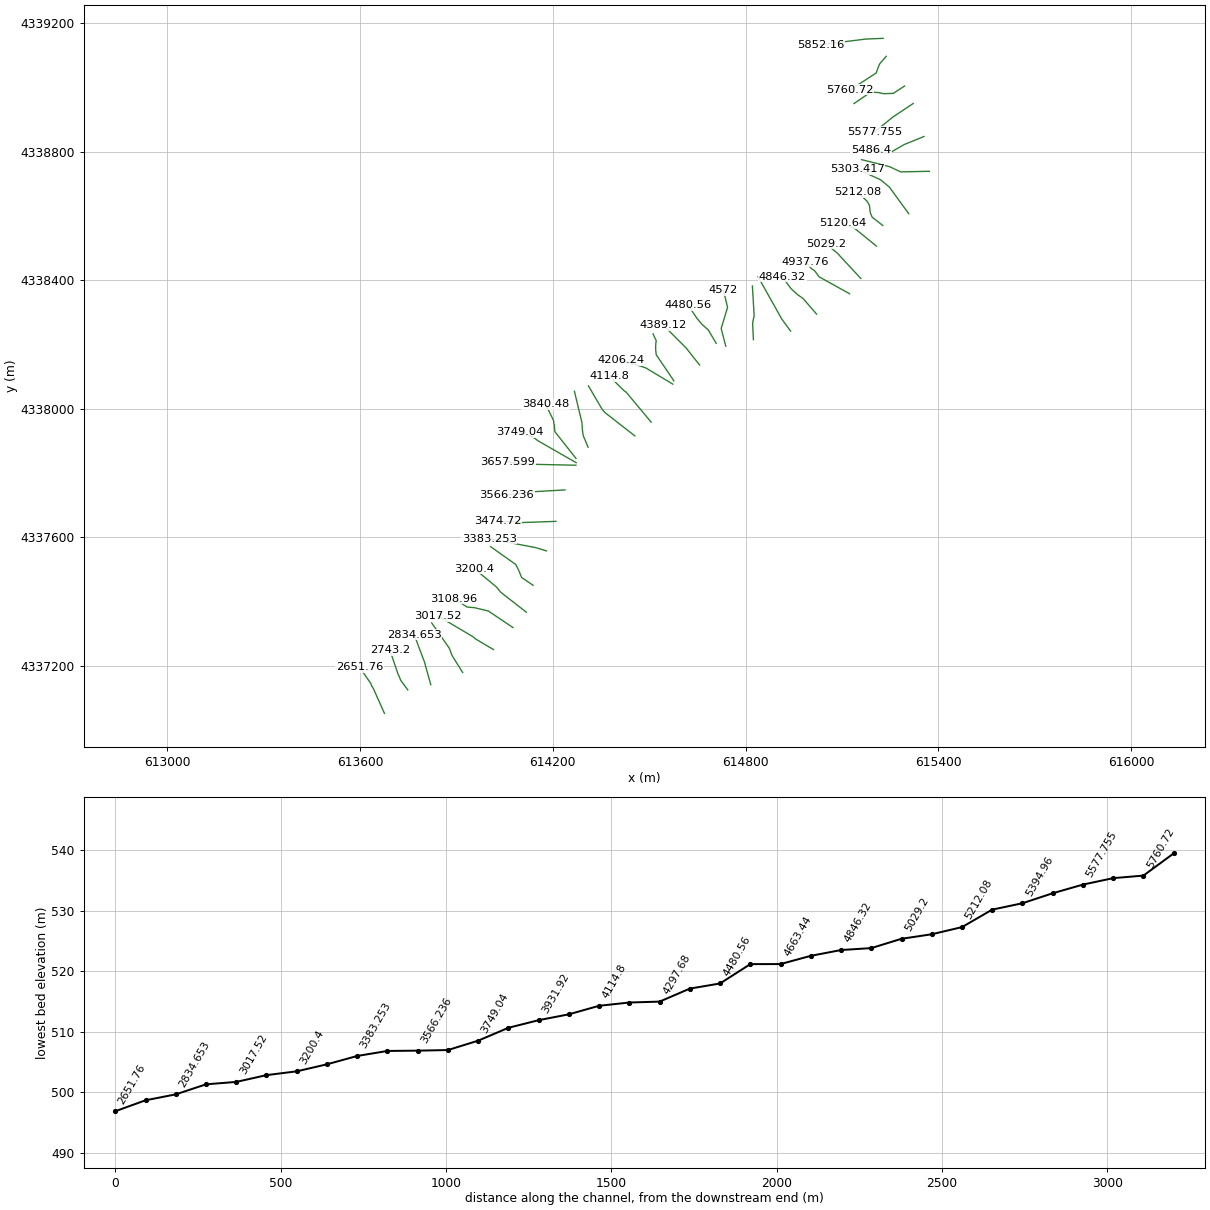
HEC-RAS study MinearRun.prj: MinearRun

--- MinearRun.g01 (geometry) --- (continued)

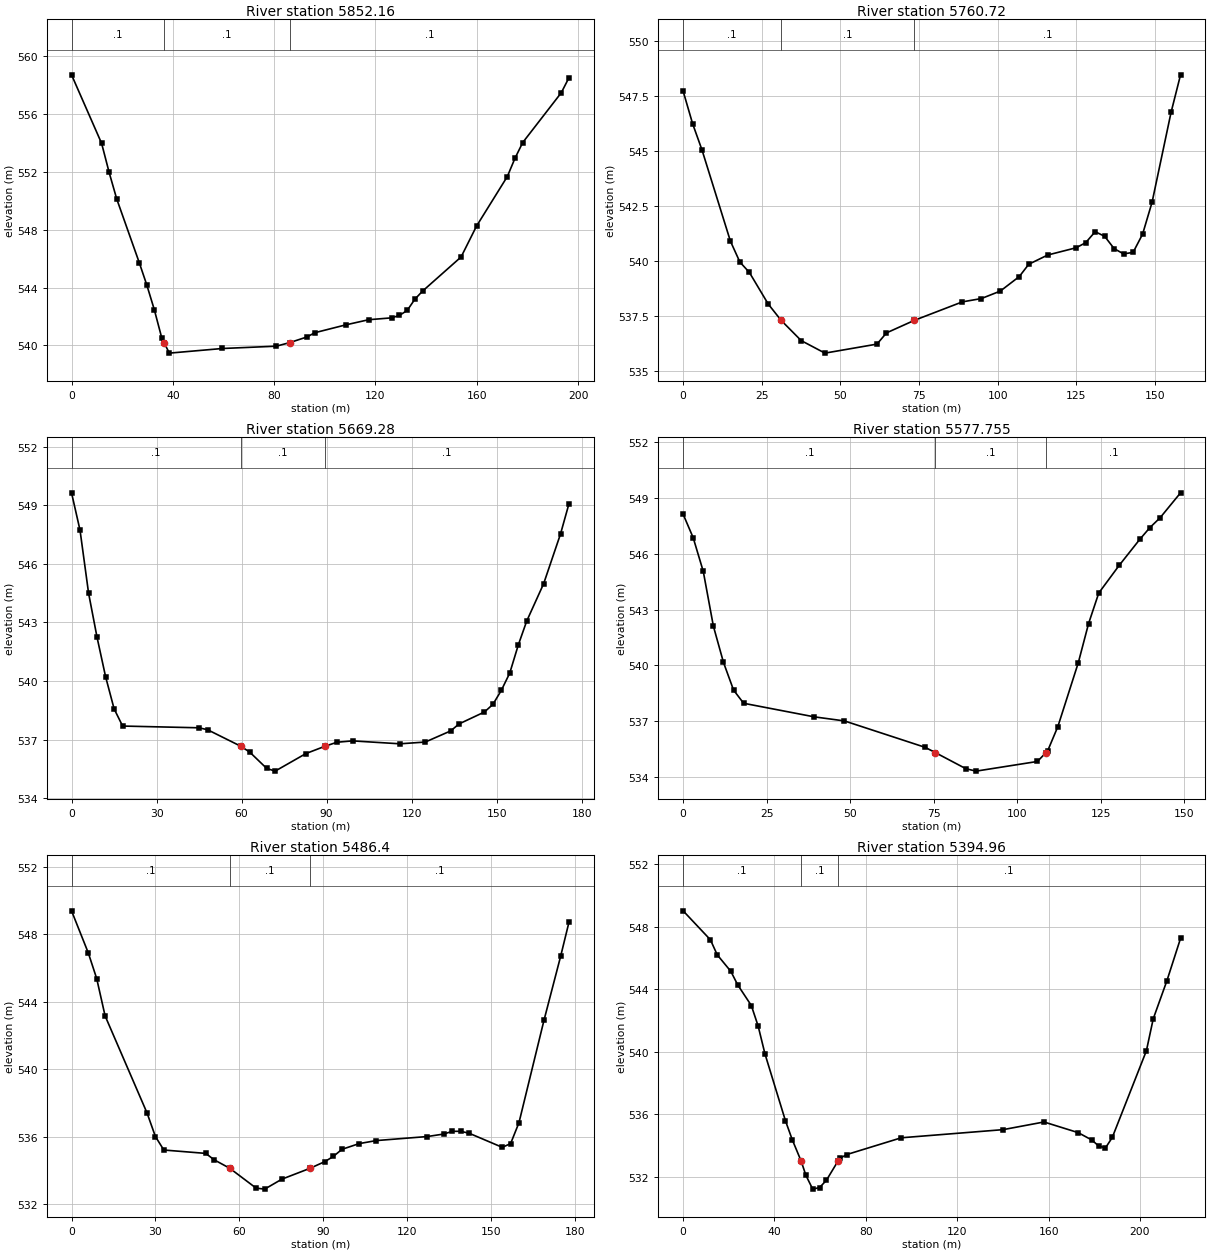
Type RM Length L Ch R = 1 ,5852.16 ,82.91,91.44,114.81
XS GIS Cut Line= 3
     615228.1279    4339152.7064     615174.7194    4339150.4809
     615032.8651    4339132.8585
#Sta/Elev= 29
       0  558.71   11.88  553.97   14.85  551.96   17.82  550.14   26.73  545.73
    29.7  544.19   32.67  542.48   35.64  540.51   36.54540.1948   38.61  539.47
   59.54  539.79   80.83  539.95   86.08540.1936   92.99  540.59   96.03  540.88
   108.2  541.42  117.32  541.78  126.45  541.91  129.49  542.08  132.53  542.42
  135.57   543.2  138.61  543.76  153.82  546.12   159.9  548.25  172.07  551.68
  175.11  552.95  178.15  554.03  193.36  557.47   196.4  558.51
#Mann= 3 , 0 , 0
       0      .1       0   36.54      .1       0   86.08      .1       0
Bank Sta=36.54,86.08
XS Rating Curve= 0 ,0
Exp/Cntr=0.3,0.1

Type RM Length L Ch R = 1 ,5760.72 ,99.62,91.44,80.9
XS GIS Cut Line= 5
     615237.8288    4339096.7717     615218.0803    4339074.1021
      615215.064    4339068.0696     615206.4756     4339044.781
     615125.5829    4338992.1703
#Sta/Elev= 30
       0  547.71    3.01  546.23    6.01  545.03   15.03  540.89   18.04  539.94
   21.05  539.47   27.06  538.03   31.15537.2906   37.53  536.37   45.08   535.8
   61.63  536.21   64.65  536.72   73.53537.2915   88.77  538.13    94.8  538.28
  100.83  538.62  106.86  539.28  109.88  539.84  115.91  540.26  124.96  540.59
  127.97  540.82  130.99  541.32     134  541.11  137.02  540.55  140.03  540.31
  143.05  540.38  146.07  541.21  149.08  542.66  155.11  546.74  158.13  548.45
#Mann= 3 , 0 , 0
       0      .1       0   31.15      .1       0   73.53      .1       0
Bank Sta=31.15,73.53
XS Rating Curve= 0 ,0
Exp/Cntr=0.3,0.1

Type RM Length L Ch R = 1 ,5669.28 ,72.58,91.53,100.86
XS GIS Cut Line= 6
     615294.8455     4339004.242     615259.5247    4338981.4241
     615229.7779    4338980.3848     615213.8655    4338983.9209
     615189.1454    4338985.1283     615137.5285    4338949.6964
#Sta/Elev= 30
       0  549.64       3  547.72    6.01   544.5    9.01  542.23   12.01  540.22
   15.02  538.57   18.02  537.69   45.03   537.6      48   537.5   59.73536.6539
   62.89  536.35   68.84  535.52   71.82  535.38   82.68  536.28    89.4536.6545
   93.62  536.86   99.12  536.93  115.85  536.78  124.79  536.87  133.73  537.44
  136.72   537.8  145.66  538.41  148.64   538.8  151.62  539.52   154.6  540.41
  157.59  541.84  160.57  543.07  166.53  544.98  172.49  547.53  175.47  549.08
#Mann= 3 , 0 , 0
       0      .1       0   59.73      .1       0    89.4      .1       0
Bank Sta=59.73,89.4
XS Rating Curve= 0 ,0
Exp/Cntr=0.3,0.1

Type RM Length L Ch R = 1 ,5577.755,95.77,91.36,97.43
XS GIS Cut Line= 3
     615321.8451    4338949.9709     615259.0811    4338908.1415
     615201.9783    4338862.0129
#Sta/Elev= 25
       0  548.13    3.02  546.86    6.03  545.05    9.05  542.11   12.07  540.16
   15.09  538.67    18.1  537.96   39.22  537.23   48.27  537.01   72.41  535.59
   75.48535.3055    84.6  534.44   87.66  534.31  106.01  534.83  108.56 535.305
  109.07   535.4  112.13  536.71  118.25  540.15   121.3  542.24  124.36  543.89
  130.48  545.38   136.6  546.77  139.66  547.41  142.72  547.94  148.83  549.28
#Mann= 3 , 0 , 0
       0      .1       0   75.48      .1       0  108.56      .1       0
Bank Sta=75.48,108.56
XS Rating Curve= 0 ,0
Exp/Cntr=0.3,0.1

Type RM Length L Ch R = 1 ,5486.4  ,92.4,91.44,63.71
XS GIS Cut Line= 4
      615355.437    4338847.1962     615294.2623    4338822.3954
      615246.279    4338794.9765     615190.3366    4338803.8044
#Sta/Elev= 30
       0  549.39       6  546.89       9  545.37      12  543.16      27   537.4
      30     536   33.01   535.2   48.01     535   51.01  534.62   56.59534.1178
   66.01  532.94   69.08  532.88   75.22  533.47   85.33534.1174   90.57  534.51
   93.64  534.82   96.71  535.24  102.85  535.58  108.99  535.76  127.24     536
   133.2  536.15  136.18  536.31  139.16  536.31  142.14   536.2  154.06  535.36
  157.04  535.58  160.03  536.82  168.97  542.89  174.93  546.69  177.91  548.71
#Mann= 3 , 0 , 0
       0      .1       0   56.59      .1       0   85.33      .1       0
Bank Sta=56.59,85.33
XS Rating Curve= 0 ,0
Exp/Cntr=0.3,0.1

Type RM Length L Ch R = 1 ,5394.96 ,94.99,91.54,55.25
XS GIS Cut Line= 4
      615372.377    4338738.9247     615282.8197    4338737.0593
     615247.9183    4338753.3859     615160.9735    4338775.2741
#Sta/Elev= 30
       0  549.01   11.94  547.16   14.93   546.2    20.9  545.14   23.89  544.28
   29.86  542.96   32.84  541.65   35.83  539.87   44.79   535.6   47.77  534.39
   51.68533.0169   53.75  532.11   56.73  531.23   59.72  531.33    62.7  531.79
   67.78533.0164   68.68   533.2   71.66  533.44    95.5  534.51  140.06  535.03
  157.99  535.52  172.94  534.84  178.91  534.37   181.9  533.99  184.89  533.86
  187.88  534.53  202.82  540.07  205.81  542.11  211.79  544.54  217.77  547.25
#Mann= 3 , 0 , 0
       0      .1       0   51.68      .1       0   67.78      .1       0
Bank Sta=51.68,67.78
XS Rating Curve= 0 ,0
Exp/Cntr=0.3,0.1

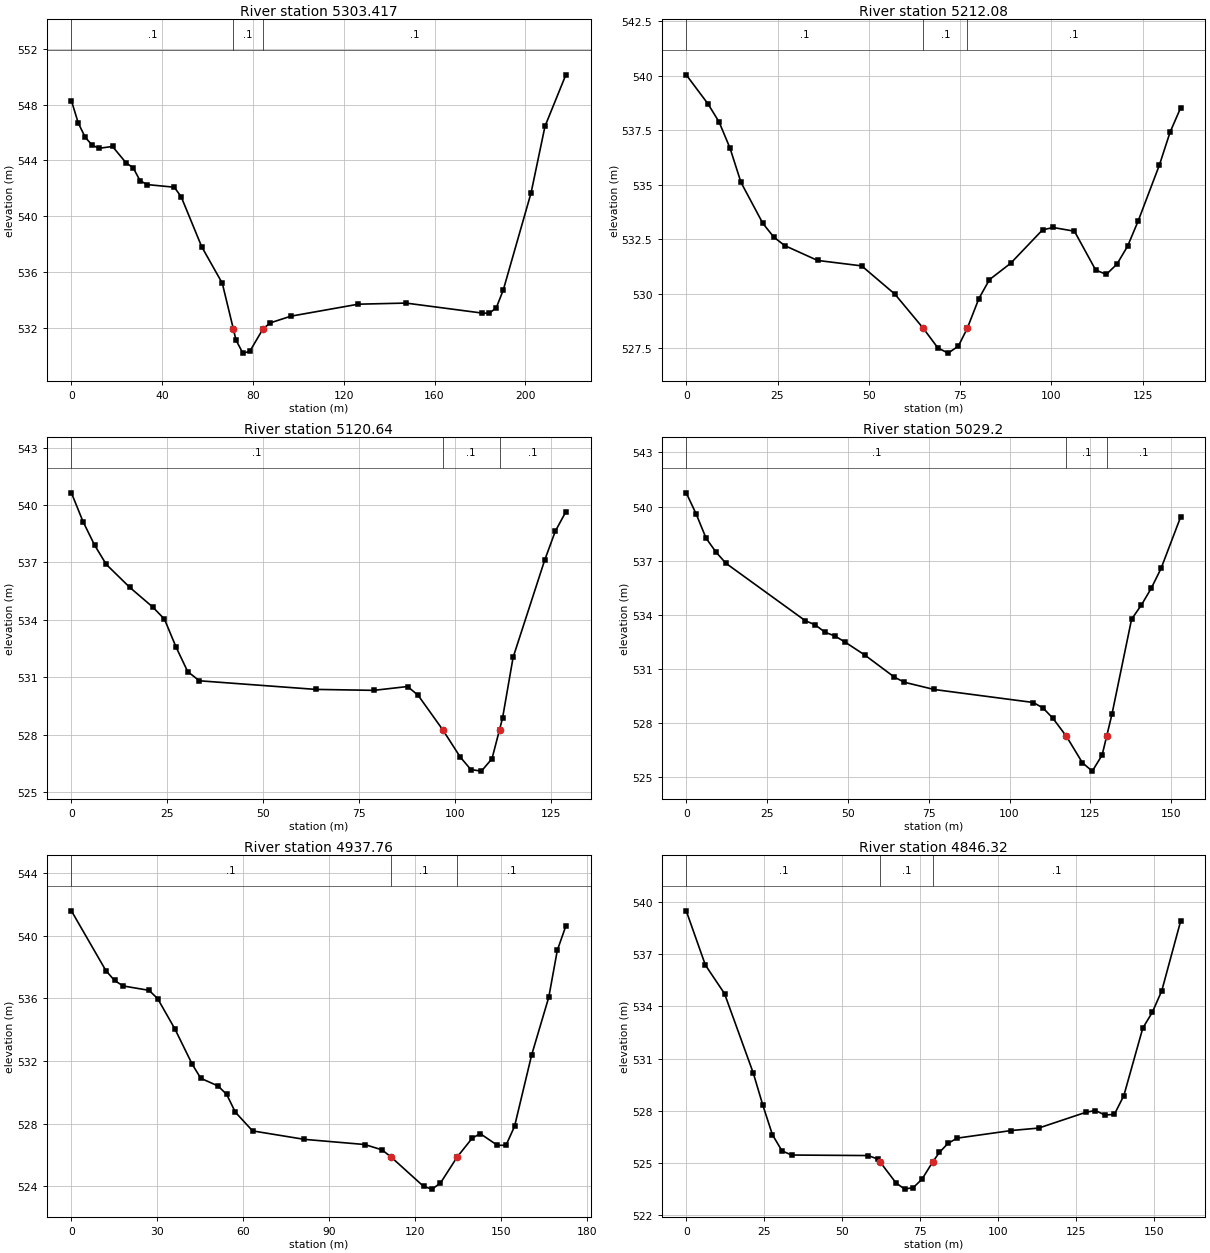
Type RM Length L Ch R = 1 ,5303.417,97.43,91.34,83.04
XS GIS Cut Line= 4
     615307.8119     4338606.954     615247.3752    4338690.0601
     615220.0047      4338712.64     615147.5875     4338745.745
#Sta/Elev= 30
       0  548.28    3.02  546.68    6.04  545.66    9.07   545.1   12.09  544.86
   18.13  544.99   24.18   543.8    27.2  543.47   30.22  542.55   33.25  542.26
   45.33  542.07   48.36  541.39   57.42   537.8   66.49  535.18   71.34531.9198
   72.54   531.1   75.56  530.17   78.58  530.29   84.46531.9166   87.65  532.34
   96.71  532.82  126.41  533.68  147.43  533.76  181.12  533.04  184.18  533.03
  187.24  533.43   190.3   534.7  202.55  541.67  208.68  546.44  217.87  550.13
#Mann= 3 , 0 , 0
       0      .1       0   71.34      .1       0   84.46      .1       0
Bank Sta=71.34,84.46
XS Rating Curve= 0 ,0
Exp/Cntr=0.3,0.1

Type RM Length L Ch R = 1 ,5212.08 ,69.16,91.44,95.89
XS GIS Cut Line= 6
     615227.0044    4338570.2112     615194.0434    4338596.1824
     615188.0562    4338610.1579     615185.4979    4338632.7384
     615178.5311    4338645.4798     615149.0616    4338673.6292
#Sta/Elev= 30
       0  540.04    5.99   538.7    8.99  537.88   11.99  536.68   14.99  535.11
   20.98  533.23   23.98   532.6   26.98  532.21   35.97  531.53   48.05  531.28
   57.17  529.98   64.89528.4243   68.91  527.52   71.71  527.28   74.52   527.6
   76.98528.4229   80.14  529.78   83.04  530.65   88.85   531.4   97.57  532.93
  100.48  533.04  106.31  532.87  112.13  531.09  115.04  530.89  117.95  531.36
  120.86  532.18  123.77  533.34  129.59  535.91   132.5  537.41  135.41  538.53
#Mann= 3 , 0 , 0
       0      .1       0   64.89      .1       0   76.98      .1       0
Bank Sta=64.89,76.98
XS Rating Curve= 0 ,0
Exp/Cntr=0.3,0.1

Type RM Length L Ch R = 1 ,5120.64 ,95.55,91.44,90.41
XS GIS Cut Line= 4
       615207.27    4338506.0594      615141.465     4338559.754
     615123.7182    4338567.2157     615101.2704    4338577.6697
#Sta/Elev= 25
       0  540.64    3.03  539.14    6.07   537.9     9.1   536.9   15.17  535.71
   21.23  534.67   24.27  534.04    27.3  532.58   30.33   531.3   33.37  530.82
    63.7  530.37   78.87  530.32   87.68  530.52   90.43  530.06   96.84 528.262
  101.43  526.83  104.18  526.18  106.93   526.1  109.69  526.75  111.65 528.261
  112.44  528.87  115.19  532.04  123.44  537.13  126.19  538.63  128.95  539.65
#Mann= 3 , 0 , 0
       0      .1       0   96.84      .1       0  111.65      .1       0
Bank Sta=96.84,111.65
XS Rating Curve= 0 ,0
Exp/Cntr=0.3,0.1

Type RM Length L Ch R = 1 ,5029.2  ,94.29,91.44,94.42
XS GIS Cut Line= 3
     615158.5866    4338405.5175     615085.5629    4338484.2097
     615050.4628     4338513.258
#Sta/Elev= 28
       0  540.76    3.07  539.59    6.13  538.25     9.2  537.48   12.27  536.86
   36.81  533.68   39.87  533.45   42.94  533.04   46.01  532.83   49.08   532.5
   55.21  531.78   64.41  530.55   67.48  530.27   76.68  529.87  107.35  529.15
  110.39  528.84  113.43  528.27  117.56527.2814  122.54  525.81  125.58  525.35
  128.62  526.24  130.02527.2796  131.65  528.49  137.73  533.76  140.77  534.55
   143.8  535.47  146.84  536.57  152.92  539.43
#Mann= 3 , 0 , 0
       0      .1       0  117.56      .1       0  130.02      .1       0
Bank Sta=117.56,130.02
XS Rating Curve= 0 ,0
Exp/Cntr=0.3,0.1

Type RM Length L Ch R = 1 ,4937.76 ,86.62,91.44,90.26
XS GIS Cut Line= 5
     615123.6615    4338357.8924     615028.8228    4338410.5577
     615015.0446    4338429.3462     615005.7744    4338435.3539
     614986.3034    4338458.0169
#Sta/Elev= 30
       0  541.59   12.05  537.77   15.07  537.14   18.08  536.79   27.12  536.51
   30.13  535.98   36.16  534.04   42.19  531.79    45.2  530.89   51.23   530.4
   54.24  529.86   57.25  528.73   63.28  527.53   81.36  526.99  102.45  526.66
  108.48  526.32  111.57525.8761  123.04  523.98  125.95  523.81  128.87  524.19
   134.8525.8778  140.06  527.08  142.83  527.35   148.8  526.61  151.79  526.61
  154.78  527.82  160.75  532.38  166.73  536.07  169.72  539.07   172.7  540.62
#Mann= 3 , 0 , 0
       0      .1       0  111.57      .1       0   134.8      .1       0
Bank Sta=111.57,134.8
XS Rating Curve= 0 ,0
Exp/Cntr=0.3,0.1

Type RM Length L Ch R = 1 ,4846.32 ,92.27,91.45,80.12
XS GIS Cut Line= 5
     615020.9953    4338294.5288     614978.8574    4338343.2589
      614962.855    4338354.3194     614941.3809    4338373.8702
     614914.3917    4338410.5153
#Sta/Elev= 30
       0  539.49    6.14  536.37   12.27  534.73   21.47  530.17   24.54  528.32
   27.61  526.62   30.68  525.69   33.74  525.45   58.29  525.42   61.35  525.22
   62.19525.0339    67.2  523.85   69.98  523.49   72.76  523.58   75.54  524.06
   78.91525.0328    81.1   525.6   83.88  526.12   86.78  526.42   104.2  526.86
  112.92     527  128.09  527.91  131.12  528.01  134.15  527.75  137.19  527.79
  140.22  528.87  146.29  532.75  149.32  533.65  152.36  534.89  158.43  538.91
#Mann= 3 , 0 , 0
       0      .1       0   62.19      .1       0   78.91      .1       0
Bank Sta=62.19,78.91
XS Rating Curve= 0 ,0
Exp/Cntr=0.3,0.1

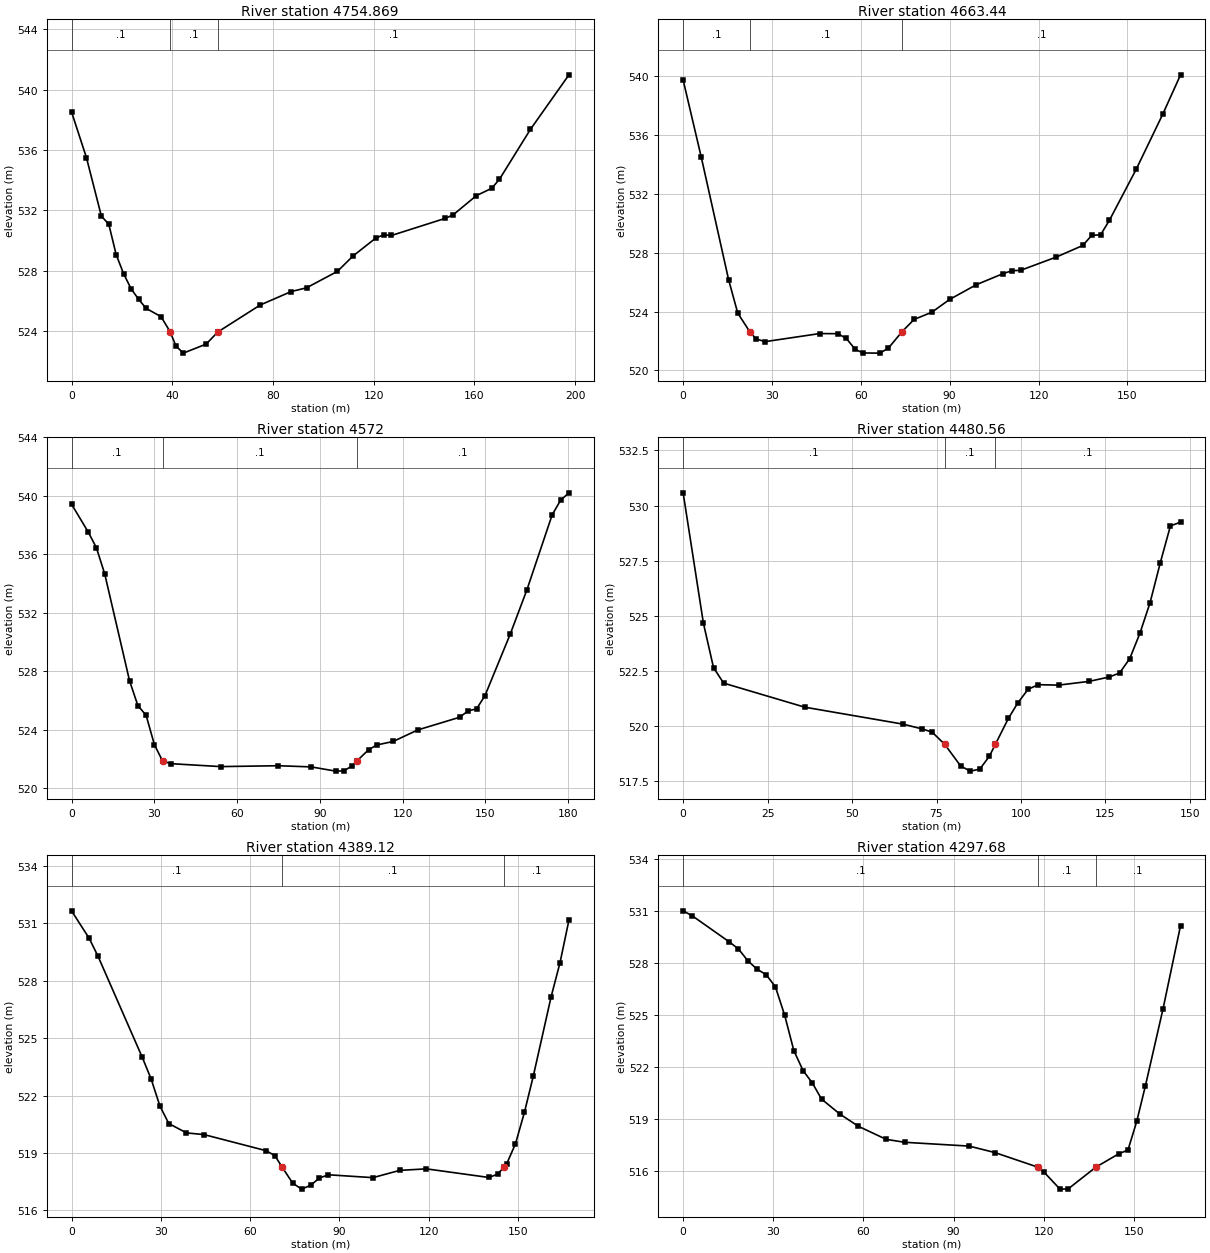
Type RM Length L Ch R = 1 ,4754.869,96.62,91.43,70.48
XS GIS Cut Line= 3
     614940.3064    4338241.5214     614912.3613    4338279.7506
     614838.9693    4338410.8092
#Sta/Elev= 30
       0  538.52    5.92  535.49   11.84  531.62    14.8  531.07   17.76  529.04
   20.72  527.78   23.68  526.79   26.64   526.1    29.6   525.5   35.52  524.95
   39.21523.9356   41.43  523.01   44.39  522.53   53.48  523.13   58.11523.9337
   74.94  525.72   87.21  526.61   93.34  526.86   105.6  527.95  111.73  528.96
  120.93  530.17  123.99  530.37  127.06  530.33  148.52  531.47  151.58   531.7
  160.78  532.97  166.91  533.46  169.97  534.06  182.24  537.36  197.56  540.98
#Mann= 3 , 0 , 0
       0      .1       0   39.21      .1       0   58.11      .1       0
Bank Sta=39.21,58.11
XS Rating Curve= 0 ,0
Exp/Cntr=0.3,0.1

Type RM Length L Ch R = 1 ,4663.44 ,95.55,91.44,85.47
XS GIS Cut Line= 4
     614824.5015    4338214.8234     614821.9693    4338267.0154
     614826.7978    4338289.2261     614821.2802    4338382.0338
#Sta/Elev= 30
       0  539.74    6.15  534.47   15.37  526.15   18.44  523.89   22.46522.6395
   24.59  522.14   27.66  521.95   46.11   522.5   52.25  522.49   55.09  522.17
   58.14  521.42   60.78  521.18   66.46  521.17    69.3  521.51   73.97522.6382
   77.98  523.46   83.98  523.95   89.98  524.82   98.98  525.82  107.97  526.57
  110.97  526.77  113.97   526.8  125.97   527.7  134.96  528.49  137.96  529.18
  140.96  529.21  143.96  530.21  152.96  533.66  161.96  537.42  167.95  540.09
#Mann= 3 , 0 , 0
       0      .1       0   22.46      .1       0   73.97      .1       0
Bank Sta=22.46,73.97
XS Rating Curve= 0 ,0
Exp/Cntr=0.3,0.1

Type RM Length L Ch R = 1 ,4572    ,61.38,91.44,102.43
XS GIS Cut Line= 4
      614738.429     4338194.635      614724.106    4338249.8684
     614743.9957     4338315.339     614731.1529    4338368.5989
#Sta/Elev= 30
       0  539.43    6.01  537.54    9.01  536.45   12.01  534.67   21.02  527.35
   24.03  525.65   27.03  524.98   30.03  522.97      33521.8513   36.04  521.67
   54.06  521.47   74.91  521.53   86.81  521.45   95.74  521.16   98.71  521.18
  101.69  521.52  103.39 521.852  107.64  522.62  110.61  522.95  116.56  523.19
  125.49  523.98   140.7  524.85  143.75  525.29  146.79  525.42  149.84  526.33
  158.97  530.53  165.05  533.58  174.18   538.7  177.23   539.7  180.27  540.21
#Mann= 3 , 0 , 0
       0      .1       0      33      .1       0  103.39      .1       0
Bank Sta=33,103.39
XS Rating Curve= 0 ,0
Exp/Cntr=0.3,0.1

Type RM Length L Ch R = 1 ,4480.56 ,91.23,91.44,91.97
XS GIS Cut Line= 5
     614708.5631    4338203.6644     614684.1893    4338244.9941
     614664.9274    4338262.0187     614648.6014    4338281.4842
     614621.7744    4338321.4558
#Sta/Elev= 28
       0  530.58       6  524.67       9  522.65      12  521.95   35.99  520.86
   65.12  520.09   70.83  519.87   73.69  519.73   77.44 519.172   82.16  518.19
   84.98  517.96    87.8  518.05   90.63  518.63   92.41519.1722   96.27  520.35
   99.09  521.06   102.1  521.67  105.11  521.88  111.13  521.86  120.16  522.03
  126.17  522.23  129.18  522.41  132.19  523.06   135.2  524.21  138.21   525.6
  141.22   527.4  144.23  529.08  147.23  529.25
#Mann= 3 , 0 , 0
       0      .1       0   77.44      .1       0   92.41      .1       0
Bank Sta=77.44,92.41
XS Rating Curve= 0 ,0
Exp/Cntr=0.3,0.1

Type RM Length L Ch R = 1 ,4389.12 ,106.16,91.44,69.17
XS GIS Cut Line= 3
      614657.112    4338135.9948     614614.6465    4338189.5404
     614544.7799     4338259.407
#Sta/Elev= 30
       0  531.66    5.94  530.22    8.91  529.28   23.77     524   26.74  522.87
   29.71  521.45   32.68  520.54   38.63  520.05   44.57  519.96   65.37  519.12
   68.34  518.86   70.79518.2537   74.33  517.42   77.32  517.11   80.32  517.31
   83.31  517.69   86.31  517.86  101.28  517.71  110.26  518.09  119.24  518.17
   140.2  517.72  143.19  517.89  145.25518.2539  146.19  518.42  149.18  519.48
  152.18  521.12  155.17  523.02  161.16  527.17  164.15  528.95  167.15  531.18
#Mann= 3 , 0 , 0
       0      .1       0   70.79      .1       0  145.25      .1       0
Bank Sta=70.79,145.25
XS Rating Curve= 0 ,0
Exp/Cntr=0.3,0.1

Type RM Length L Ch R = 1 ,4297.68 ,69.98,91.44,103.38
XS GIS Cut Line= 6
      614576.943    4338086.7822     614521.9442    4338168.1876
     614520.2878    4338184.3934     614520.2878    4338197.9533
     614521.9302    4338211.8432     614512.0218    4338232.9594
#Sta/Elev= 30
       0     531    3.07  530.71   15.35  529.21   18.42   528.8   21.49  528.13
   24.56  527.64   27.63  527.32    30.7  526.62   33.77  524.99   36.84  522.94
   39.91  521.79   42.98  521.08   46.05  520.15   52.19  519.28   58.33  518.58
   67.54  517.83   73.68  517.66   95.17  517.44  103.67  517.07     118516.2277
  119.96  515.96  125.38  514.96  128.09  514.97  137.32516.2278  145.08  517.01
  147.99  517.21  150.91  518.86  153.82  520.93  159.66  525.35  165.49  530.15
#Mann= 3 , 0 , 0
       0      .1       0     118      .1       0  137.32      .1       0
Bank Sta=118,137.32
XS Rating Curve= 0 ,0
Exp/Cntr=0.3,0.1

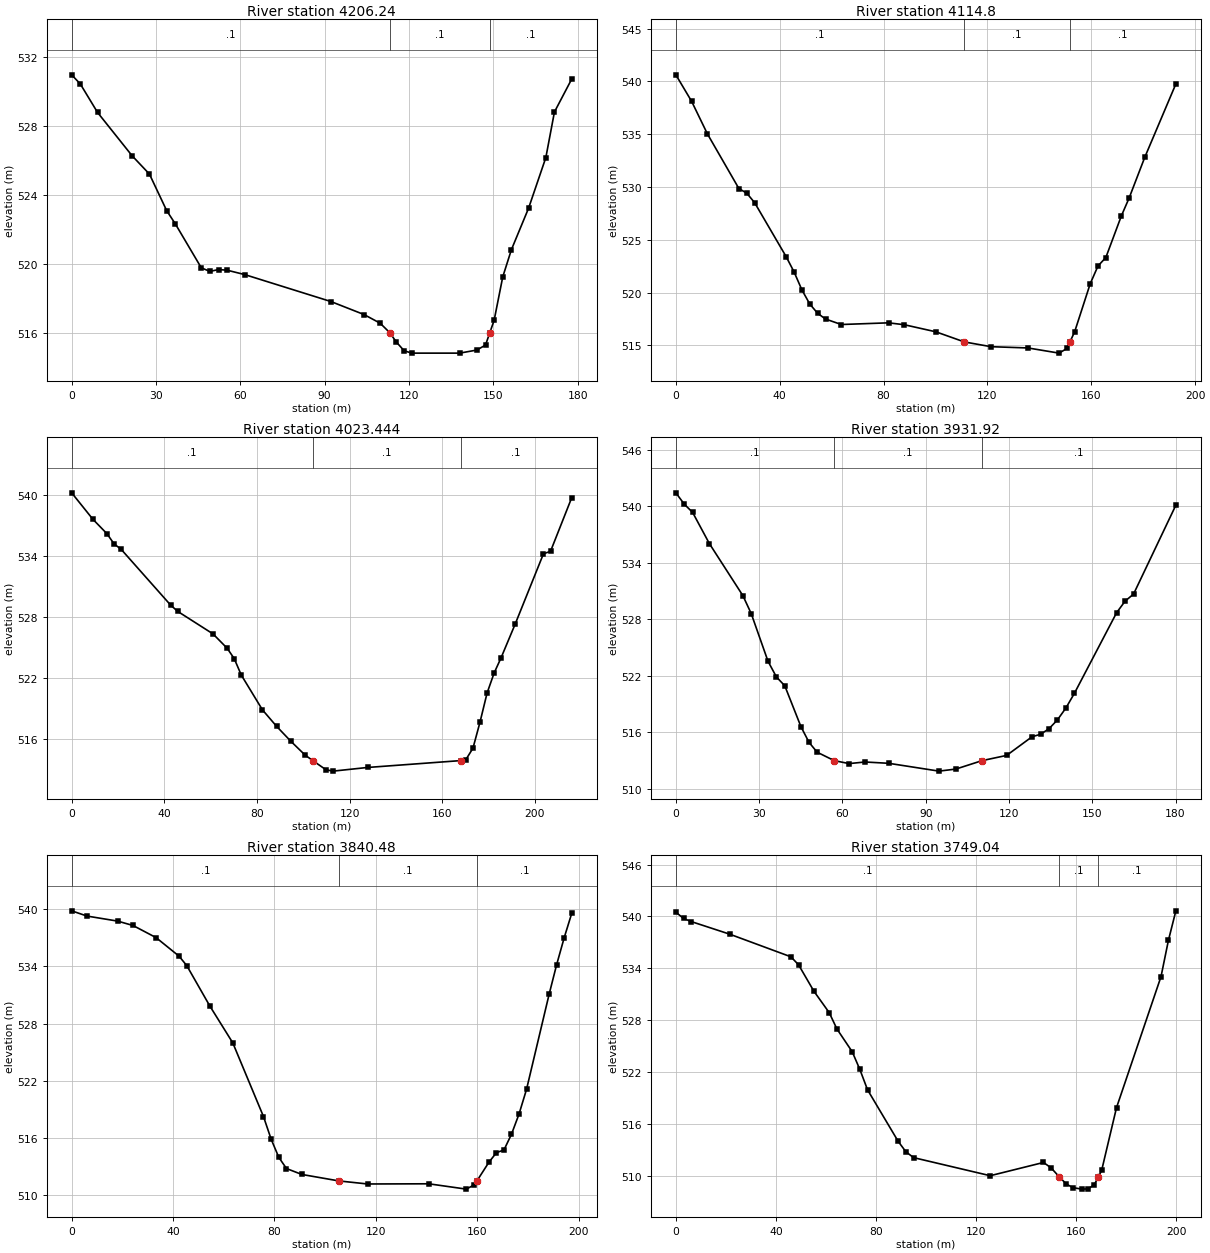
Type RM Length L Ch R = 1 ,4206.24 ,95.53,91.44,86.27
XS GIS Cut Line= 5
      614573.768    4338076.4634     614489.4225    4338127.0669
      614470.619     4338133.554     614457.3508    4338136.6965
     614413.4302    4338150.2823
#Sta/Elev= 30
       0  530.99    3.07  530.46    9.22   528.8   21.52  526.28   27.66  525.22
   33.81  523.09   36.89  522.32   46.11  519.77   49.18  519.56   52.25  519.67
   55.33  519.63   61.48  519.38   92.21  517.81  104.04  517.05  109.73  516.55
  113.19515.9937  115.41  515.47  118.25  514.95  120.98  514.81  138.02  514.81
  144.15  514.99  147.21  515.28  148.73 515.993  150.28  516.72  153.34  519.24
  156.41  520.82  162.54  523.24  168.67  526.18  171.73  528.83  177.86  530.74
#Mann= 3 , 0 , 0
       0      .1       0  113.19      .1       0  148.73      .1       0
Bank Sta=113.19,148.73
XS Rating Curve= 0 ,0
Exp/Cntr=0.3,0.1

Type RM Length L Ch R = 1 ,4114.8  ,90.51,91.36,91.69
XS GIS Cut Line= 4
     614506.3521    4337958.3002     614428.5763    4338051.4575
     614421.8193    4338056.2056     614376.9706    4338100.3818
#Sta/Elev= 30
       0  540.63    6.07  538.12   12.14  535.04   24.27  529.86   27.31  529.42
   30.34  528.52   42.47  523.41   45.51  521.97   48.54  520.26   51.58  518.92
   54.61  518.04   57.64   517.5   63.71  516.98   81.92  517.14   87.98  516.96
  100.12  516.29   111.1515.3311  121.36  514.88  135.61  514.76   147.6  514.27
   150.6  514.71  151.77515.3301   153.6   516.3  159.59  520.85  162.59  522.53
  165.59  523.32  171.58  527.27  174.58  528.97  180.58  532.81  192.57  539.77
#Mann= 3 , 0 , 0
       0      .1       0   111.1      .1       0  151.77      .1       0
Bank Sta=111.1,151.77
XS Rating Curve= 0 ,0
Exp/Cntr=0.3,0.1

Type RM Length L Ch R = 1 ,4023.444,98.18,91.52,84.36
XS GIS Cut Line= 4
      614455.552    4337915.4376     614361.7402    4337988.6239
     614354.1677    4337997.4787     614311.0892     4338071.013
#Sta/Elev= 30
       0  540.26    9.15  537.66   15.25  536.23   18.31  535.23   21.36   534.7
   42.71  529.21   45.76  528.59   61.02  526.37   67.12  524.96   70.17  523.94
   73.22  522.32   82.37  518.89   88.47  517.27   94.58  515.81  100.68  514.46
  104.07513.8976  109.83  512.99  112.86  512.86  127.72  513.22  167.96513.8968
   170.2     514  173.25  515.12  176.29  517.69  179.33  520.54  182.38  522.52
  185.42  524.04  191.51  527.36  203.68  534.26  206.73   534.5  215.86  539.77
#Mann= 3 , 0 , 0
       0      .1       0  104.07      .1       0  167.96      .1       0
Bank Sta=104.07,167.96
XS Rating Curve= 0 ,0
Exp/Cntr=0.3,0.1

Type RM Length L Ch R = 1 ,3931.92 ,89.35,91.44,90.78
XS GIS Cut Line= 5
     614309.9449    4337880.2644     614294.8294    4337916.4766
     614292.2848    4337933.7679     614290.8831     4337956.546
     614267.4328    4338054.3442
#Sta/Elev= 30
       0  541.44    3.02  540.24    6.04  539.36   12.07  536.05   24.15  530.52
   27.17   528.6    33.2  523.55   36.22  521.89   39.24  520.95   45.07   516.6
   47.98  514.94   50.89   513.9   57.05513.0046   62.42  512.69   68.13  512.86
   76.69  512.72   94.78  511.89  100.87  512.11   110.3513.0043  119.16  513.56
   128.3  515.54  131.35   515.8   134.4  516.39  137.44  517.33  140.49  518.59
  143.54  520.14  158.78  528.72  161.82  529.94  164.87  530.69  180.11  540.13
#Mann= 3 , 0 , 0
       0      .1       0   57.05      .1       0   110.3      .1       0
Bank Sta=57.05,110.3
XS Rating Curve= 0 ,0
Exp/Cntr=0.3,0.1

Type RM Length L Ch R = 1 ,3840.48 ,72.98,91.44,95.67
XS GIS Cut Line= 6
     614272.1954    4337845.5875     614206.5054    4337928.6899
     614204.7421     4337950.291     614203.3351     4337953.701
     614202.5728    4337963.2159     614177.7389    4338013.8628
#Sta/Elev= 30
       0  539.84    6.05  539.29   18.16  538.76   24.21   538.3   33.29  537.03
   42.37  535.08    45.4  534.09   54.48  529.86   63.56  525.98   75.66  518.25
   78.69  515.87   81.72  513.96   84.74  512.79    90.8  512.17  105.42511.4903
  116.77  511.17  140.84  511.19  155.68  510.63  158.65  511.06  159.86511.4919
  164.59  513.45  167.56  514.46  170.53  514.74  173.49  516.39  176.46   518.5
  179.43   521.1  188.34  531.08  191.31  534.19  194.28  537.01  197.24  539.56
#Mann= 3 , 0 , 0
       0      .1       0  105.42      .1       0  159.86      .1       0
Bank Sta=105.42,159.86
XS Rating Curve= 0 ,0
Exp/Cntr=0.3,0.1

Type RM Length L Ch R = 1 ,3749.04 ,86.04,91.44,94.07
XS GIS Cut Line= 6
     614272.9891    4337832.0937     614155.9547    4337899.1042
     614141.2637    4337909.7718      614132.744    4337913.3013
     614128.0154    4337914.9781     614097.9767    4337927.7049
#Sta/Elev= 30
       0  540.49    3.07  539.77    6.13  539.41   21.46  537.96   45.98  535.34
   49.04  534.42   55.17  531.37    61.3  528.89   64.37  527.01    70.5  524.37
   73.56  522.32   76.63  519.97   88.89  514.01   91.95  512.82   95.02  512.14
  125.67  510.05  146.96  511.58  149.99  510.96  153.31 509.905  156.09  509.09
  158.63  508.68  162.24   508.5  164.75  508.53  167.26     509  168.86509.9027
  170.22  510.67  176.15  517.91  193.95  533.06  196.91  537.25  199.88  540.65
#Mann= 3 , 0 , 0
       0      .1       0  153.31      .1       0  168.86      .1       0
Bank Sta=153.31,168.86
XS Rating Curve= 0 ,0
Exp/Cntr=0.3,0.1

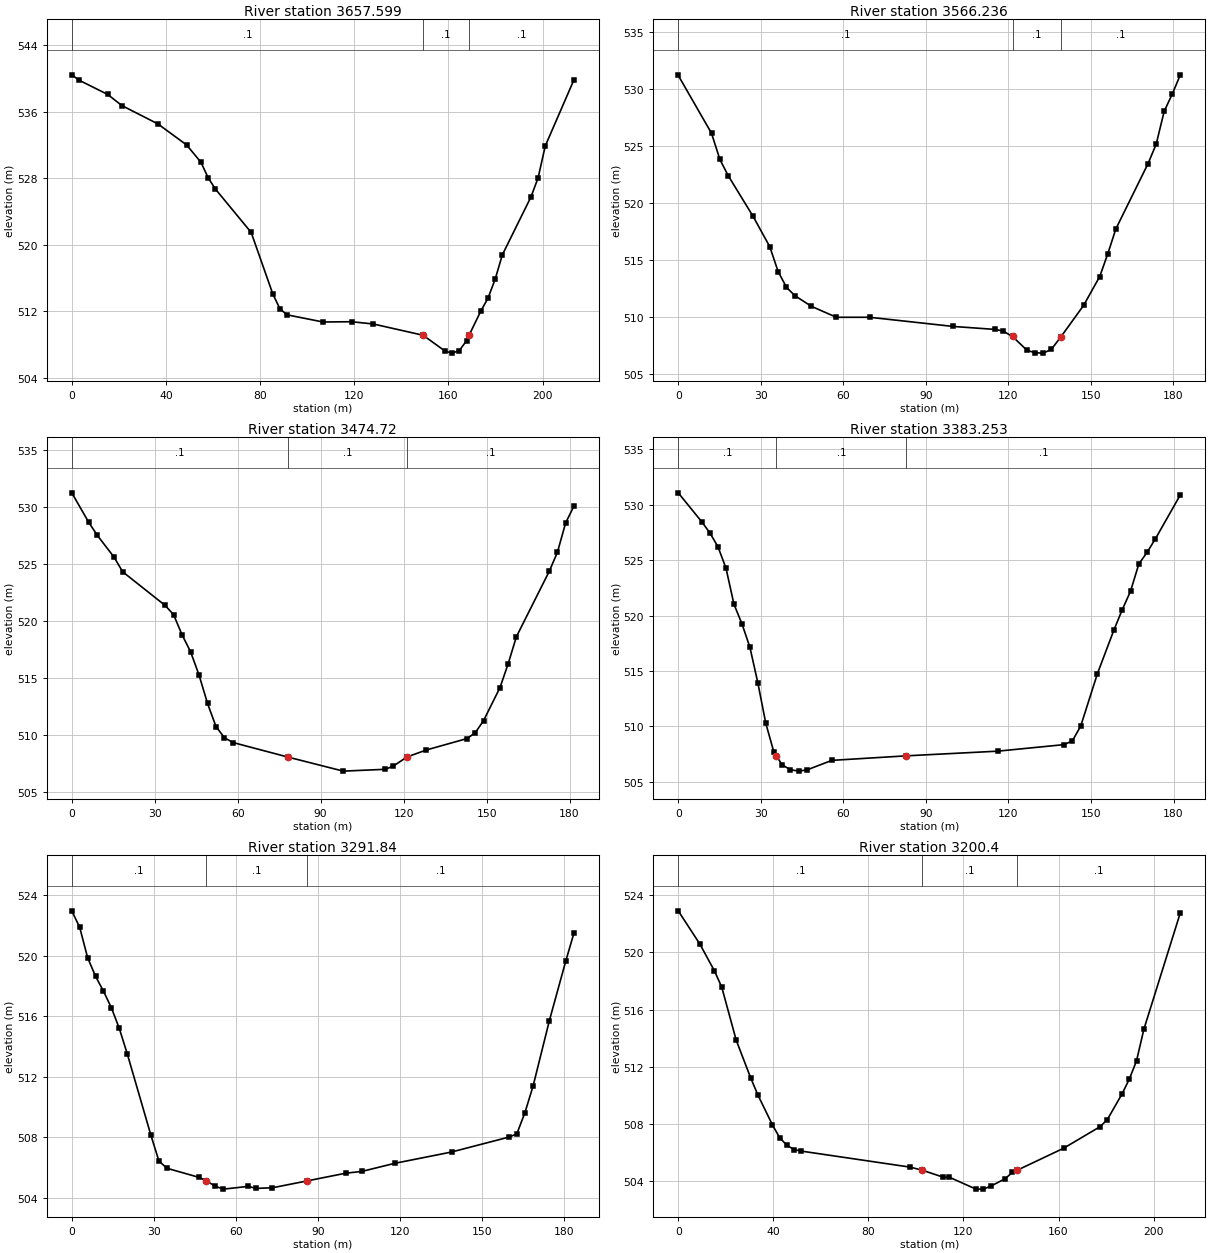
Type RM Length L Ch R = 1 ,3657.599,90.5,91.36,94.59
XS GIS Cut Line= 3
     614272.1954    4337824.1562     614098.4458    4337827.9838
      614059.643    4337835.3826
#Sta/Elev= 30
       0  540.46    3.05  539.82   15.24   538.1   21.34  536.75   36.59  534.55
   48.78  532.02   54.88  529.93   57.93  528.07   60.98  526.72   76.22  521.48
   85.37   514.1   88.42  512.29   91.47  511.56  106.71   510.7  118.91  510.73
  128.06  510.46  149.26509.1024  158.55   507.2   161.6  506.95  164.64  507.26
  167.69  508.44  168.78509.1002  173.79  512.03  176.83  513.57  179.87  515.86
  182.91  518.78  195.06  525.75   198.1  528.05  201.14  531.89  213.29  539.83
#Mann= 3 , 0 , 0
       0      .1       0  149.26      .1       0  168.78      .1       0
Bank Sta=149.26,168.78
XS Rating Curve= 0 ,0
Exp/Cntr=0.3,0.1

Type RM Length L Ch R = 1 ,3566.236,93,91.52,89.66
XS GIS Cut Line= 4
     614238.2625    4337747.3938     614123.4992    4337740.7792
     614109.2531    4337736.7802     614056.6963    4337732.4563
#Sta/Elev= 30
       0  531.18    12.1  526.11   15.13  523.82   18.15   522.4   27.23  518.82
   33.28  516.17    36.3     514   39.33  512.62   42.35  511.89    48.4  510.95
   57.48  509.99   69.58  509.99   99.83  509.19  114.95  508.93  117.91   508.8
   121.5508.3068  126.79  507.09  129.75  506.88  132.68  506.85  135.61  507.18
  139.17508.3058  147.33  511.03  153.19  513.56  156.12  515.55  159.05  517.73
  170.77  523.46   173.7  525.15  176.63  528.04  179.56  529.55  182.48  531.23
#Mann= 3 , 0 , 0
       0      .1       0   121.5      .1       0  139.17      .1       0
Bank Sta=121.5,139.17
XS Rating Curve= 0 ,0
Exp/Cntr=0.3,0.1

Type RM Length L Ch R = 1 ,3474.72 ,92.02,91.47,86.56
XS GIS Cut Line= 4
     614209.8197    4337649.4978     614099.4425    4337645.6098
     614093.8448    4337647.1259     614028.5798    4337649.4978
#Sta/Elev= 30
       0  531.22    6.14  528.63     9.2   527.5   15.34  525.56   18.41  524.29
   33.75  521.34   36.82  520.53   39.88  518.76   42.95  517.28   46.02  515.23
   49.09  512.74   52.15  510.71   55.22  509.73   58.29  509.31   78.16508.0336
   98.17   506.8  113.35  506.96  116.25  507.24  121.17508.0344  128.12  508.65
  142.96  509.66  145.93  510.18   148.9  511.23  154.84  514.13   157.8  516.22
  160.77  518.59  172.65  524.33  175.62  526.01  178.58  528.58  181.55  530.04
#Mann= 3 , 0 , 0
       0      .1       0   78.16      .1       0  121.17      .1       0
Bank Sta=78.16,121.17
XS Rating Curve= 0 ,0
Exp/Cntr=0.3,0.1

Type RM Length L Ch R = 1 ,3383.253,103.99,91.41,82.06
XS GIS Cut Line= 3
     614180.2001    4337557.6354     614146.9968    4337567.7718
     614001.8744    4337595.4874
#Sta/Elev= 30
       0  531.06    8.68  528.41   11.57  527.42   14.47  526.18   17.36  524.26
   20.25  521.02   23.14  519.26   26.04  517.14   28.93  513.93   31.82  510.28
   34.72  507.72   35.66 507.351   37.73  506.54   40.75   506.1   43.76  505.97
   46.78  506.08   55.82  506.94   82.92507.3492  116.13  507.77  140.25  508.36
  143.26  508.71  146.28  510.04  152.31  514.74  158.34   518.7  161.35  520.52
  164.37  522.19  167.39  524.65   170.4   525.7  173.42  526.92  182.46  530.87
#Mann= 3 , 0 , 0
       0      .1       0   35.66      .1       0   82.92      .1       0
Bank Sta=35.66,82.92
XS Rating Curve= 0 ,0
Exp/Cntr=0.3,0.1

Type RM Length L Ch R = 1 ,3291.84 ,84.87,91.44,95.03
XS GIS Cut Line= 5
     614138.8243    4337450.4601     614102.9741    4337475.0283
     614094.0512    4337497.3354     614084.4002    4337515.7001
     614006.5227    4337570.8022
#Sta/Elev= 30
       0  522.96     2.9  521.87    5.79  519.87    8.69  518.64   11.59  517.66
   14.49  516.56   17.38   515.2   20.28  513.53   28.97  508.13   31.87  506.45
   34.77  505.97   46.46  505.37   49.26505.1375   52.47  504.78   55.47  504.59
   64.48  504.77   67.49  504.64   73.41  504.68   86.19505.1373  100.16  505.64
  106.12  505.76  118.04  506.29  138.91  507.04  159.78  508.02  162.76  508.23
  165.74  509.64  168.73   511.4  174.69  515.72  180.65  519.63  183.63  521.47
#Mann= 3 , 0 , 0
       0      .1       0   49.26      .1       0   86.19      .1       0
Bank Sta=49.26,86.19
XS Rating Curve= 0 ,0
Exp/Cntr=0.3,0.1

Type RM Length L Ch R = 1 ,3200.4  ,83.35,91.44,97.47
XS GIS Cut Line= 4
     614117.9209    4337366.7282     614038.4949    4337428.5197
     614024.8538    4337445.2202     613956.2794    4337502.0087
#Sta/Elev= 30
       0  522.91    9.15  520.57   15.25   518.7    18.3  517.57    24.4  513.85
   30.49  511.21   33.54  510.01   39.64  507.92   42.69  507.03   45.74  506.49
   48.79   506.2   51.84  506.09   97.58  504.97  102.72504.7516  111.41  504.27
  114.11  504.26  125.27  503.43  128.34  503.43  131.41  503.63  137.55  504.16
  140.62  504.61   142.6504.7519  162.11  506.29  177.46   507.8  180.53   508.3
  186.67  510.08  189.74  511.12  192.81  512.41  195.88  514.61  211.23  522.77
#Mann= 3 , 0 , 0
       0      .1       0  102.72      .1       0   142.6      .1       0
Bank Sta=102.72,142.6
XS Rating Curve= 0 ,0
Exp/Cntr=0.3,0.1

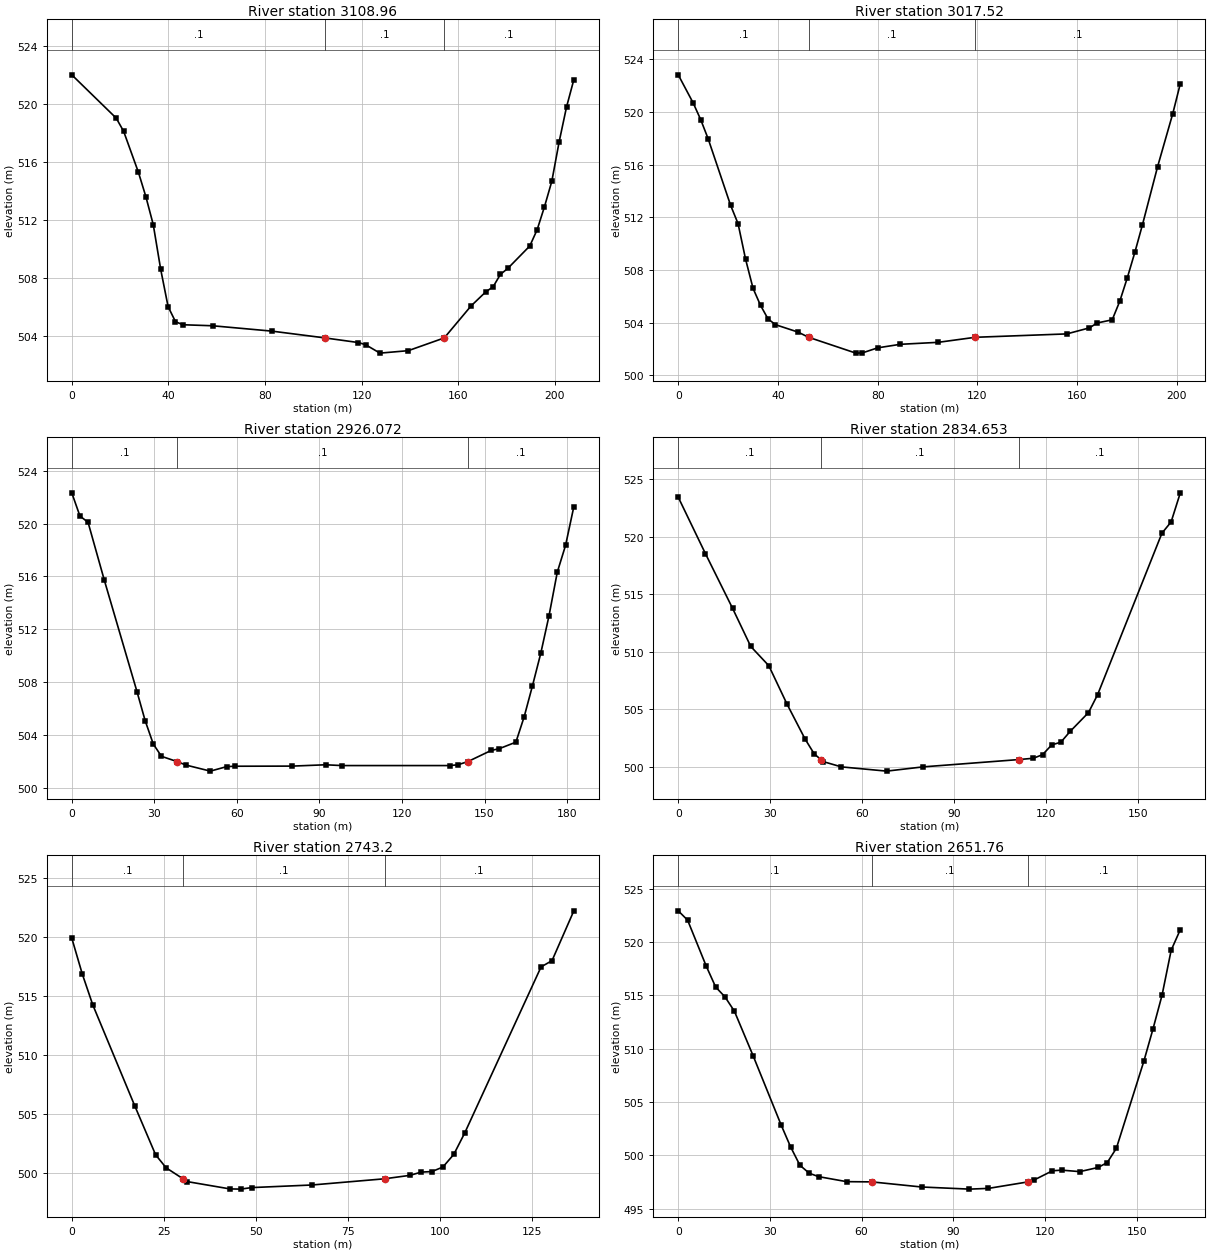
Type RM Length L Ch R = 1 ,3108.96 ,96.79,91.44,85.21
XS GIS Cut Line= 5
     614076.0759    4337319.0506     613999.7454    4337370.4528
     613956.5239     4337380.858      613933.852    4337382.7467
     613892.7101    4337408.6718
#Sta/Elev= 30
       0  522.02    18.4  519.03   21.47  518.12   27.61  515.28   30.67  513.61
   33.74  511.67   36.81  508.59   39.88  506.01   42.94  504.97   46.01  504.76
   58.28  504.69   82.82  504.32  104.81503.8511   118.7  503.53  121.66  503.38
  127.59   502.8  139.32  502.97  154.21503.8505  165.31  506.06  171.39  507.03
  174.43  507.38  177.47  508.24  180.51  508.65  189.62   510.2  192.66  511.32
   195.7  512.91  198.74  514.67  201.78   517.4  204.82  519.79  207.86  521.69
#Mann= 3 , 0 , 0
       0      .1       0  104.81      .1       0  154.21      .1       0
Bank Sta=104.81,154.21
XS Rating Curve= 0 ,0
Exp/Cntr=0.3,0.1

Type RM Length L Ch R = 1 ,3017.52 ,93.52,91.45,85.27
XS GIS Cut Line= 4
      614015.527    4337250.5097      613958.745    4337284.1672
     613953.1005    4337289.6485     613843.4706    4337354.6829
#Sta/Elev= 30
       0  522.82       6  520.68       9  519.42      12  517.96      21  512.91
      24  511.51      27  508.82      30   506.6      33  505.31      36  504.28
      39  503.84   48.01  503.28   52.29502.8833   71.25  501.68   73.88   501.7
   79.95  502.08   89.05  502.35  104.23   502.5   119.1502.8831  155.82  503.14
  164.92   503.6  167.96  503.97  174.03  504.21  177.06  505.62   180.1  507.41
  183.13  509.35  186.17  511.44  192.24  515.85  198.31  519.87  201.34  522.15
#Mann= 3 , 0 , 0
       0      .1       0   52.29      .1       0   119.1      .1       0
Bank Sta=52.29,119.1
XS Rating Curve= 0 ,0
Exp/Cntr=0.3,0.1

Type RM Length L Ch R = 1 ,2926.072,93.27,91.42,88.52
XS GIS Cut Line= 4
     613919.6153    4337179.0721        613886.7     4337231.863
     613878.3115    4337254.3353      613823.289    4337333.3205
#Sta/Elev= 29
       0  522.32    2.96  520.57    5.92  520.09   11.85   515.7    23.7  507.29
   26.66   505.1   29.62  503.33   32.59   502.4   38.21502.0062   41.47  501.74
   50.36  501.28   56.29  501.62   59.25  501.65    80.2  501.66   92.21  501.76
   98.23   501.7  137.34   501.7  140.35  501.76     144502.0061  152.38  502.84
  155.39  502.98   161.4  503.47  164.41  505.39  167.42  507.73  170.43  510.18
  173.43  513.02  176.44  516.32  179.45  518.35  182.46  521.28
#Mann= 3 , 0 , 0
       0      .1       0   38.21      .1       0     144      .1       0
Bank Sta=38.21,144
XS Rating Curve= 0 ,0
Exp/Cntr=0.3,0.1

Type RM Length L Ch R = 1 ,2834.653,91.68,91.45,91.35
XS GIS Cut Line= 3
     613820.3964    4337141.3689     613800.5291    4337212.6089
     613768.8025    4337296.8119
#Sta/Elev= 24
       0  523.45    8.88  518.54   17.75  513.78   23.67  510.47   29.58  508.79
    35.5  505.46   41.42  502.41   44.38  501.13   46.57500.6252   47.33  500.45
   53.25  499.99   68.04  499.62   79.96  499.99  111.19500.6248  115.95  500.74
  118.95  501.05  121.95   501.9  124.95  502.14  127.95  503.07  133.95  504.71
  136.95  506.28  157.94  520.32  160.94   521.3  163.94  523.83
#Mann= 3 , 0 , 0
       0      .1       0   46.57      .1       0  111.19      .1       0
Bank Sta=46.57,111.19
XS Rating Curve= 0 ,0
Exp/Cntr=0.3,0.1

Type RM Length L Ch R = 1 ,2743.2  ,89.85,91.44,92.22
XS GIS Cut Line= 5
     613748.9829    4337124.8392     613727.0287    4337154.5809
     613721.5399    4337168.3028     613719.2326    4337172.1932
     613693.3961    4337247.8639
#Sta/Elev= 22
       0  519.91    2.84  516.88    5.69  514.26   17.06  505.72   22.75  501.55
   25.59  500.45   30.18499.5163   31.28  499.28   42.88  498.66   45.83  498.64
   48.79  498.77   65.15  498.99   84.87499.5159   91.81  499.81   94.77  500.08
   97.73  500.13  100.69  500.51  103.65  501.58  106.61  503.39  127.34  517.47
  130.31     518  136.23  522.22
#Mann= 3 , 0 , 0
       0      .1       0   30.18      .1       0   84.87      .1       0
Bank Sta=30.18,84.87
XS Rating Curve= 0 ,0
Exp/Cntr=0.3,0.1

Type RM Length L Ch R = 1 ,2651.76 ,91.72,91.44,92.52
XS GIS Cut Line= 5
     613676.1982    4337051.9395     613641.2464    4337130.2406
     613635.8143    4337138.1078      613634.374    4337144.1626
     613598.5521     4337195.707
#Sta/Elev= 30
       0  522.91    3.06  522.04    9.19  517.71   12.25  515.77   15.31  514.84
   18.37  513.51    24.5  509.33   33.69  502.83   36.75   500.8   39.81  499.07
   42.87  498.32   45.94     498   55.12  497.53   63.33497.5088   79.62  497.03
   95.31  496.83  101.53   496.9  114.47497.5085  116.48  497.69  122.46  498.55
  125.44  498.61  131.42  498.47   137.4  498.86  140.39  499.32  143.38  500.66
  152.35   508.8  155.33  511.81  158.32     515  161.31  519.22   164.3  521.15
#Mann= 3 , 0 , 0
       0      .1       0   63.33      .1       0  114.47      .1       0
Bank Sta=63.33,114.47
XS Rating Curve= 0 ,0
Exp/Cntr=0.3,0.1