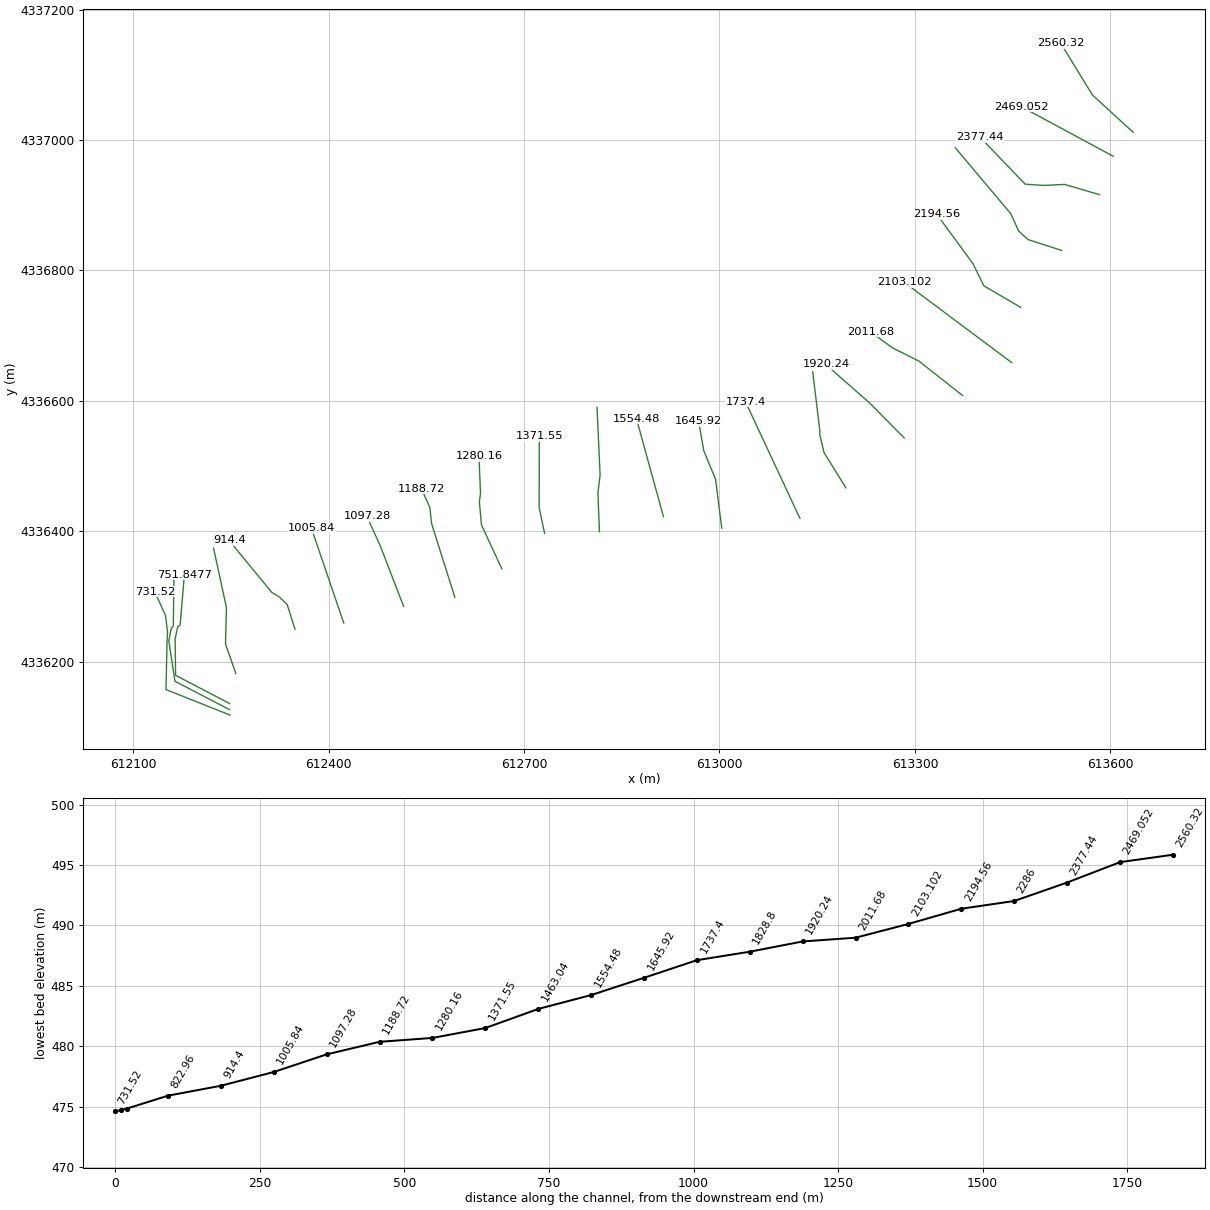
HEC-RAS study MinearRun.prj: MinearRun

--- MinearRun.g01 (geometry) --- (continued)

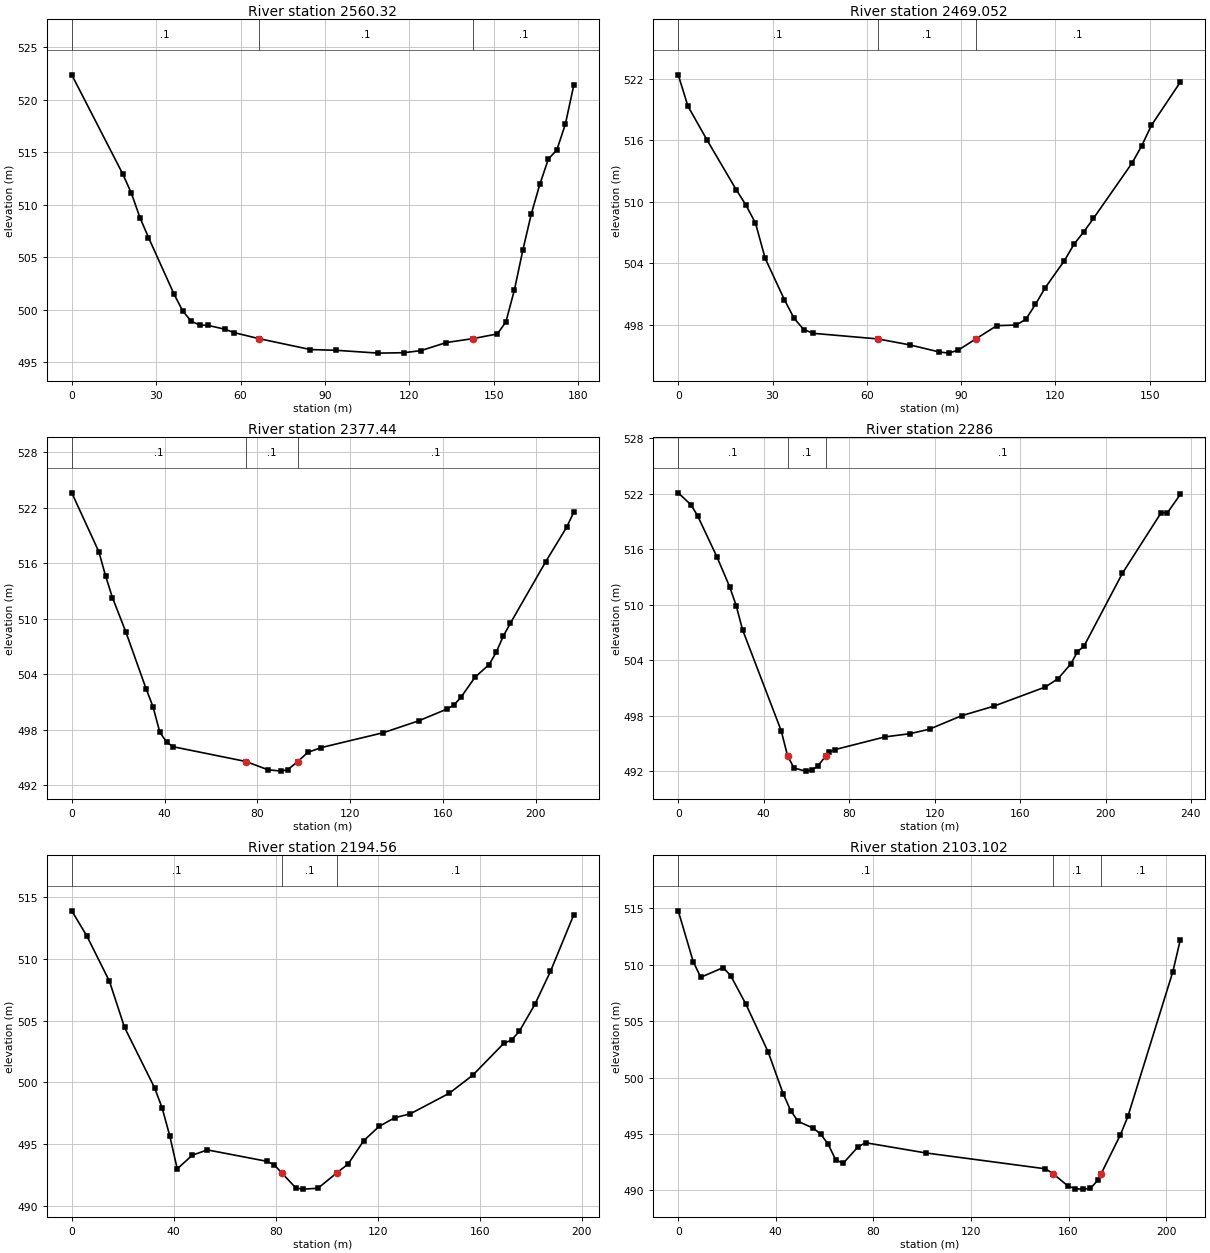
Type RM Length L Ch R = 1 ,2560.32 ,84.6,91.27,94.47
XS GIS Cut Line= 3
     613635.0554    4337011.8551     613572.4365    4337069.1013
     613523.4397    4337148.8634
#Sta/Elev= 30
       0  522.35   18.18  512.88   21.21  511.06   24.24  508.75   27.27  506.86
   36.36  501.46   39.39  499.89   42.42  498.89   45.45  498.53   48.48  498.49
   54.54  498.12   57.57  497.81   66.38497.2385   84.84  496.19    93.9  496.12
     109  495.85  118.06  495.89   124.1  496.09  133.16  496.86  142.75497.2381
  151.27  497.68  154.29  498.82  157.31  501.85  160.33  505.67  163.35  509.13
  166.37  511.93  169.39  514.33  172.41   515.2  175.43  517.65  178.45  521.39
#Mann= 3 , 0 , 0
       0      .1       0   66.38      .1       0  142.75      .1       0
Bank Sta=66.38,142.75
XS Rating Curve= 0 ,0
Exp/Cntr=0.3,0.1

Type RM Length L Ch R = 1 ,2469.052,83.95,91.61,95.22
XS GIS Cut Line= 2
     613604.4021    4336975.1159     613463.7373    4337050.8812
#Sta/Elev= 30
       0  522.39    3.07  519.34    9.22     516   18.44  511.19   21.51   509.7
   24.58  507.93   27.65   504.5    33.8  500.44   36.87  498.64   39.94  497.54
   43.02  497.17   63.49 496.627   73.74  496.04   82.96  495.36   86.03  495.24
    89.1  495.53    94.7496.6271  101.39  497.92  107.54  497.98  110.61  498.54
  113.68     500  116.76  501.61   122.9  504.27  125.97  505.88  129.05  507.07
  132.12  508.38  144.41  513.78  147.48  515.46  150.55  517.45  159.77  521.68
#Mann= 3 , 0 , 0
       0      .1       0   63.49      .1       0    94.7      .1       0
Bank Sta=63.49,94.7
XS Rating Curve= 0 ,0
Exp/Cntr=0.3,0.1

Type RM Length L Ch R = 1 ,2377.44 ,95.61,91.44,81.31
XS GIS Cut Line= 5
     613582.9499    4336916.3162      613529.741    4336931.9618
      613497.823    4336930.4048     613469.2847    4336932.2971
     613399.6816     4337004.676
#Sta/Elev= 30
       0  523.62   11.68  517.25    14.6  514.62   17.51  512.31   23.35  508.56
   32.11   502.4   35.03   500.5   37.95  497.76   40.87  496.68   43.79  496.18
   75.12494.5897   84.51   493.7   90.28  493.55   93.14  493.71   97.43  494.59
  101.72  495.57  107.44  496.09  134.28   497.7  149.49  498.98  161.66  500.25
   164.7  500.69  167.75  501.52  173.83   503.7  179.92  505.07  182.96  506.39
     186  508.13  189.05  509.52  204.26  516.16  213.39  519.93  216.43  521.55
#Mann= 3 , 0 , 0
       0      .1       0   75.12      .1       0   97.43      .1       0
Bank Sta=75.12,97.43
XS Rating Curve= 0 ,0
Exp/Cntr=0.3,0.1

Type RM Length L Ch R = 1 ,2286    ,98.93,91.44,89.89
XS GIS Cut Line= 5
     613525.1627    4336830.7656     613473.5592    4336847.4178
     613459.3291    4336860.2926     613447.3066    4336886.8592
     613361.9784    4336988.1396
#Sta/Elev= 30
       0   522.1    6.02  520.79    9.04  519.63   18.07   515.2    24.1  511.93
   27.11  509.92   30.12  507.29    48.2  496.38   51.19493.6582   54.22  492.35
   59.71  492.02   62.45  492.14   65.19  492.53   69.08493.6564   70.67  494.08
   73.41  494.35   96.74  495.72  108.59  496.07  117.62  496.56  132.67  498.01
  147.72  499.04   171.8  501.11  177.82  502.02  183.84  503.63  186.85  504.93
  189.86   505.5  207.92  513.41  225.98  519.93  228.99  519.95  235.01  521.93
#Mann= 3 , 0 , 0
       0      .1       0   51.19      .1       0   69.08      .1       0
Bank Sta=51.19,69.08
XS Rating Curve= 0 ,0
Exp/Cntr=0.3,0.1

Type RM Length L Ch R = 1 ,2194.56 ,92.19,91.46,92.39
XS GIS Cut Line= 4
     613461.9799    4336743.6753     613405.8634     4336776.464
     613389.4451     4336809.932     613333.5356    4336886.2748
#Sta/Elev= 30
       0  513.87    5.91  511.84   14.77  508.18   20.68  504.46    32.5  499.56
   35.45  497.93   38.41   495.7   41.36  493.02   47.27  494.12   53.18  494.55
   76.46  493.63   79.33  493.36   82.31492.7001   87.93  491.46    90.8  491.38
   96.54  491.45  103.99492.6994  108.38  493.41  114.48  495.29  120.59  496.46
  126.69  497.15   132.8  497.47  148.06  499.13  157.22  500.58  169.43  503.16
  172.48  503.43  175.53  504.14  181.64  506.32  187.74  508.98   196.9  513.57
#Mann= 3 , 0 , 0
       0      .1       0   82.31      .1       0  103.99      .1       0
Bank Sta=82.31,103.99
XS Rating Curve= 0 ,0
Exp/Cntr=0.3,0.1

Type RM Length L Ch R = 1 ,2103.102,88.05,91.42,91.62
XS GIS Cut Line= 2
     613448.6296    4336658.7326      613283.657    4336781.8388
#Sta/Elev= 30
       0  514.78    6.14  510.28    9.22  508.89   18.43  509.75   21.51  509.03
   27.65  506.55   36.87  502.27   43.01  498.58   46.08  497.08   49.16  496.12
    55.3  495.53   58.37     495   61.45  494.11   64.52  492.73   67.59   492.4
   73.73  493.87   76.81  494.23  101.39  493.33  150.54  491.92  153.64491.4942
  159.76   490.4  162.83  490.15   165.9  490.12  168.98  490.18  172.05  490.92
  173.41491.4959  181.26  494.92  184.34  496.56  202.77  509.38  205.84  512.21
#Mann= 3 , 0 , 0
       0      .1       0  153.64      .1       0  173.41      .1       0
Bank Sta=153.64,173.41
XS Rating Curve= 0 ,0
Exp/Cntr=0.3,0.1

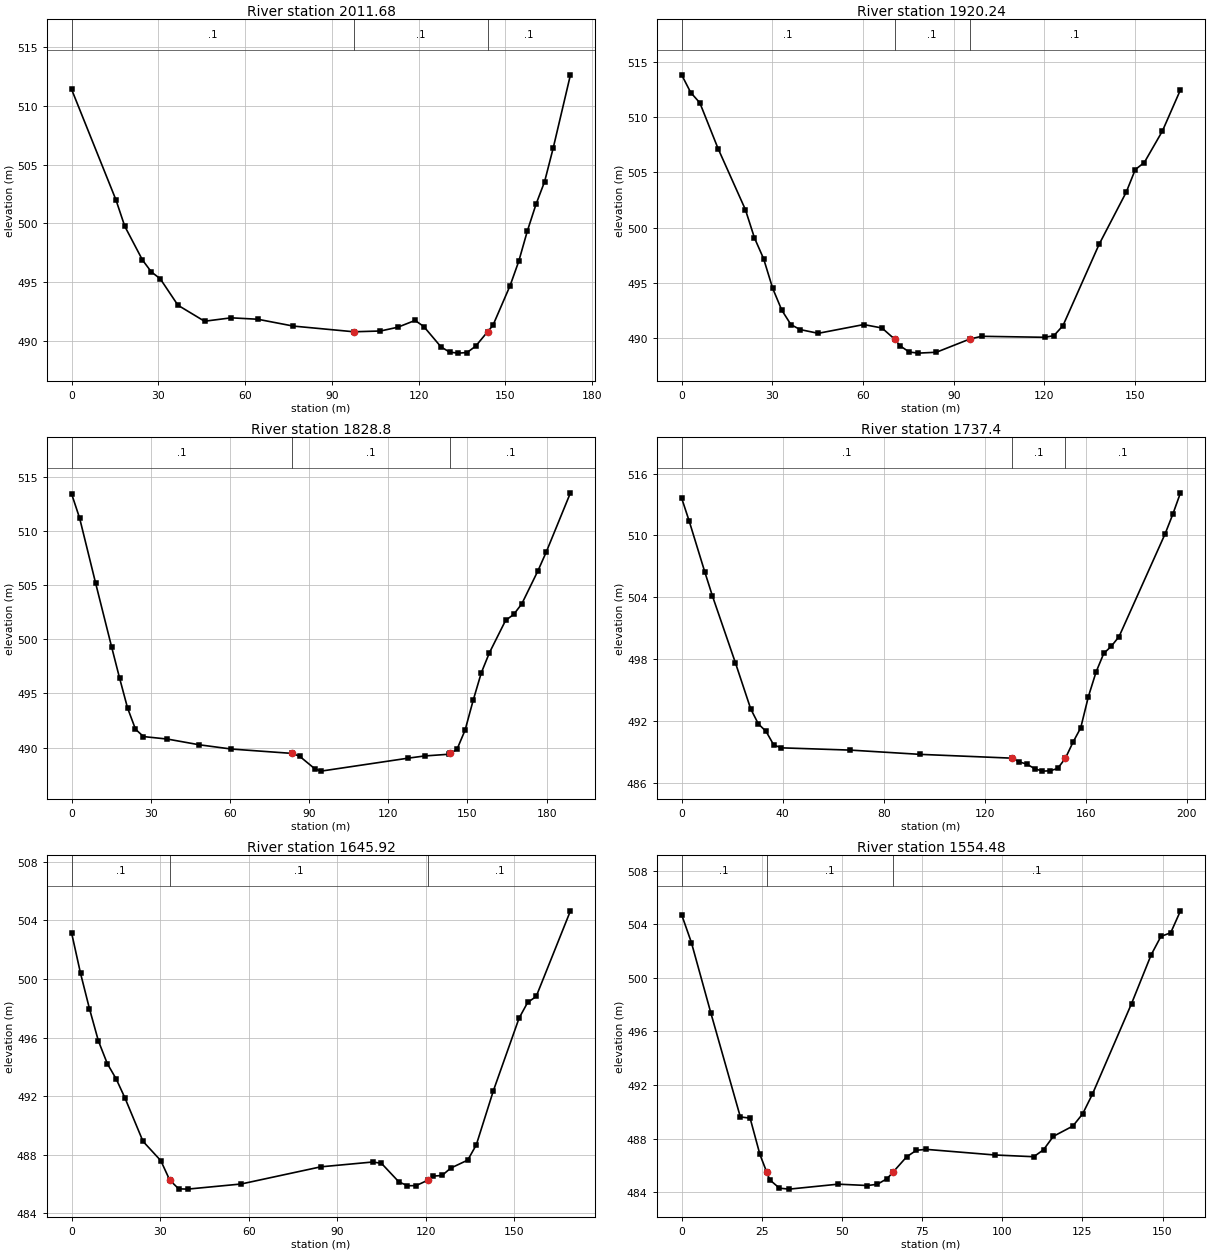
Type RM Length L Ch R = 1 ,2011.68 ,93.8,91.44,87.18
XS GIS Cut Line= 4
     613373.3202    4336608.2148      613305.879    4336661.2495
     613265.6275    4336681.2831     613231.9904    4336705.9588
#Sta/Elev= 30
       0  511.39   15.32  502.01   18.38  499.76   24.51  496.89   27.58  495.88
   30.64   495.3   36.77  493.05   45.96  491.69   55.15  491.98   64.35  491.86
    76.6  491.28   97.58490.7949  106.78  490.86  112.77  491.18  118.77  491.76
  121.77  491.24  127.76   489.5  130.76  489.06  133.74  488.98  136.72  489.03
   139.7  489.57  143.83490.7957  145.66  491.33  151.62  494.72   154.6  496.78
  157.58  499.36  160.56  501.62  163.54  503.55  166.52  506.41  172.48  512.63
#Mann= 3 , 0 , 0
       0      .1       0   97.58      .1       0  143.83      .1       0
Bank Sta=97.58,143.83
XS Rating Curve= 0 ,0
Exp/Cntr=0.3,0.1

Type RM Length L Ch R = 1 ,1920.24 ,95.65,91.44,74.23
XS GIS Cut Line= 3
     613283.6263    4336543.1271      613230.678    4336596.6696
     613163.2871    4336655.8643
#Sta/Elev= 30
       0  513.81    3.01  512.21    6.02  511.28   12.05  507.15   21.08  501.64
    24.1  499.07   27.11   497.2   30.12  494.52   33.13  492.55   36.14  491.25
   39.16   490.8   45.18  490.46   60.24  491.25   66.27  490.94   70.45489.9313
   72.29  489.32    75.3  488.77   78.29  488.67   84.27  488.75   95.22489.9323
   99.22  490.19  120.15   490.1  123.14  490.25  126.13  491.15  138.09   498.5
  147.06  503.21  150.05  505.25  153.04  505.89  159.02  508.73     165  512.46
#Mann= 3 , 0 , 0
       0      .1       0   70.45      .1       0   95.22      .1       0
Bank Sta=70.45,95.22
XS Rating Curve= 0 ,0
Exp/Cntr=0.3,0.1

Type RM Length L Ch R = 1 ,1828.8  ,90.69,91.4,95.59
XS GIS Cut Line= 5
     613194.0716    4336466.7124     613160.5528    4336520.7148
     613153.9207    4336548.5138     613154.2172    4336553.2578
     613143.1322    4336644.7273
#Sta/Elev= 30
       0  513.42    3.03  511.19    9.08   505.2   15.13  499.32   18.16  496.43
   21.19  493.66   24.21  491.69   27.24  491.01   36.32  490.78   48.43  490.25
   60.53  489.86   83.61489.4553   86.42  489.19   92.14  488.04   94.51  487.82
   127.6  489.02  133.75  489.22  142.96  489.38  143.47489.4547  146.03  489.83
   149.1   491.6  152.17  494.36  155.25   496.9  158.32  498.75  164.46  501.74
  167.53  502.29   170.6  503.27  176.75  506.34  179.82  508.03  189.03  513.52
#Mann= 3 , 0 , 0
       0      .1       0   83.61      .1       0  143.47      .1       0
Bank Sta=83.61,143.47
XS Rating Curve= 0 ,0
Exp/Cntr=0.3,0.1

Type RM Length L Ch R = 1 ,1737.4  ,91.54,91.48,90.36
XS GIS Cut Line= 2
     613123.5667    4336419.7656     613039.9445    4336598.6897
#Sta/Elev= 30
       0  513.62    3.04  511.35    9.12  506.49   12.15  504.15   21.27  497.65
   27.35  493.16   30.38   491.7   33.42  490.98   36.46  489.66    39.5  489.38
   66.85  489.16   94.19  488.75  130.83488.3775  133.69  488.02  136.73  487.79
  139.77  487.36  142.81  487.12  145.85  487.15  148.89  487.38  151.95488.3755
  154.96  489.93     158  491.32  161.04  494.35  164.08  496.74  167.12  498.54
  170.15  499.25  173.19  500.18  191.42  510.15  194.46  512.05   197.5  514.13
#Mann= 3 , 0 , 0
       0      .1       0  130.83      .1       0  151.95      .1       0
Bank Sta=130.83,151.95
XS Rating Curve= 0 ,0
Exp/Cntr=0.3,0.1

Type RM Length L Ch R = 1 ,1645.92 ,92.53,91.44,89.65
XS GIS Cut Line= 4
     613003.5057    4336404.9098     612994.0407    4336479.8764
      612976.033    4336523.3067     612967.9026    4336568.9848
#Sta/Elev= 30
       0  503.13    3.02  500.38    6.04  497.97    9.07  495.77   12.09  494.22
   15.11  493.17   18.13  491.85   24.18  488.92   30.22   487.6   33.23486.2788
   36.27  485.68   39.29  485.66   57.43  486.01   84.38  487.18  102.01  487.51
  104.95  487.42  110.82  486.16  113.76  485.89   116.7   485.9  120.77486.2791
  122.58  486.55  125.48  486.59  128.38  487.09  134.18  487.64  137.08  488.68
  142.88  492.38  151.57  497.32  154.47  498.39  157.37   498.8  168.97  504.64
#Mann= 3 , 0 , 0
       0      .1       0   33.23      .1       0  120.77      .1       0
Bank Sta=33.23,120.77
XS Rating Curve= 0 ,0
Exp/Cntr=0.3,0.1

Type RM Length L Ch R = 1 ,1554.48 ,92.73,91.44,84.57
XS GIS Cut Line= 2
      612914.042    4336422.5608     612872.6653    4336572.5518
#Sta/Elev= 30
       0  504.72    3.05  502.64    9.15  497.35   18.31  489.62   21.36  489.53
   24.41  486.82   26.54485.5001   27.46  484.93   30.51   484.3   33.56  484.23
   48.81   484.6   57.97   484.5   61.02  484.59   64.07  485.01   65.94485.5005
   70.17  486.64   73.22  487.13   76.27   487.2   97.63  486.78  109.83  486.65
  112.88  487.17  115.93  488.17  122.03  488.94  125.08  489.85  128.14  491.33
  140.34  498.09  146.44  501.72  149.49   503.1  152.54  503.37  155.59  505.01
#Mann= 3 , 0 , 0
       0      .1       0   26.54      .1       0   65.94      .1       0
Bank Sta=26.54,65.94
XS Rating Curve= 0 ,0
Exp/Cntr=0.3,0.1

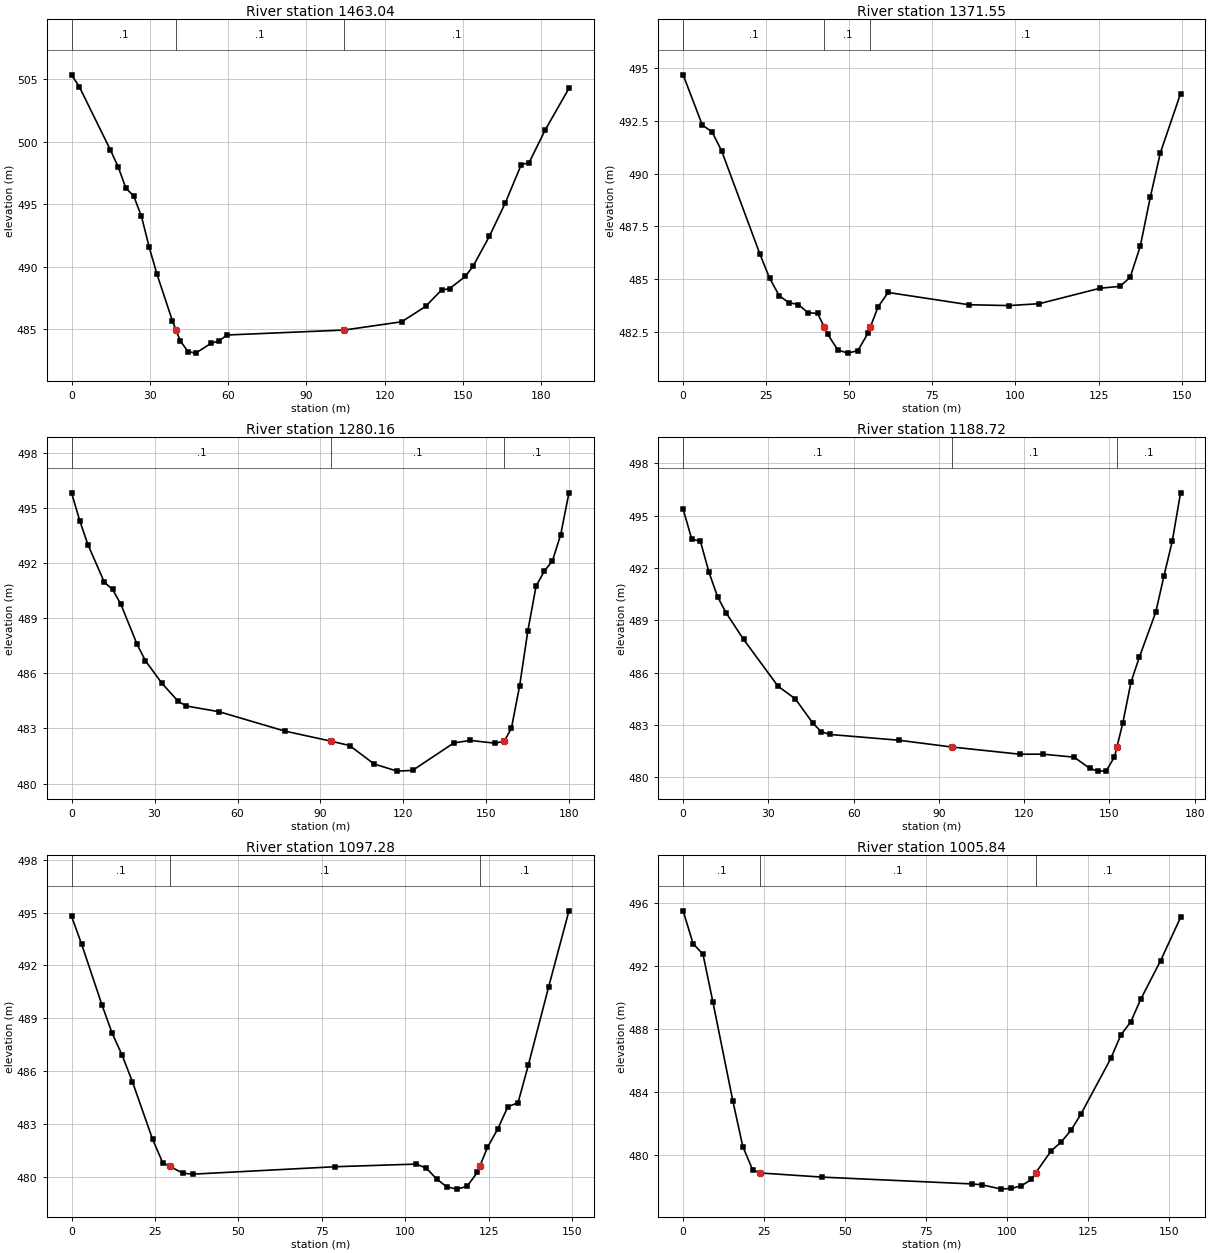
Type RM Length L Ch R = 1 ,1463.04 ,90.84,91.49,92.9
XS GIS Cut Line= 4
     612815.7583    4336399.7577     612813.4928     4336459.228
      612816.828    4336486.3741     612812.0849    4336590.0114
#Sta/Elev= 30
       0  505.35    2.98   504.4   14.88  499.34   17.85     498   20.83  496.28
   23.81  495.66   26.78  494.03   29.76  491.56   32.73   489.4   38.68  485.65
   40.04484.9244   41.66  484.06   44.64   483.2   47.61  483.08   53.56  483.88
   56.54  484.05   59.51  484.53  104.48484.9264  126.53  485.59  135.69  486.82
  141.79  488.13  144.84  488.24  150.94  489.22  153.99  490.08   160.1  492.42
   166.2  495.09   172.3  498.15  175.35  498.33  181.46  500.92  190.61  504.27
#Mann= 3 , 0 , 0
       0      .1       0   40.04      .1       0  104.48      .1       0
Bank Sta=40.04,104.48
XS Rating Curve= 0 ,0
Exp/Cntr=0.3,0.1

Type RM Length L Ch R = 1 ,1371.55 ,91.49,91.39,90.28
XS GIS Cut Line= 3
     612731.6201    4336396.9147     612723.2156    4336436.4938
     612723.4493    4336545.6936
#Sta/Elev= 30
       0  494.67    5.78  492.29    8.67  491.98   11.56  491.08   23.12  486.18
   26.01  485.05    28.9  484.22   31.79  483.89   34.68   483.8   37.57  483.41
   40.46  483.38   42.51482.7169   43.49   482.4   46.53  481.65   49.56   481.5
   52.59  481.62   55.63  482.45   56.28 482.716   58.66  483.69   61.69  484.37
   85.96  483.79   98.09  483.75  107.19  483.84   125.4  484.57  131.46  484.66
   134.5  485.09  137.53  486.55  140.56  488.88  143.59  490.98  149.66  493.78
#Mann= 3 , 0 , 0
       0      .1       0   42.51      .1       0   56.28      .1       0
Bank Sta=42.51,56.28
XS Rating Curve= 0 ,0
Exp/Cntr=0.3,0.1

Type RM Length L Ch R = 1 ,1280.16 ,80.36,91.44,85.6
XS GIS Cut Line= 5
     612665.9023    4336342.6255     612634.7326      4336409.83
     612631.5195    4336444.9571     612633.2234    4336458.8009
      612630.845    4336515.2665
#Sta/Elev= 30
       0  495.81    2.96   494.3    5.93  492.99   11.85  490.95   14.82  490.56
   17.78  489.77   23.71  487.57   26.67  486.69    32.6  485.47   38.52  484.48
   41.49  484.22   53.34  483.91   77.02  482.86   93.96482.3038  100.54  482.07
  109.35  481.07  117.72  480.68   123.3  480.72  138.18  482.21  144.12  482.35
  153.05   482.2  156.41482.3047     159     483  161.97   485.3  164.95   488.3
  167.92  490.73   170.9  491.55  173.87  492.12  176.84  493.54  179.82  495.81
#Mann= 3 , 0 , 0
       0      .1       0   93.96      .1       0  156.41      .1       0
Bank Sta=93.96,156.41
XS Rating Curve= 0 ,0
Exp/Cntr=0.3,0.1

Type RM Length L Ch R = 1 ,1188.72 ,84.88,91.44,94.44
XS GIS Cut Line= 4
     612593.8032    4336298.9691     612558.1833    4336411.8955
     612555.5817    4336436.3941      612542.539    4336465.5789
#Sta/Elev= 29
       0  495.37    3.04  493.64    6.07  493.53    9.11  491.74   12.14  490.34
   15.18  489.41   21.25  487.91    33.4  485.22   39.47   484.5   45.54  483.13
   48.58  482.62   51.61  482.46    75.9  482.13   94.43481.7429  118.41  481.33
  126.62  481.33  137.57  481.16  143.05  480.52  145.95  480.36  148.86  480.38
  151.77  481.17  152.63481.7424  154.67   483.1  157.58  485.46  160.48  486.87
   166.3  489.47   169.2  491.56  172.11  493.54  175.01   496.3
#Mann= 3 , 0 , 0
       0      .1       0   94.43      .1       0  152.63      .1       0
Bank Sta=94.43,152.63
XS Rating Curve= 0 ,0
Exp/Cntr=0.3,0.1

Type RM Length L Ch R = 1 ,1097.28 ,92.16,91.44,91.18
XS GIS Cut Line= 3
     612515.2385    4336284.9095     612479.1378     4336378.445
     612458.8466    4336422.8662
#Sta/Elev= 27
       0  494.79    3.04   493.2    9.11  489.77   12.15  488.17   15.19   486.9
   18.23  485.42   24.31  482.14   27.34  480.81   29.44480.6096   33.42  480.22
   36.46  480.17   78.99  480.59  103.31  480.74  106.36  480.51  109.42   479.9
  112.47  479.45  115.52  479.32  118.57  479.48  121.63  480.27  122.36480.6099
  124.68  481.69  127.73  482.72  130.78  483.99  133.84  484.22  136.89  486.33
  142.99  490.77   149.1   495.1
#Mann= 3 , 0 , 0
       0      .1       0   29.44      .1       0  122.36      .1       0
Bank Sta=29.44,122.36
XS Rating Curve= 0 ,0
Exp/Cntr=0.3,0.1

Type RM Length L Ch R = 1 ,1005.84 ,80.04,91.44,94.77
XS GIS Cut Line= 2
     612423.2977    4336259.4825     612373.6929    4336404.8761
#Sta/Elev= 26
       0  495.49    3.07  493.42    6.14  492.73    9.22  489.69   15.36  483.44
   18.43  480.56   21.51  479.06   23.88478.8824   43.01  478.62    89.1  478.19
   92.17  478.14   98.32  477.86  101.39  477.91  104.46  478.07  107.54  478.47
  108.85478.8839  113.68  480.29  116.75  480.84  119.83   481.6   122.9  482.63
  132.12  486.15  135.19  487.63  138.26  488.46  141.33  489.89  147.48  492.34
  153.62  495.07
#Mann= 3 , 0 , 0
       0      .1       0   23.88      .1       0  108.85      .1       0
Bank Sta=23.88,108.85
XS Rating Curve= 0 ,0
Exp/Cntr=0.3,0.1

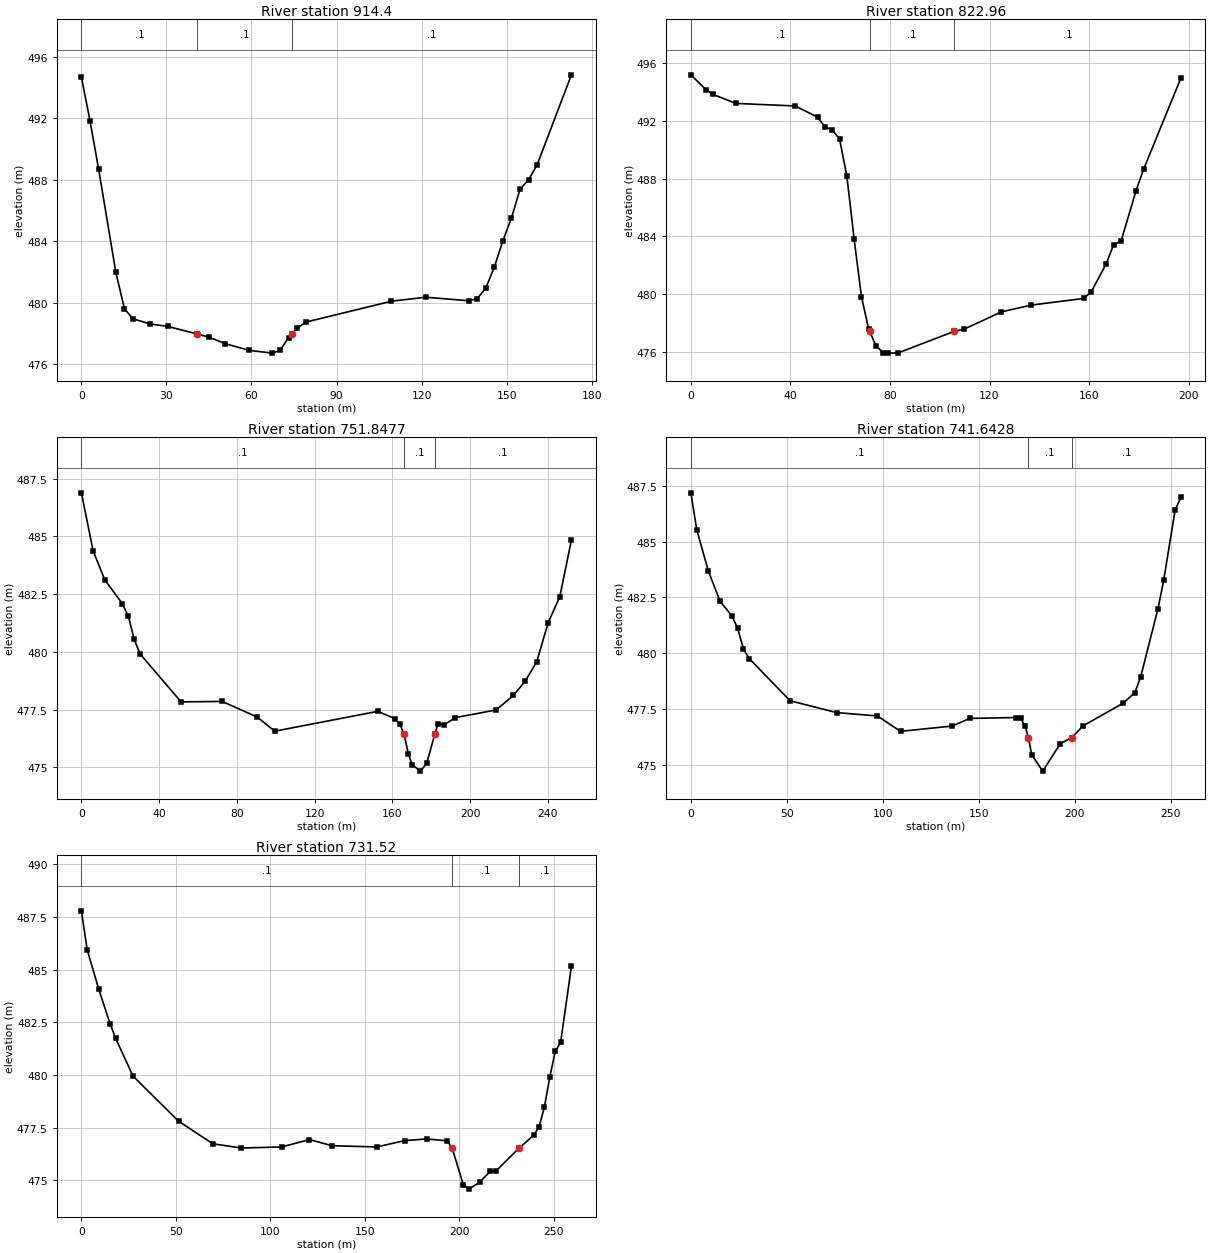
Type RM Length L Ch R = 1 ,914.4   ,100.41,91.44,82.71
XS GIS Cut Line= 5
     612348.4553    4336250.1612     612336.5025    4336287.8127
     612324.2421    4336299.5577     612312.6493    4336306.6823
     612247.3306    4336386.0437
#Sta/Elev= 30
       0  494.68    3.04  491.84    6.08  488.69   12.15  481.97   15.19   479.6
   18.23  478.95   24.31  478.62   30.39  478.46   40.94477.9638   45.16  477.75
   50.82  477.33    59.2   476.9   67.37  476.72   70.09  476.91   73.11  477.73
   74.27477.9643   76.13  478.34   79.16  478.74  109.39   480.1  121.48  480.36
   136.6  480.13  139.62  480.27  142.64  480.95  145.67  482.32  148.69  484.04
  151.71  485.52  154.74   487.4  157.76  488.01  160.78  488.99  172.87  494.84
#Mann= 3 , 0 , 0
       0      .1       0   40.94      .1       0   74.27      .1       0
Bank Sta=40.94,74.27
XS Rating Curve= 0 ,0
Exp/Cntr=0.3,0.1

Type RM Length L Ch R = 1 ,822.96  ,79.84,71.11,72.79
XS GIS Cut Line= 4
     612257.6494    4336182.0495      612241.816    4336227.3551
     612243.2875    4336283.1116     612223.5181    4336374.1374
#Sta/Elev= 30
       0  495.19       6  494.17       9  493.83      18  493.21   41.99  493.03
   50.93  492.25   53.86  491.59    56.8  491.37   59.73  490.75   62.67  488.18
   65.61  483.79   68.54  479.81   71.48  477.54   71.83477.4038   74.41   476.4
   77.35  475.92   79.06   475.9   83.22  475.91  105.71477.4028  109.78  477.56
   124.8  478.76  136.82  479.23  157.85  479.69  160.86  480.14  166.87  482.08
  169.87  483.42  172.88  483.67  178.89  487.16  181.89  488.63  196.92  494.97
#Mann= 3 , 0 , 0
       0      .1       0   71.83      .1       0  105.71      .1       0
Bank Sta=71.83,105.71
XS Rating Curve= 0 ,0
Exp/Cntr=0.3,0.1

Type RM Length L Ch R = 1 ,751.8477,9.93,10.2,10.53
XS GIS Cut Line= 6
     612248.1244    4336136.0119     612165.2139     4336179.285
      612164.486    4336235.3074     612168.5077    4336253.9341
     612172.1061    4336256.2625      612178.767    4336333.2894
#Sta/Elev= 30
       0  486.89    6.03  484.37   12.07  483.11   21.12  482.08   24.14  481.54
   27.15  480.54   30.17  479.91   51.29  477.83   72.41  477.85   90.51  477.17
   99.42  476.56  152.45  477.42  161.14  477.11  163.68  476.89  165.99 476.428
  168.17  475.59  170.12  475.11  174.41  474.83  177.64  475.17  181.82476.4297
  183.48  476.88  186.46  476.83  192.43  477.15  213.31  477.48  222.26  478.11
  228.23  478.72   234.2  479.56  240.16  481.27  246.13  482.39   252.1  484.85
#Mann= 3 , 0 , 0
       0      .1       0  165.99      .1       0  181.82      .1       0
Bank Sta=165.99,181.82
XS Rating Curve= 0 ,0
Exp/Cntr=0.3,0.1

Type RM Length L Ch R = 1 ,741.6428,2.46,10.12,9.92
XS GIS Cut Line= 6
     612247.8598    4336126.7515     612164.2513    4336170.1433
     612154.7494    4336232.4499      612158.771    4336251.9233
     612161.7344     4336254.675      612162.581    4336328.1235
#Sta/Elev= 30
       0  487.18    3.04  485.53    9.12  483.67   15.19  482.33   21.27  481.68
   24.31  481.13   27.35   480.2   30.39  479.76   51.66  477.87   75.97  477.34
    97.2  477.19   109.2   476.5  136.22  476.74  145.22  477.08   169.3  477.12
  171.74  477.08  174.18  476.72   175.8476.2245  177.58  475.45  183.31  474.72
  192.42  475.95  198.45476.2236  204.39  476.75  225.35  477.77  231.34  478.24
  234.33  478.94  243.31  481.98  246.31  483.26  252.29  486.42  255.29  486.98
#Mann= 3 , 0 , 0
       0      .1       0   175.8      .1       0  198.45      .1       0
Bank Sta=175.8,198.45
XS Rating Curve= 0 ,0
Exp/Cntr=0.3,0.1

Type RM Length L Ch R = 1 ,731.52  ,37.46,38.89,39.66
XS GIS Cut Line= 6
     612248.9182    4336118.2848      612150.493    4336157.4432
      612152.088    4336231.4889     612152.8394    4336245.1102
     612149.8785    4336270.6404       612133.38    4336307.1677
#Sta/Elev= 30
       0  487.79    3.03  485.95    9.08   484.1   15.13  482.44   18.16  481.74
   27.24  479.96   51.45  477.81   69.61  476.74   84.74  476.54  105.93  476.59
  120.74  476.94  132.59  476.65  156.29  476.59   171.1  476.89  182.72  476.97
  193.63  476.88   196.3476.5252   202.2  474.79  205.06  474.59  210.77  474.91
  216.48  475.44  219.34  475.44  231.59476.5255  239.38  477.14  242.24  477.53
   245.1  478.48  247.96   479.9  250.83  481.12  253.69  481.55  259.42  485.16
#Mann= 3 , 0 , 0
       0      .1       0   196.3      .1       0  231.59      .1       0
Bank Sta=196.3,231.59
XS Rating Curve= 0 ,0
Exp/Cntr=0.3,0.1