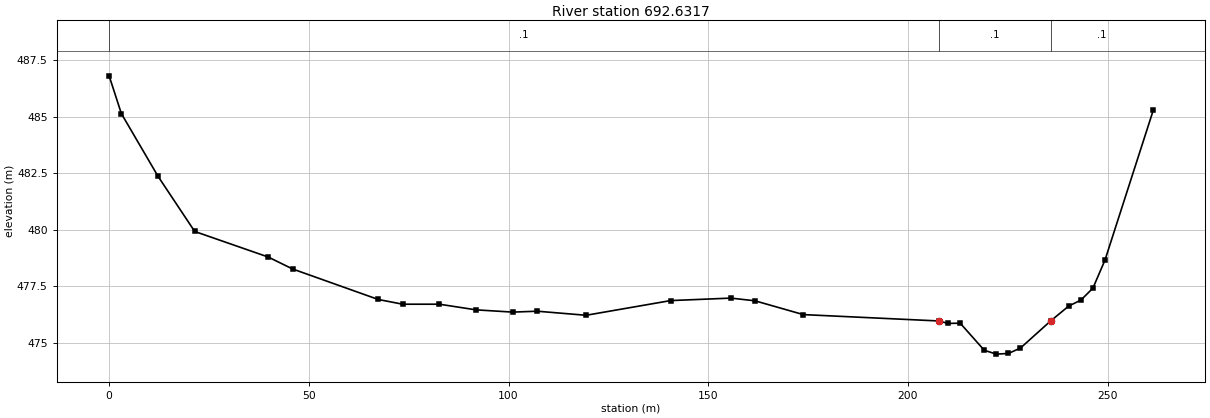
HEC-RAS study MinearRun.prj: MinearRun

--- MinearRun.g01 (geometry) --- (continued)

Type RM Length L Ch R = 1 ,692.6317,520.16,692.63,502.1
XS GIS Cut Line= 3
     612247.8598    4336110.8765     612135.5811     4336151.554
     612104.0288    4336289.9985
#Sta/Elev= 30
       0  486.82    3.06  485.15   12.25  482.37   21.43  479.93   39.81   478.8
   45.93  478.27   67.37  476.92   73.49  476.71   82.68  476.71   91.86  476.46
  101.05  476.36  107.17   476.4  119.42  476.22  140.57  476.87  155.67  476.98
  161.72  476.86   173.8  476.25  207.72 475.968  210.05  475.86  213.08  475.87
  219.12  474.67  222.14   474.5  225.16  474.53  228.18  474.77  235.72475.9676
  240.27  476.63  243.29  476.89  246.31  477.42  249.33  478.66  261.41  485.29
#Mann= 3 , 0 , 0
       0      .1       0  207.72      .1       0  235.72      .1       0
Bank Sta=207.72,235.72
XS Rating Curve= 0 ,0
Exp/Cntr=0.3,0.1
LCMann Table=0

Chan Stop Cuts=-1
Use User Specified Reach Order=0
Composite Channel Slope=5